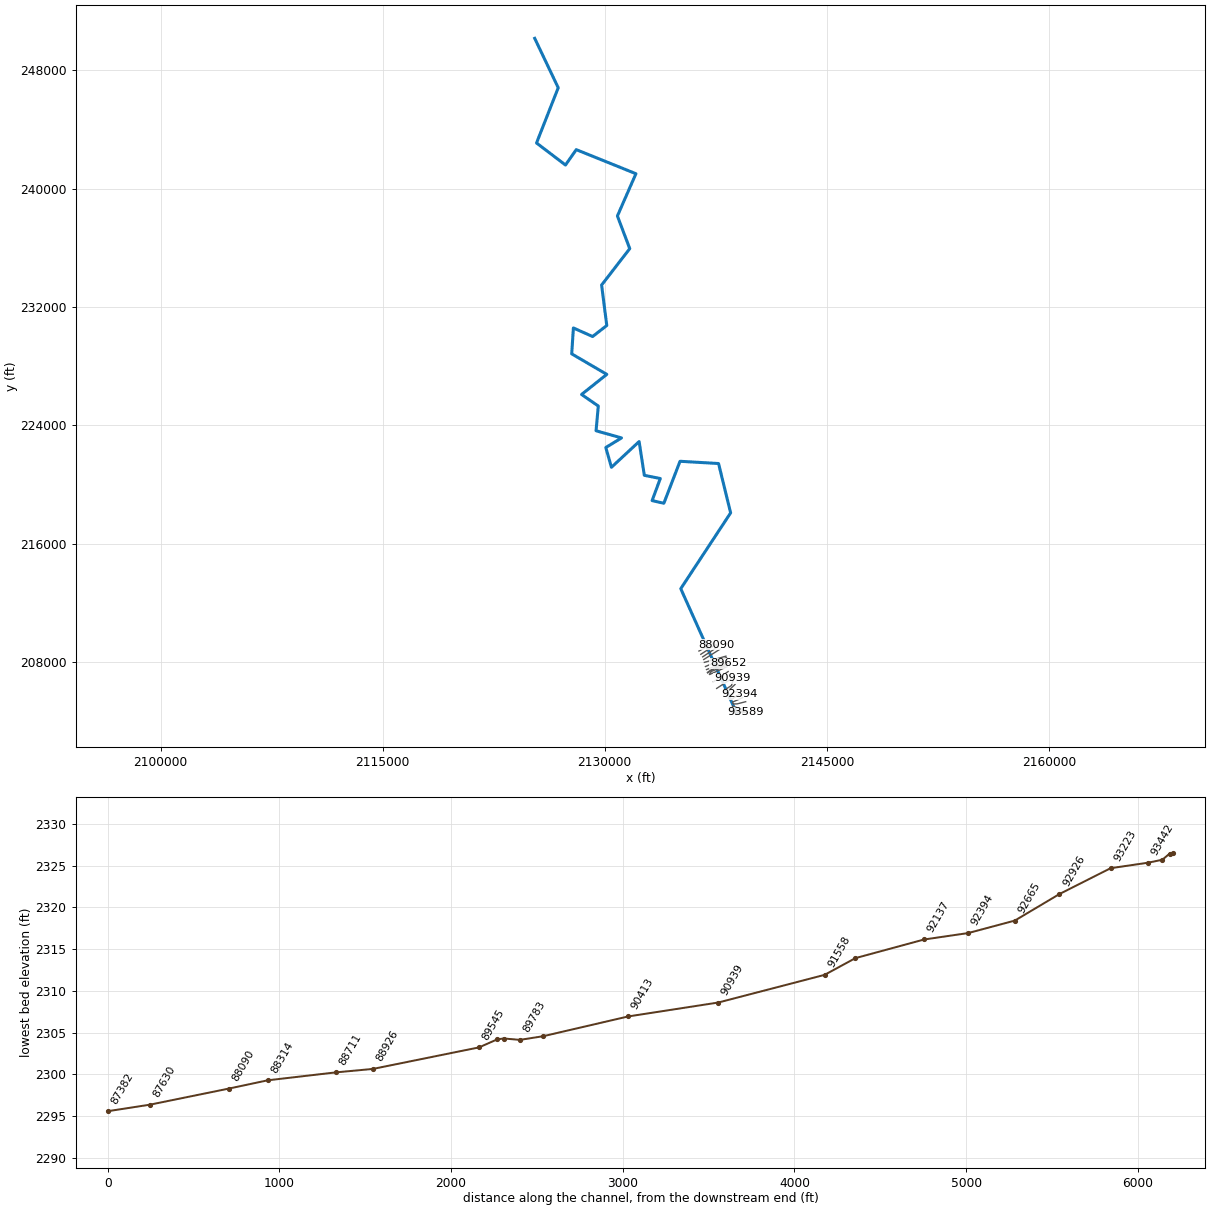
--- SECONDCK.prj (project) ---

Proj Title=SECONDCK
Current Plan=p01
Default Exp/Contr=0,0
English Units
Geom File=g01
Flow File=f01
Plan File=p01
Background Map Layer=Inundation Boundary (01pct Value_0)
Background Map Layer=LAURELCK3_River
Background Map Layer=LAURELCK3_XS
BEGIN DESCRIPTION:
Stream Name: Second Creek
Flood Zone: Approximate
Monroe County, West Virginia
HEC-RAS Version: 5.0.7
Vertical Datum: NAVD88
Projection: NAD 1983 StatePlane West Virginia S FIPS 4702 (US Feet)
LiDAR: 2016, 1-meter
Land Use: 2016 NLCD
Hydrology Method:
Gage-Weighted Regression. 0.2% and 1% plus profiles may cross due to varying approaches to compute 84% confidence interval for gage vs. regression flows.
Model Notes: DS boundary condition from KWSEL of Greenbrier County Second Creek model.
Starting at XS71524, the 0.2 % flows are higher than the 1% plus flows which is causing crossing profiles. All flow points US of the flow change applied at XS71524 have the 0.2% flows lower than the 0.1% plus flows. This inconsistency resulted from the gage weighted flows being developed at two different Counties- Greenbrier and Monroe.
END DESCRIPTION:
DSS Export Rating Curves= 0
DSS Export Rating Curve Sorted= 0
DSS Export Volume Flow Curves= 0
DXF OffsetX= 0
DXF OffsetY= 0
DXF ScaleX= 0
DXF ScaleY= 0

--- SECONDCK.p01 (plan) ---

Plan Title=Floodplain
Program Version=5.07
Short Identifier=Floodplain
Geom File=g01
Flow File=f01
Subcritical Flow
K Sum by GR= 0
Std Step Tol= 0.01
Critical Tol= 0.01
Num of Std Step Trials= 20
Max Error Tol= 0.3
Flow Tol Ratio= 0.001
Split Flow NTrial= 30
Split Flow Tol= 0.02
Split Flow Ratio= 0.02
Log Output Level= 0
Friction Slope Method= 1
Unsteady Friction Slope Method= 2
Unsteady Bridges Friction Slope Method= 1
Parabolic Critical Depth
Global Vel Dist= 0 , 0 , 0
Global Log Level= 0
CheckData=True
Encroach Param=-1 ,0,0, 0
Mapping Interval=1HOUR
Computation Time Step Use Courant=        0
Computation Time Step Use Time Series=    0
Computation Time Step Count To Double=0
Computation Time Step Max Doubling=0
Computation Time Step Max Halving=0
Computation Time Step Residence Courant=0
Run HTab= 0
Run UNet= 0
Run Sediment= 0
Run PostProcess= 0
Run WQNet= 0
Run RASMapper=-1
UNET Theta= 0
UNET Theta Warmup= 0
UNET ZTol= 0
UNET ZSATol= 0
UNET MxIter= 0
UNET Max Iter WO Improvement= 0
UNET MaxInSteps= 0
UNET DtIC= 0
UNET DtMin= 0
UNET MaxCRTS= 0
UNET WFStab= 0
UNET SFStab= 0
UNET WFX= 1
UNET SFX= 1
UNET 1D Methodology=Finite Difference
UNET DSS MLevel= 1
UNET Pardiso=0
UNET DZMax Abort= 0
UNET Use Existing IB Tables= 0
UNET Froude Reduction=False
UNET Froude Limit= 0
UNET Froude Power= 0
UNET D1 Cores= 0
UNET D2 Coriolis=0
UNET D2 Cores= 0
UNET D2 Theta= 1
UNET D2 Theta Warmup= 1
UNET D2 Z Tol= 0.01
UNET D2 Volume Tol= 0.01
UNET D2 Max Iterations= 20
UNET D2 Equation= 0
UNET D2 RampUpFraction=0.1
UNET D2 TimeSlices= 1
UNET D2 BCVolumeCheck=0
UNET D1D2 MaxIter= 0
UNET D1D2 ZTol=0.01
UNET D1D2 QTol=0.1
UNET D1D2 MinQTol=1
Write IC File= 0
Write IC File at Fixed DateTime=0
Write IC File at Sim End=0
Echo Input=False
Echo Parameters=False
Echo Output=False
Write Detailed= 0
HDF Write Warmup=0
HDF Write Time Slices=0
HDF Flush=0
HDF Face Node Velocities=0
HDF Compression= 1
HDF Chunk Size= 1
HDF Spatial Parts= 1
HDF Use Max Rows=0
HDF Fixed Rows= 1
Calibration Method= 0
Calibration Iterations= 20
Calibration Max Change=0.05
Calibration Tolerance=0.2
Calibration Maximum=1.5
Calibration Minimum=0.5
Calibration Optimization Method= 1
WQ AD Non Conservative
WQ ULTIMATE=-1
WQ Max Comp Step=1HOUR
WQ Output Interval=15MIN
WQ Output Selected Increments= 0
WQ Output face flow=0
WQ Output face velocity=0
WQ Output face area=0
WQ Output face dispersion=0
WQ Output cell volume=0
WQ Output cell surface area=0
WQ Output cell continuity=0
WQ Output cumulative cell continuity=0
WQ Output face conc=0
WQ Output face dconc_dx=0
WQ Output face courant=0
WQ Output face peclet=0
WQ Output face adv mass=0
WQ Output face disp mass=0
WQ Output cell mass=0
WQ Output cell source sink temp=0
WQ Output nsm pathways=0
WQ Output nsm derived pathways=0
WQ Output MaxMinRange=-1
WQ Daily Max Min Mean=-1
WQ Daily Range=0
WQ Daily Time=0
WQ Create Restart=0
WQ Fixed Restart=0
WQ System Summary=0
WQ Write To DSS=0
WQ Use Fixed Temperature=0
Sorting and Armoring Iterations= 10
XS Update Threshold= 0.02
Bed Roughness Predictor= 0
Hydraulics Update Threshold= 0.02
Energy Slope Method= 1
Volume Change Method= 1
Sediment Retention Method= 0
XS Weighting Method= 0
Number of US Weighted Cross Sections= 1
Number of DS Weighted Cross Sections= 1
Upstream XS Weight=0
Main XS Weight=1
Downstream XS Weight=0
Number of DS XS's Weighted with US Boundary= 1
Upstream Boundary Weight= 1
Weight of XSs Associated with US Boundary= 0
Number of US XS's Weighted with DS Boundary= 1
Downstream Boundary Weight= 0.5
Weight of XSs Associated with DS Boundary= 0.5
Percentile Method= 0
Sediment Output Level= 3
Mass or Volume Output= 0
Output Increment Type= 1
Profile and TS Output Increment= 1
XS Output Flag= 0
XS Output Increment= 10
Write Gradation File= 0
Read Gradation Hotstart= 0
Write HDF5 File= 1
Write Binary Output= 1
Write DSS Sediment File= 0
SV Curve= 0
Specific Gage Flag= 0

--- SECONDCK.f01 (steady flow) ---

Flow Title=Flow
Program Version=5.07
Number of Profiles= 6
Profile Names=01pct,10pct,04pct,02pct,0_2pct,01plus
River Rch & RM=SECONDCK,Main            ,93589
    2030    1130    1460    1740    2770    3000
River Rch & RM=SECONDCK,Main            ,93223
    3160    1780    2300    2720    4270    4670
River Rch & RM=SECONDCK,Main            ,92665
    3520    2000    2570    3030    4760    5210
River Rch & RM=SECONDCK,Main            ,89919
    3870    2200    2820    3330    5210    5720
River Rch & RM=SECONDCK,Main            ,71524
    4980    2780    3620    4300    6800    5470
River Rch & RM=SECONDCK,Main            ,70113
    5310    2970    3870    4590    7240    5840
River Rch & RM=SECONDCK,Main            ,69153
    5630    3160    4100    4860    7660    6190
River Rch & RM=SECONDCK,Main            ,58451
    6230    3510    4550    5380    8460    6850
River Rch & RM=SECONDCK,Main            ,20628
    7750    4390    5680    6700   10500    8520
River Rch & RM=SECONDCK,Main            ,20014
    8610    4890    6310    7430   11600    9460
River Rch & RM=SECONDCK,Main            ,9833
    9110    5180    6690    7870   12200   10000
Boundary for River Rch & Prof#=SECONDCK,Main            , 1
Up Type= 0
Dn Type= 1
Dn Known WS=1817.38
Boundary for River Rch & Prof#=SECONDCK,Main            , 2
Up Type= 0
Dn Type= 1
Dn Known WS=1815.882
Boundary for River Rch & Prof#=SECONDCK,Main            , 3
Up Type= 0
Dn Type= 1
Dn Known WS=1816.514
Boundary for River Rch & Prof#=SECONDCK,Main            , 4
Up Type= 0
Dn Type= 1
Dn Known WS=1816.952
Boundary for River Rch & Prof#=SECONDCK,Main            , 5
Up Type= 0
Dn Type= 1
Dn Known WS=1818.295
Boundary for River Rch & Prof#=SECONDCK,Main            , 6
Up Type= 0
Dn Type= 1
Dn Known WS=1817.659
DSS Import GetInterval= 0
DSS Import GetPeak= 0
DSS Import FillOption= 0

--- SECONDCK.g01 (geometry) ---

Geom Title=Geometry
Program Version=5.07

River Reach=SECONDCK        ,Main
Reach XY= 30
2138906.74657641 204577.80146324     2135133.335212977.183999991
     2138501.391218097.626999985     2137685.983221430.091999994
2135085.07099999221580.915999996     2133991.716218745.714999999
     2133200.701 218926.92199999     2133750.831220416.721999998
     2132673.357220633.736000007     2132321.534222914.335000001
     2130453.044221174.751999982     2130070.174222510.283999998
     2131133.542223159.155999983     2129413.707223643.097000002
     2129564.532225313.018999983     2128434.974226093.182999985
     2130138.533227450.604999985     2127769.827228836.239000011
     2127882.674230585.371000003     2129180.417230007.028999997
     2130137.448230750.300999997     2129788.056233483.591000002
     2131689.098235942.358999998     2130854.679238147.219999995
      2132105.33241002.211000016     2128076.468242627.644999984
     2127349.102241589.609999982     2125393.373243076.589000009
     2126858.217246807.0579999792125270.19152561250144.564208394

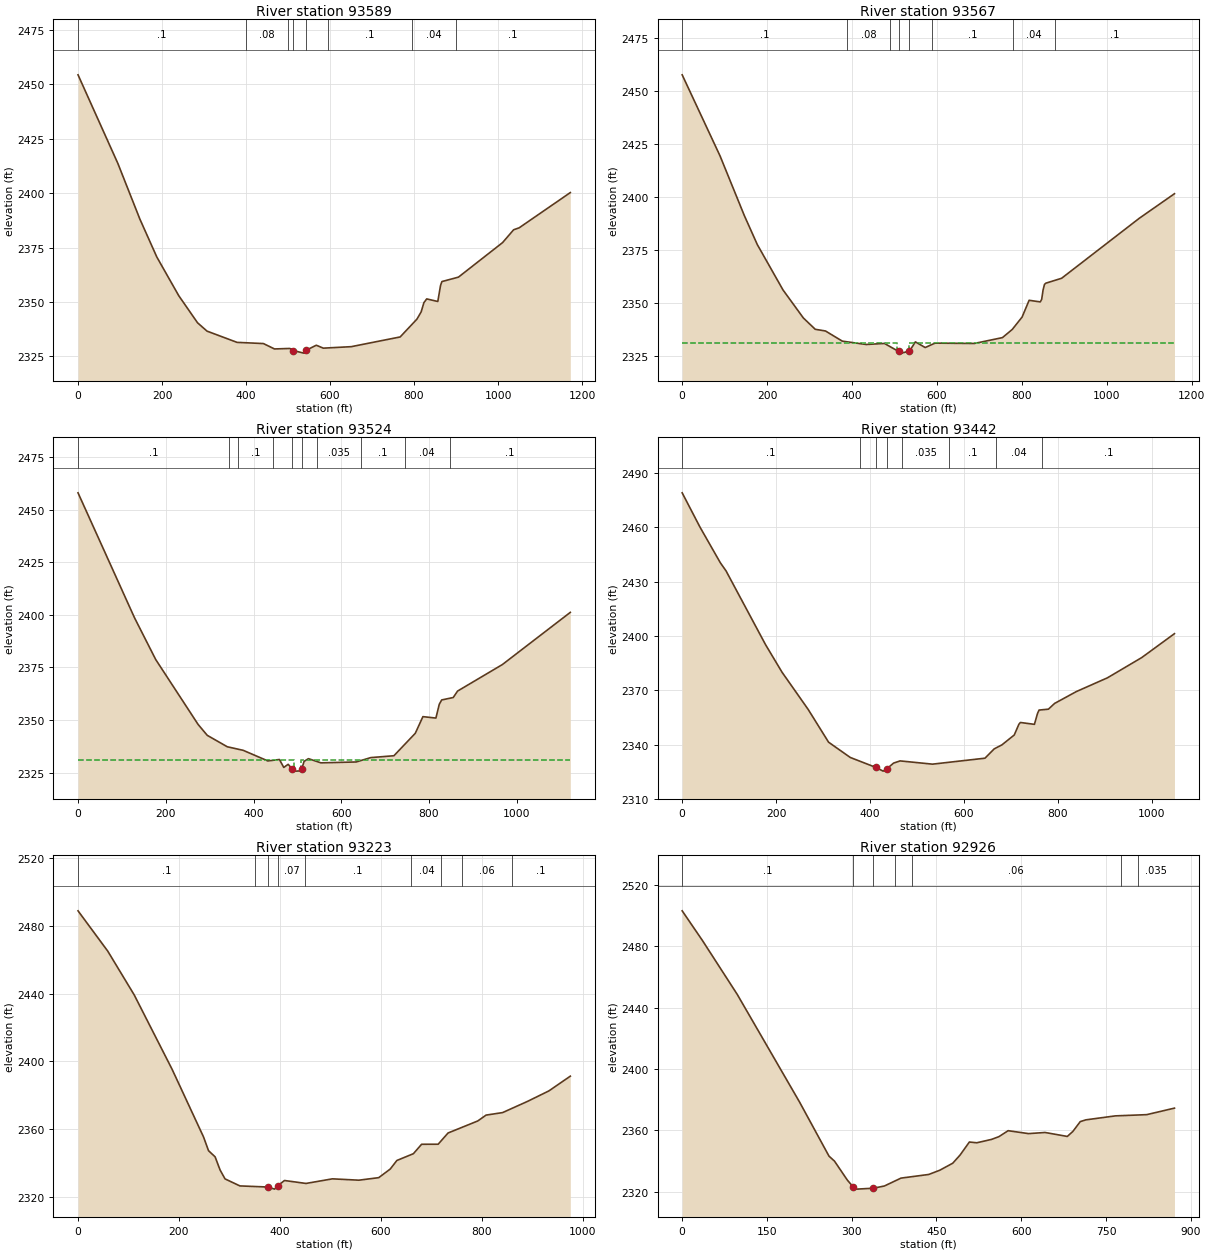
Type RM Length L Ch R = 1 ,93589   ,21.8,21.8,21.8
XS GIS Cut Line= 5
 2138433.0257029204748.0675686212138702.04848736204556.728234778
2138905.73525294204584.4771133442139205.47472938204634.992652248
2139537.71118605204622.083467727
#Sta/Elev= 30
       0 2454.43      95 2413.61   147.3 2388.07   187.6 2370.65   239.9 2352.84
   284.5 2340.42   307.1 2336.57   378.6  2331.4   441.4 2330.85   467.8 2328.37
   504.3  2328.6   512.7 2327.64   537.4 2326.45   543.3 2327.77   567.3 2330.08
     584 2328.74   650.5 2329.42     767 2333.89   806.9 2342.08   816.9 2345.39
   823.5 2349.65   830.2 2351.38   856.6  2350.2   863.1 2357.55   866.4 2359.36
   905.8  2361.4  1010.9 2377.29  1037.1 2383.17  1050.3 2384.07  1172.1 2400.28
#Mann= 8 ,-1 , 0
       0      .1       0  400.13     .08       0  500.13    .035       0
   512.7    .045       0   543.3    .035       0   595.7      .1       0
   795.7     .04       0  899.66      .1       0
Bank Sta=512.7,543.3
XS Rating Curve= 0 ,0
Exp/Cntr(USF)=0,0
Exp/Cntr=0.5,0.3

Type RM Length L Ch R = 1 ,93567   ,45.5,43,41.9
XS GIS Cut Line= 4
 2138440.3666954204762.8868137172138702.33258133204580.259487992
2139206.48618026204644.3063026852139538.37207277 204645.00016648
#Sta/Elev= 30
       0 2457.53    89.4 2419.24   146.4 2391.22     177 2377.55   237.4 2356.22
   285.4 2342.99   313.4 2337.66   337.5 2336.86   377.2 2332.07   433.5  2330.5
   476.4 2330.99     5102327.197   516.1 2326.43   535.32327.354   549.2 2331.73
   572.4 2329.07   595.5 2331.14   688.1 2330.98   754.3 2333.74   777.4 2337.59
   800.6 2343.43   817.1 2351.32   843.4 2350.56   846.7 2351.78     850 2356.19
   853.3 2358.81   856.5 2359.38   893.7  2361.7  1076.4 2389.93  1159.4 2401.52
#Mann= 8 ,-1 , 0
       0      .1       0  389.34     .08       0  489.34    .035       0
     510    .045       0   535.3    .035       0  589.34      .1       0
  779.34     .04       0  877.55      .1       0
#XS Ineff= 2 , 0
             505    2331     535            2331
Permanent Ineff=
       F       F
Bank Sta=510,535.3
XS Rating Curve= 0 ,0
Exp/Cntr=0.5,0.3

Type RM Length L Ch R = 1 ,93524   ,85.6,82.3,78.2
XS GIS Cut Line= 4
 2138474.2910844204793.8614114382138714.47064619204623.230292378
2139213.59250302 204681.614497192139537.55793857204654.574858136
#Sta/Elev= 30
       0 2458.07   128.8 2398.62   177.1 2378.77   273.7 2347.91   294.6 2342.71
   340.2 2337.28   376.6 2335.58   432.7 2330.54   459.1 2331.22     469 2327.45
     479 2328.93   488.6 2326.66   496.7 2325.69   508.7 2325.83  510.18 2326.83
   515.3 2330.32   525.2 2331.62   553.7 2329.63   634.2 2330.05   667.2 2332.12
   720.1 2333.01   768.8 2343.68   786.2 2351.61   815.8 2350.93   823.5 2357.49
     829 2359.55   855.3  2360.7   865.2 2363.77   967.3 2376.38  1122.2 2401.21
#Mann= 10 ,-1 , 0
       0      .1       0  344.62     .08       0  364.62      .1       0
  444.62     .07       0   488.6    .045       0  510.18     .07       0
  544.62    .035       0  644.62      .1       0  744.62     .04       0
  847.15      .1       0
#XS Ineff= 2 , 0
           491.7    2331   508.3            2331
Permanent Ineff=
       F       F
Bank Sta=488.6,510.18
XS Rating Curve= 0 ,0
Exp/Cntr=0.5,0.3

Type RM Length L Ch R = 1 ,93442   ,223.5,218.8,212
XS GIS Cut Line= 4
 2138548.1641022204913.7450263572138811.36124157204733.893647791
2139218.92224509204711.8163689322139537.56601527 204667.78729962
#Sta/Elev= 30
       0 2478.95    37.7 2460.14    81.4  2440.3    93.4 2435.88   177.6 2395.14
   212.6 2379.98   268.2 2359.47   311.9  2341.3   358.1 2332.88   412.42327.406
   428.1 2325.34   436.2 2326.69   450.3 2329.77   464.2 2330.98   533.2 2329.19
     645 2332.48   664.7 2337.64     681 2339.81   707.4  2345.3   717.2  2351.2
   720.5 2352.19   750.3 2351.16   756.9 2357.16   760.2 2359.04   780.1 2359.53
   793.3 2362.71   839.7 2369.26   905.9 2376.85   978.8    2388  1048.6 2401.21
#Mann= 8 ,-1 , 0
       0      .1       0  378.78     .07       0   412.4    .045       0
   436.2     .07       0  468.78    .035       0  568.78      .1       0
  668.78     .04       0  766.94      .1       0
Bank Sta=412.4,436.2
XS Rating Curve= 0 ,0
Exp/Cntr(USF)=0,0
Exp/Cntr=0.3,0.1

Type RM Length L Ch R = 1 ,93223   ,285.7,297.7,309.1
XS GIS Cut Line= 2
     2138632.746       205037.36     2139565.079      204751.531
#Sta/Elev= 30
       0 2488.75    58.9 2464.98   111.3 2439.19   186.5 2395.24   248.7 2355.39
   258.5 2347.35   271.6  2343.7   281.4 2335.97   291.2 2330.72   320.7 2326.57
   376.3 2325.92   389.4 2324.68     396 2326.76     409 2329.76   451.6 2328.03
   503.9 2330.74   556.3 2329.95   595.6 2331.44   618.5 2336.52   631.6 2341.57
   664.3 2345.56   680.6 2351.12   713.4 2351.15     733 2357.77   791.9 2364.87
   808.3 2368.32     841 2369.79   890.1 2376.36   932.6 2382.56   975.2 2391.28
#Mann= 9 ,-1 , 0
       0      .1       0     350     .08       0   376.3    .045       0
     396     .07       0     450      .1       0     660     .04       0
     720      .1       0     760     .06       0     860      .1       0
Bank Sta=376.3,396
XS Rating Curve= 0 ,0
Exp/Cntr=0.3,0.1

Type RM Length L Ch R = 1 ,92926   ,253.1,260.4,260
XS GIS Cut Line= 3
     2138665.774      205192.504     2138941.815      205197.712
     2139518.204      205345.281
#Sta/Elev= 30
       0 2503.04    35.7 2483.78    97.4 2448.58   207.9 2378.24   259.8 2343.11
   269.6 2339.81   292.4 2327.42   302.2 2323.22   308.8 2321.59   338.2 2322.18
   357.8 2323.63   387.2 2328.77   436.3 2331.15   455.9 2333.92   478.8  2338.5
   491.8 2343.84   508.2  2352.3   521.3 2351.81   547.4 2354.01   560.5 2355.81
   576.8 2359.69   612.8 2357.79   642.2 2358.52   681.5 2355.94   691.3  2359.2
   704.4  2365.6   714.2 2366.75   766.5 2369.35     822 2370.15   871.1  2374.4
#Mann= 7 ,-1 , 0
       0      .1       0   302.2    .045       0   338.2      .1       0
  376.09     .08       0  406.09     .06       0  776.09      .1       0
  806.09    .035       0
Bank Sta=302.2,338.2
XS Rating Curve= 0 ,0
Exp/Cntr=0.3,0.1

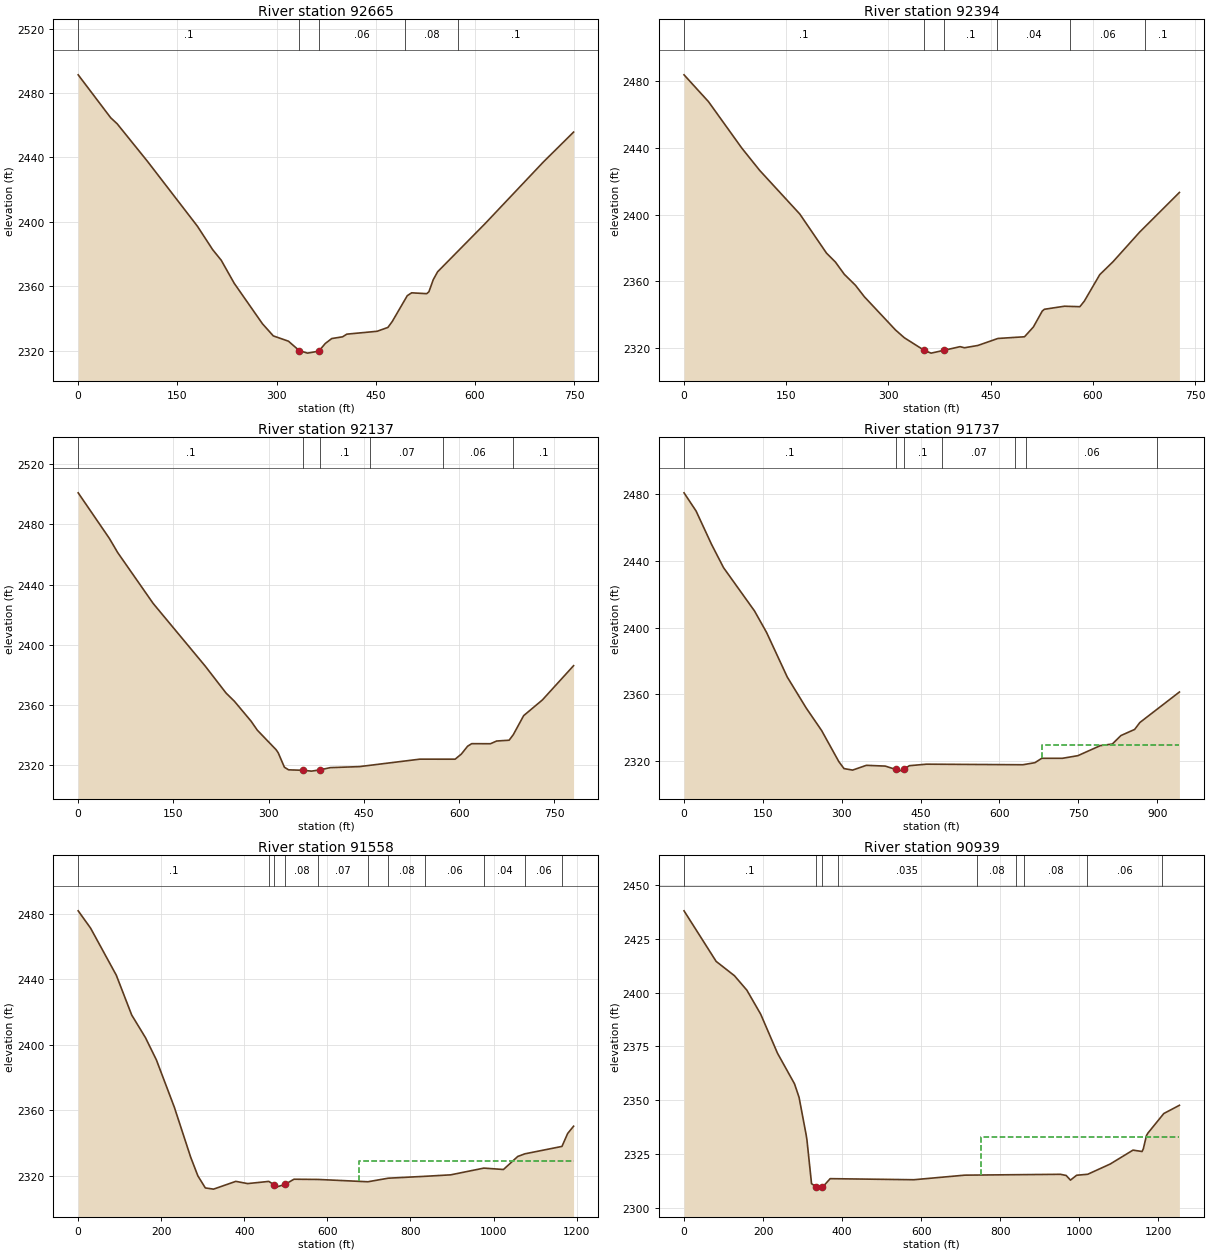
Type RM Length L Ch R = 1 ,92665   ,262.9,271.2,273
XS GIS Cut Line= 3
     2138637.086      205321.648     2138961.827       205462.53
     2139322.024      205624.795
#Sta/Elev= 30
       0 2491.27    49.2 2464.58      59 2460.84   104.9 2437.46   180.3 2397.22
   203.2 2382.76   216.3 2376.09     236 2361.74   278.6 2336.66     295 2329.12
   317.9 2325.82   334.3 2319.98   346.8 2318.41   363.8 2319.63   373.6  2324.4
   383.4 2327.47   399.7 2328.54   406.2  2330.2   451.9 2331.97   468.3 2334.37
   474.8 2338.02   497.6  2354.1   504.2 2355.87     527 2355.34   530.3 2356.54
   536.8 2363.98   543.4 2368.91   615.2 2398.83   703.3 2437.12     749 2455.69
#Mann= 5 ,-1 , 0
       0      .1       0   334.3    .045       0   363.8     .06       0
  493.98     .08       0  573.98      .1       0
Bank Sta=334.3,363.8
XS Rating Curve= 0 ,0
Exp/Cntr=0.3,0.1

Type RM Length L Ch R = 1 ,92394   ,252.1,256.7,262.6
XS GIS Cut Line= 3
     2138494.111       205450.75     2138882.788      205727.226
     2139106.746      205838.337
#Sta/Elev= 30
       0 2483.76    35.9 2467.67    84.9 2439.77   111.1 2426.43   169.9  2400.3
   209.1 2376.86   222.2  2371.5   235.2 2364.18   251.6 2357.59   264.6 2350.73
   310.4 2330.78   323.4 2326.11   352.8 2318.51   362.6 2316.92   382.2 2318.67
   405.1  2320.8   411.6 2320.14   431.2 2321.51   460.6 2325.71   499.7 2326.73
   512.7  2332.6   525.7 2342.13   528.9 2343.21   558.2 2345.04   580.9 2344.76
   587.4 2348.06   610.1 2363.97   629.6 2371.73   668.5 2389.42     727 2413.24
#Mann= 6 ,-1 , 0
       0      .1       0   352.8    .045       0   382.2      .1       0
     460     .04       0  566.98     .06       0  676.98      .1       0
Bank Sta=352.8,382.2
XS Rating Curve= 0 ,0
Exp/Cntr=0.3,0.1

Type RM Length L Ch R = 1 ,92137   ,400.3,400.3,393.1
XS GIS Cut Line= 3
     2138368.899      205572.712     2138726.538      205970.281
     2138959.177      206048.406
#Sta/Elev= 30
       0 2500.89    49.2 2470.58    62.3 2461.19   118.1 2427.46   200.1 2385.86
   232.9 2367.97     246 2362.55   272.3 2349.31   282.1 2343.35   311.7 2330.37
     315 2328.34   324.8 2318.74   331.4 2317.01   354.3  2316.7   367.4 2316.15
   380.6 2316.96     397 2318.47   442.9 2319.14     538 2324.09   593.7 2324.08
   603.5 2327.49   613.3 2332.68   619.8 2334.38   649.3 2334.33   659.1 2336.14
   678.7 2336.67   685.3 2340.36   701.6 2352.98   731.1  2363.4   780.2 2386.14
#Mann= 6 ,-1 , 0
       0      .1       0   354.3    .045       0   380.6      .1       0
     460     .07       0  574.76     .06       0  684.76      .1       0
Bank Sta=354.3,380.6
XS Rating Curve= 0 ,0
Exp/Cntr=0.3,0.1

Type RM Length L Ch R = 1 ,91737   ,181.3,179.4,173.4
XS GIS Cut Line= 2
     2138113.123      205861.194     2138797.718      206508.476
#Sta/Elev= 30
       0 2480.95    22.9 2470.05    52.3 2450.04    75.2 2436.01   134.1 2410.03
     157 2397.14   196.3 2370.42   232.3 2351.83   261.7 2338.28   294.4 2319.64
   304.2 2315.45   320.6 2314.54   346.8  2317.4   382.8 2316.94   402.4 2314.96
   408.9 2313.92   418.7 2315.21   428.6 2317.18   461.3 2318.09   644.5 2317.75
   667.4 2318.99   680.4 2321.62   719.7 2321.62   749.1  2323.2   791.7 2329.22
   814.6 2330.19   830.9 2335.26   857.1 2338.96   866.9 2343.08   942.2  2361.4
#Mann= 7 ,-1 , 0
       0      .1       0   402.4    .045       0   418.7      .1       0
     490     .07       0     630     .04       0     650     .06       0
     900      .1       0
#XS Ineff= 2 , 0
                          680.89         2329.81
Permanent Ineff=
       F       F
Bank Sta=402.4,418.7
XS Rating Curve= 0 ,0
Exp/Cntr=0.3,0.1

Type RM Length L Ch R = 1 ,91558   ,606.9,618.6,614.7
XS GIS Cut Line= 4
2138076.93219189205911.7896363682138055.15499694206107.490156127
2138560.62175189206442.9769403862138676.26232321206814.551303053
#Sta/Elev= 30
       02481.733   29.832471.188  91.8192442.421 128.8622418.162 161.873  2404.4
 188.2822390.786 231.4192361.969 270.7972331.448 288.1952320.006 306.1392312.645
 325.9252311.917 379.5112316.657 407.9122315.296     4592316.628 470.6472314.731
 475.5582313.086 497.851 2314.78 519.5752317.958 577.9382317.824  697.562316.412
 746.367 2318.58  834.952319.736 896.799 2320.63  976.892324.7461023.9322323.893
1058.293 2331.841075.4732333.457 1164.812337.9791178.5542345.8881192.731  2350.3
#Mann= 11 ,-1 , 0
       0      .1       0     459     .08       0 470.647    .045       0
 497.851     .08       0 577.938     .07       0  697.56     .06       0
 746.367     .08       0  834.95     .06       0  976.89     .04       0
1075.473     .06       0 1164.81      .1       0
#XS Ineff= 2 , 0
                          677.29         2328.95
Permanent Ineff=
       F       F
Bank Sta=470.647,497.851
XS Rating Curve= 0 ,0
Exp/Cntr=0.3,0.1

Type RM Length L Ch R = 1 ,90939   ,522.2,525.6,524.4
XS GIS Cut Line= 2
2137558.15193013206241.4736936122138606.45859671 206927.63805719
#Sta/Elev= 30
       0 2438.04    81.2 2414.53   127.5 2407.86     159 2401.11   193.9 2389.97
   236.5 2371.78   279.4 2357.59     291 2351.25   308.8 2333.92   310.8 2331.62
   322.5 2311.15   334.3  2309.7   343.2 2308.61     350 2309.45   369.6 2313.48
   581.3 2312.98   710.2 2315.11   952.2  2315.5   966.5 2314.96   977.4  2312.8
     993 2315.07    1021 2315.52  1077.8 2320.28  1135.5 2326.75  1158.4 2326.11
  1161.6 2327.34  1169.5 2333.49  1173.4 2334.71  1213.4 2343.77  1252.9  2347.6
#Mann= 9 ,-1 , 0
       0      .1       0   334.3    .045       0     350      .1       0
     390    .035       0     740     .08       0     840     .06       0
     860     .08       0    1020     .06       0    1210     .04       0
#XS Ineff= 2 , 0
                           752.2          2332.7
Permanent Ineff=
       F       F
Bank Sta=334.3,350
XS Rating Curve= 0 ,0
Exp/Cntr(USF)=0,0
Exp/Cntr=0.3,0.1

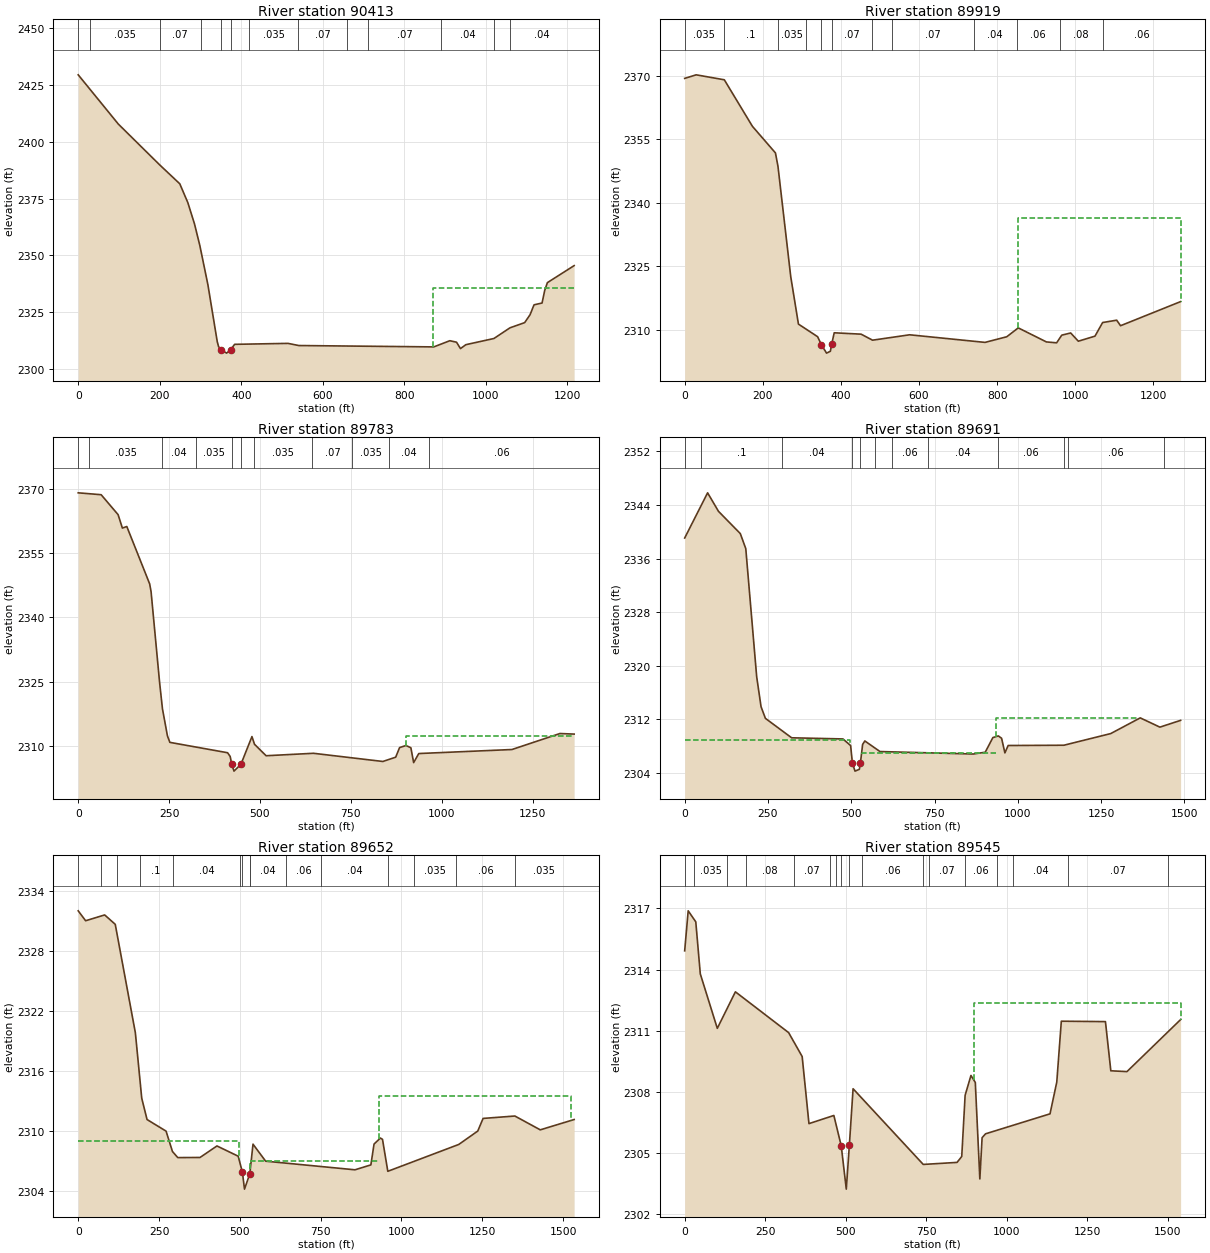
Type RM Length L Ch R = 1 ,90413   ,498.4,494.1,490.3
XS GIS Cut Line= 2
     2137337.564      206684.182     2138334.135      207381.978
#Sta/Elev= 30
       0 2429.44    98.4 2407.77     200 2389.78   249.2 2381.47   268.9  2373.2
   285.3  2363.8   298.4 2354.26   318.1  2337.1     341 2312.08   344.3 2309.81
   350.9  2308.4     364 2306.94   373.8 2308.41   383.7 2310.81   514.8 2311.23
   541.1 2310.28   872.3 2309.68   911.6  2312.4     928 2311.76   937.8 2308.93
     951 2310.66  1019.8 2313.38  1059.2 2318.08  1095.2 2320.37  1108.4 2323.83
  1118.2  2328.2  1137.9    2329  1144.4 2334.55    1151 2337.97  1216.6 2345.46
#Mann= 13 ,-1 , 0
       0      .1       0      30    .035       0     200     .07       0
     300      .1       0   350.9    .045       0   373.8      .1       0
     420    .035       0     540     .07       0     660    .035       0
     710     .07       0     890     .04       0    1020    .035       0
    1060     .04       0
#XS Ineff= 2 , 0
                          869.47         2335.56
Permanent Ineff=
       F       F
Bank Sta=350.9,373.8
XS Rating Curve= 0 ,0
Exp/Cntr=0.3,0.1

Type RM Length L Ch R = 1 ,89919   ,136.7,135.8,134.9
XS GIS Cut Line= 2
     2137102.921      207192.806     2138263.822      207707.499
#Sta/Elev= 30
       0 2369.32    29.5 2370.16   101.5 2368.99   173.5 2358.02   232.4 2351.76
   238.9  2348.6   271.6 2322.59   291.3 2311.42   340.4 2308.45   350.2 2306.53
   363.3 2304.58   373.1 2305.02   376.4 2306.66   382.9 2309.37   451.7 2309.05
   481.1 2307.63     576  2308.9   769.1 2307.11   824.8 2308.44   854.2 2310.53
   926.2 2307.22   952.4 2307.01   965.5 2308.81   988.4 2309.33    1008 2307.39
  1050.6 2308.58  1070.2 2311.79  1106.2 2312.34  1116.1 2311.04  1269.9 2316.72
#Mann= 12 ,-1 , 0
       0    .035       0     100      .1       0     240    .035       0
     310     .07       0   350.2    .045       0   376.4     .07       0
     480    .035       0     530     .07       0     740     .04       0
     850     .06       0     960     .08       0    1070     .06       0
#XS Ineff= 2 , 0
                          852.71         2336.43
Permanent Ineff=
       F       F
Bank Sta=350.2,376.4
XS Rating Curve= 0 ,0
Exp/Cntr=0.3,0.1

Type RM Length L Ch R = 1 ,89783   ,89.3,92.9,93.9
XS GIS Cut Line= 3
 2137075.9749504207197.7627960772137204.38367239207393.533470585
2138254.80911948207810.335551794
#Sta/Elev= 30
       0 2369.06    63.1 2368.62   109.7 2363.97   121.5 2360.84   133.7  2361.2
   196.5 2347.83   200.4 2346.03   223.9 2324.81   231.8 2318.65   245.4 2312.38
   252.1 2310.85   410.9 2308.43     418 2307.57   422.3 2305.78   428.5 2304.14
   447.6 2305.74   477.9  2312.2     485  2310.4   516.8 2307.73   647.2  2308.3
     838 2306.39   873.3 2307.39   883.9 2309.62   901.5 2310.12   915.1 2309.59
   922.7 2306.13   936.8 2308.24  1193.1 2309.18  1325.1 2312.91  1364.2 2312.78
#Mann= 11 ,-1 , 0
       0      .1       0      30    .035       0     230     .04       0
  324.13    .035       0   422.3    .045       0   447.6     .07       0
  484.13    .035       0  644.13     .07       0  754.13    .035       0
  854.13     .04       0  964.13     .06       0
#XS Ineff= 2 , 0
                          900.79         2312.28
Permanent Ineff=
       F       F
Bank Sta=422.3,447.6
XS Rating Curve= 0 ,0
Exp/Cntr(USF)=0,0
Exp/Cntr=0.5,0.3

Type RM Length L Ch R = 1 ,89691   ,38.1,38.5,37.5
XS GIS Cut Line= 5
     2136952.232      207289.726      2137167.51      207439.031
     2137441.815      207586.601      2137519.94      207623.059
     2138302.885      207894.999
#Sta/Elev= 30
       0 2339.06    68.8  2345.8   101.5 2343.04     167 2339.72   183.4 2337.48
   216.1 2318.38   229.2 2313.91   242.3 2312.17     321 2309.27   475.1  2309.1
   498.1 2308.11  503.32 2305.55   511.2  2304.3   524.3 2304.57   527.6 2305.58
   534.1 2308.28   540.7  2308.8   586.2 2307.22   866.1 2306.85   902.1 2307.12
     925  2309.3   941.4 2309.55   951.2  2309.2   961.1 2307.02   970.9 2308.12
    1138 2308.16  1278.8  2309.9  1367.3 2312.24  1426.3 2310.86  1488.5 2311.87
#Mann= 12 ,-1 , 0
       0     .04       0      50      .1       0  291.99     .04       0
  503.32    .045       0   527.6    .035       0  571.99     .04       0
  623.47     .06       0  729.68     .04       0  939.68     .06       0
 1139.68    .035       0 1149.68     .06       0 1439.68    .035       0
#XS Ineff= 4 ,-1
       0   497.5    2309   530.8  932.93    2307  932.93 1364.13 2312.26
 1364.13  1488.5    2307
Permanent Ineff=
       F       F       F       F
Bank Sta=503.32,527.6
XS Rating Curve= 0 ,0
Exp/Cntr=0.5,0.3

Type RM Length L Ch R = 1 ,89652   ,109.9,106.9,104.5
XS GIS Cut Line= 5
     2136934.871      207322.712     2137150.149      207472.018
     2137424.454      207619.587     2137502.579      207656.045
     2138328.927      207941.874
#Sta/Elev= 30
       0    2332    22.9 2331.01    81.9 2331.59   114.6 2330.65   176.8 2319.82
   196.5 2313.29   212.9 2311.16   271.8    2310   291.5 2307.97   307.9 2307.36
   376.7 2307.37   429.2 2308.52   494.8  2307.5   507.9  2305.9   514.4 2304.21
   530.8 2305.74   540.7  2308.7   579.8    2307   856.2 2306.14   905.3 2306.63
   915.1 2308.71   934.8 2309.31   941.3 2309.18   957.7 2305.99  1177.1 2308.67
    1236 2310.01  1252.4 2311.27  1350.7 2311.51  1429.3 2310.13  1534.1 2311.16
#Mann= 15 ,-1 , 0
       0     .04       0      70      .1       0     120     .04       0
     190      .1       0  291.99     .04       0  501.99    .035       0
   507.9    .045       0   530.8    .035       0  531.99     .04       0
  643.47     .06       0  749.68     .04       0  959.68     .06       0
 1039.68    .035       0 1169.68     .06       0 1349.68    .035       0
#XS Ineff= 4 ,-1
       0   497.5    2309   532.5  930.53    2307  930.53 1524.21 2313.48
 1524.21  1534.1    2307
Permanent Ineff=
       F       F       F       F
Bank Sta=507.9,530.8
XS Rating Curve= 0 ,0
Exp/Cntr=0.5,0.3

Type RM Length L Ch R = 1 ,89545   ,607.3,618.9,609.8
XS GIS Cut Line= 2
2136873.88909284207515.6270095252138311.64576691208067.152995771
#Sta/Elev= 30
       0 2314.92    10.9 2316.88    34.5 2316.34    48.5 2313.79   101.3 2311.12
   157.5 2312.91   322.8 2310.91   364.8 2309.74   385.9 2306.45   463.2 2306.85
   486.12305.364   501.8 2303.24  511.32 2305.39   522.9 2308.16   740.8 2304.45
   845.7 2304.55   860.3 2304.84   870.8 2307.84   888.9 2308.81   902.4 2308.47
   916.5 2303.74   923.5 2305.76   934.1 2305.95  1134.4 2306.93  1155.4 2308.49
  1169.5 2311.47  1306.5 2311.45  1323.2 2309.04  1373.3    2309  1539.9 2311.55
#Mann= 17 ,-1 , 0
       0      .1       0      30    .035       0     130     .04       0
     190     .08       0     340     .07       0     450    .035       0
     470     .08       0   486.1    .045       0  511.32     .08       0
     550     .06       0     740    .035       0     760     .07       0
     870     .06       0     970    .035       0    1020     .04       0
    1190     .07       0    1500    .035       0
#XS Ineff= 2 , 0
                          896.84         2312.35
Permanent Ineff=
       F       F
Bank Sta=486.1,511.32
XS Rating Curve= 0 ,0
Exp/Cntr(USF)=0,0
Exp/Cntr=0.3,0.1

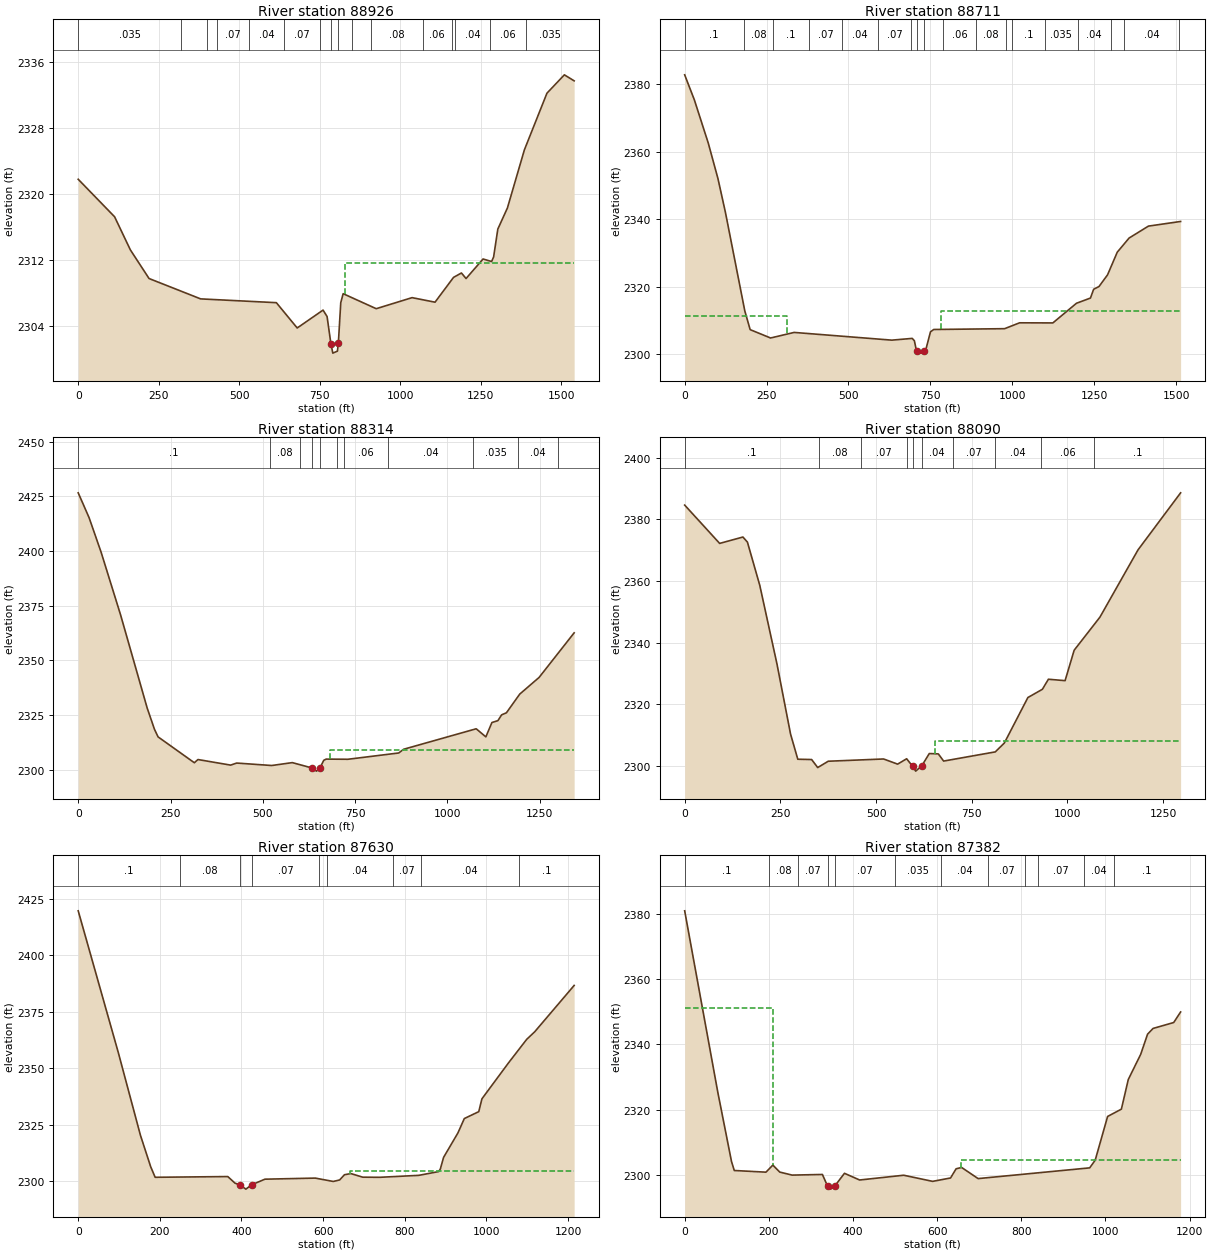
Type RM Length L Ch R = 1 ,88926   ,212.3,214.7,207.1
XS GIS Cut Line= 2
2136802.10045545207721.8097742952138218.90279877208325.380279294
#Sta/Elev= 30
       0 2321.75     113  2317.2   161.9 2313.19     220 2309.71   380.2 2307.24
   615.3 2306.78     680 2303.71   760.3 2305.88   772.8  2305.1   784.62301.812
   790.6 2300.66   804.9  2300.9   807.8 2301.88   815.3 2306.78   822.7 2307.87
   925.4 2306.05  1036.7 2307.39    1108 2306.84  1165.5 2309.85    1190 2310.38
  1204.3 2309.71  1257.2 2312.08  1283.6 2311.77  1289.9 2312.32    1303 2315.71
  1332.7 2318.26  1385.5 2325.32  1455.5 2332.19  1509.6 2334.42    1540 2333.69
#Mann= 16 ,-1 , 0
       0    .035       0     320     .07       0     400     .08       0
     430     .07       0     530     .04       0     640     .07       0
     750     .04       0   784.6    .045       0   807.8     .04       0
     850     .06       0     910     .08       0    1070     .06       0
    1160     .08       0    1170     .04       0    1280     .06       0
    1390    .035       0
#XS Ineff= 2 , 0
                          827.37         2311.57
Permanent Ineff=
       F       F
Bank Sta=784.6,807.8
XS Rating Curve= 0 ,0
Exp/Cntr(USF)=0,0
Exp/Cntr=0.3,0.1

Type RM Length L Ch R = 1 ,88711   ,392,397.3,403.5
XS GIS Cut Line= 2
     2136728.274      208001.965     2138183.093       208421.04
#Sta/Elev= 30
       0 2382.79    29.5 2375.38    72.1 2362.52   101.6 2352.01   124.5 2341.95
   183.5  2312.8   199.9 2307.22   262.2 2304.74   334.2 2306.39   632.5  2304.1
   694.7 2304.62   701.3 2303.91   707.8 2300.84   717.7 2300.25   730.8 2300.92
   737.3  2301.7   750.4 2306.57   760.3 2307.26   976.6  2307.5  1022.4 2309.24
    1124 2309.21  1196.1 2315.04  1238.7 2316.58  1248.5 2319.19  1264.9 2320.01
  1291.1 2323.49  1320.6 2330.19  1356.7 2334.38  1415.7 2337.92    1514  2339.3
#Mann= 18 ,-1 , 0
       0      .1       0     180     .08       0     270      .1       0
     380     .07       0     480     .04       0     590     .07       0
     690     .04       0   707.8    .045       0   730.8     .04       0
     790     .06       0     890     .08       0     980     .06       0
    1000      .1       0    1100    .035       0    1200     .04       0
    1300     .06       0    1340     .04       0    1510    .035       0
#XS Ineff= 2 , 0
          311.58 2311.29  781.17         2312.67
Permanent Ineff=
       F       F
Bank Sta=707.8,730.8
XS Rating Curve= 0 ,0
Exp/Cntr=0.3,0.1

Type RM Length L Ch R = 1 ,88314   ,221.6,224,221.7
XS GIS Cut Line= 2
     2136684.871      208192.938      2137818.51      208913.228
#Sta/Elev= 30
       0 2426.54    29.5 2415.17    62.2  2399.3   114.7 2370.76   186.7  2328.2
   206.4 2318.49   216.2 2314.97   314.5 2303.14   324.3  2304.6   412.8 2302.05
   429.1 2302.99   524.1 2301.87   579.8 2303.19   632.2 2300.79   645.4  2299.3
   655.2 2300.93     665 2304.25   671.6  2304.8   730.5 2304.72   868.1  2307.6
   881.2 2309.29  1077.8 2318.66    1104 2314.96  1120.4 2321.52  1136.7 2322.39
  1146.6 2325.02  1159.7 2325.98  1195.7 2334.51  1248.1 2342.13  1343.1 2362.53
#Mann= 11 ,-1 , 0
       0      .1       0     520     .08       0     600     .06       0
   632.2    .045       0   655.2     .06       0     700     .04       0
     720     .06       0     840     .04       0    1070    .035       0
    1190     .04       0    1300    .035       0
#XS Ineff= 2 , 0
                          683.09         2309.11
Permanent Ineff=
       F       F
Bank Sta=632.2,655.2
XS Rating Curve= 0 ,0
Exp/Cntr=0.3,0.1

Type RM Length L Ch R = 1 ,88090   ,461.9,460.6,457.4
XS GIS Cut Line= 3
2136613.40525547208373.6659196942137516.85500085208974.059737825
2137562.59929175209179.909046899
#Sta/Elev= 30
       0 2384.62    91.4 2372.19   152.1 2374.26   163.9 2372.62   196.1 2358.64
   241.1 2333.09   276.6 2310.35   295.5 2302.18   331.7 2302.08   347.5 2299.48
   375.1 2301.53   519.6 2302.26   556.3 2300.59   579.9 2302.33   595.7 2299.85
   603.5 2298.32   619.7 2300.09     639 2304.02   662.6 2303.91   676.5 2301.58
   811.4 2304.56   835.1 2307.44   896.6 2322.19   934.5 2324.87   950.2 2328.13
   993.8 2327.67  1017.5 2337.54  1084.8 2348.27  1184.4 2370.11  1295.6  2388.6
#Mann= 10 ,-1 , 0
       0      .1       0     350     .08       0     460     .07       0
     580     .04       0   595.7    .045       0   619.7     .04       0
     700     .07       0     810     .04       0     930     .06       0
    1070      .1       0
#XS Ineff= 2 , 0
                          653.95         2308.06
Permanent Ineff=
       F       F
Bank Sta=595.7,619.7
XS Rating Curve= 0 ,0
Exp/Cntr(USF)=0,0
Exp/Cntr=0.3,0.1

Type RM Length L Ch R = 1 ,87630   ,245.6,247.6,245.8
XS GIS Cut Line= 2
2136487.60845548208545.2070105892137505.41892812209208.499228714
#Sta/Elev= 30
       0  2419.8    98.4 2356.83   152.4  2320.3   177.6 2306.29   188.5 2301.64
   366.4 2301.96   383.9 2299.07   396.3 2298.19   410.8 2296.39   425.1 2298.32
   457.4  2300.8   580.7 2301.28   624.8 2299.79   640.5 2300.46   652.2 2302.77
   667.9 2303.29   696.9 2301.69   738.4 2301.63   834.4  2302.5   883.3 2304.18
   887.2 2305.38     895 2310.45   930.3 2321.35   945.8 2327.68   981.2 2330.74
     989 2336.44  1053.8  2352.3  1098.7 2362.82  1118.2 2366.15  1214.9 2386.71
#Mann= 9 ,-1 , 0
       0      .1       0     250     .08       0   396.3    .045       0
   425.1     .07       0     590    .035       0     610     .04       0
     770     .07       0     840     .04       0    1080      .1       0
#XS Ineff= 2 , 0
                          666.84         2304.56
Permanent Ineff=
       F       F
Bank Sta=396.3,425.1
XS Rating Curve= 0 ,0
Exp/Cntr(USF)=0,0
Exp/Cntr=0.3,0.1

Type RM Length L Ch R = 1 ,87382   ,286,289.7,288.3
XS GIS Cut Line= 2
     2136363.048      208766.133     2137394.031      209337.707
#Sta/Elev= 30
       0 2380.92    78.6  2325.4   111.3 2304.08   117.9 2301.31   193.2  2300.8
   209.6 2302.97   225.9 2300.83   255.4  2299.9   327.4 2300.09   339.6 2296.52
   347.1  2295.6   356.9 2296.57   379.8 2300.45   415.9  2298.4   520.6 2299.86
   589.4 2297.98     632 2299.02   645.1 2301.83   658.2 2302.25   697.5 2298.83
   962.7 2302.12   975.8 2304.49  1005.3 2317.88    1038 2320.12  1054.4  2329.2
  1083.9 2336.92  1100.2 2343.09  1113.3 2344.86  1162.4 2346.68  1178.8 2349.91
#Mann= 12 ,-1 , 0
       0      .1       0     200     .08       0     270     .07       0
   339.6    .045       0   356.9     .07       0     500    .035       0
     610     .04       0     720     .07       0     810    .035       0
     840     .07       0     950     .04       0    1020      .1       0
#XS Ineff= 2 , 0
          210.34 2351.17  656.84         2304.68
Permanent Ineff=
       F       F
Bank Sta=339.6,356.9
XS Rating Curve= 0 ,0
Exp/Cntr=0.3,0.1