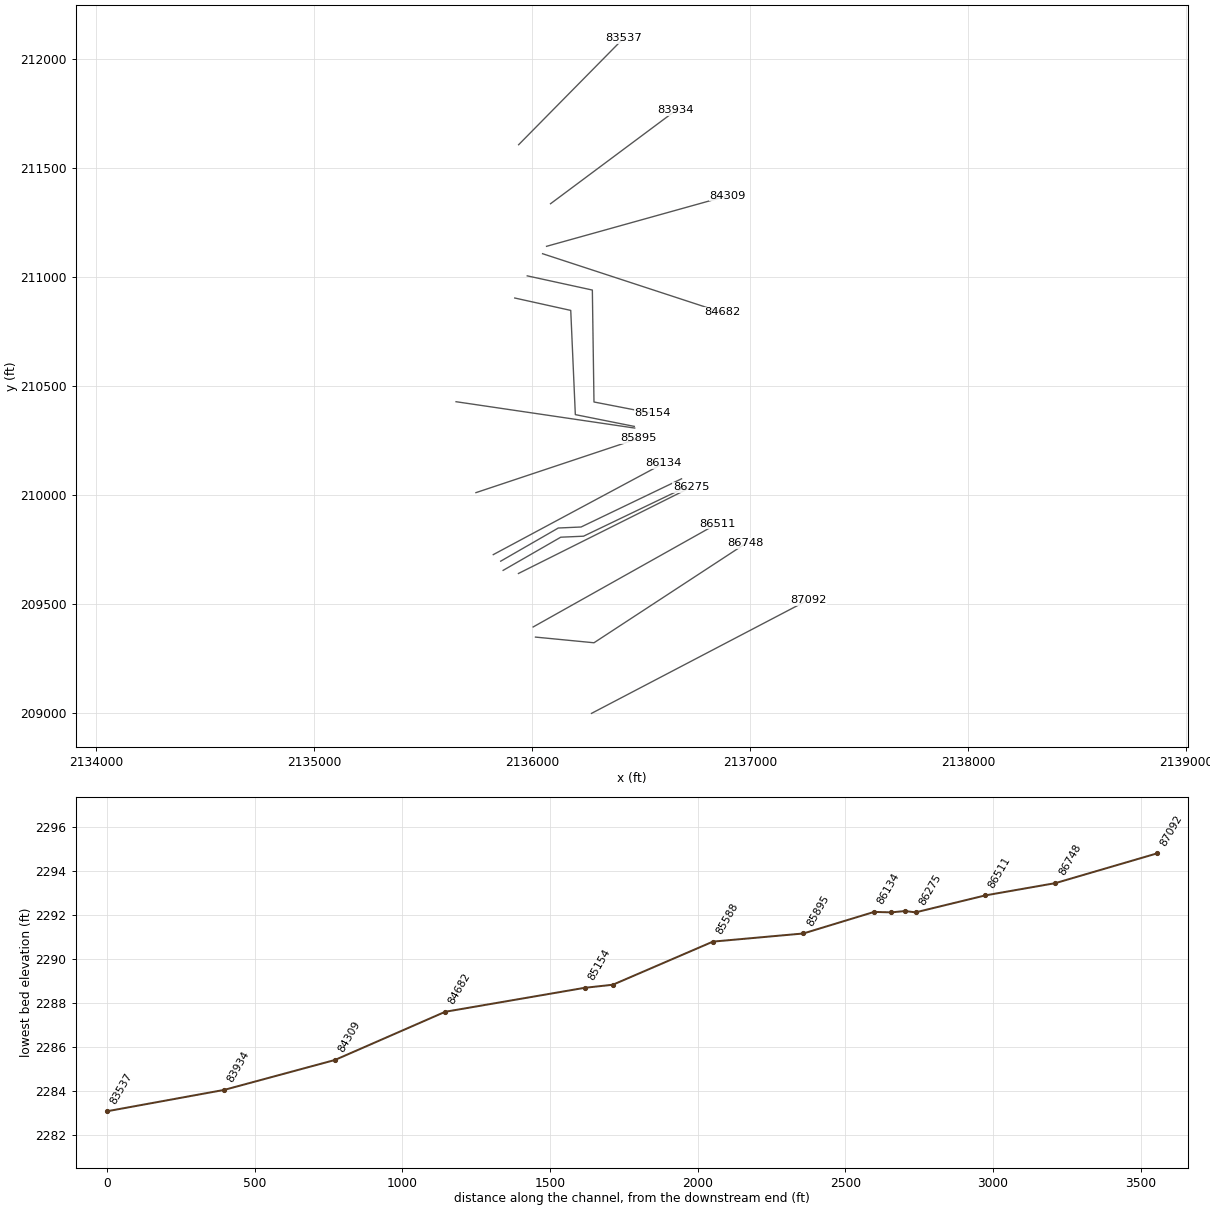
HEC-RAS study SECONDCK.prj: SECONDCK

--- SECONDCK.g01 (geometry) --- (continued)

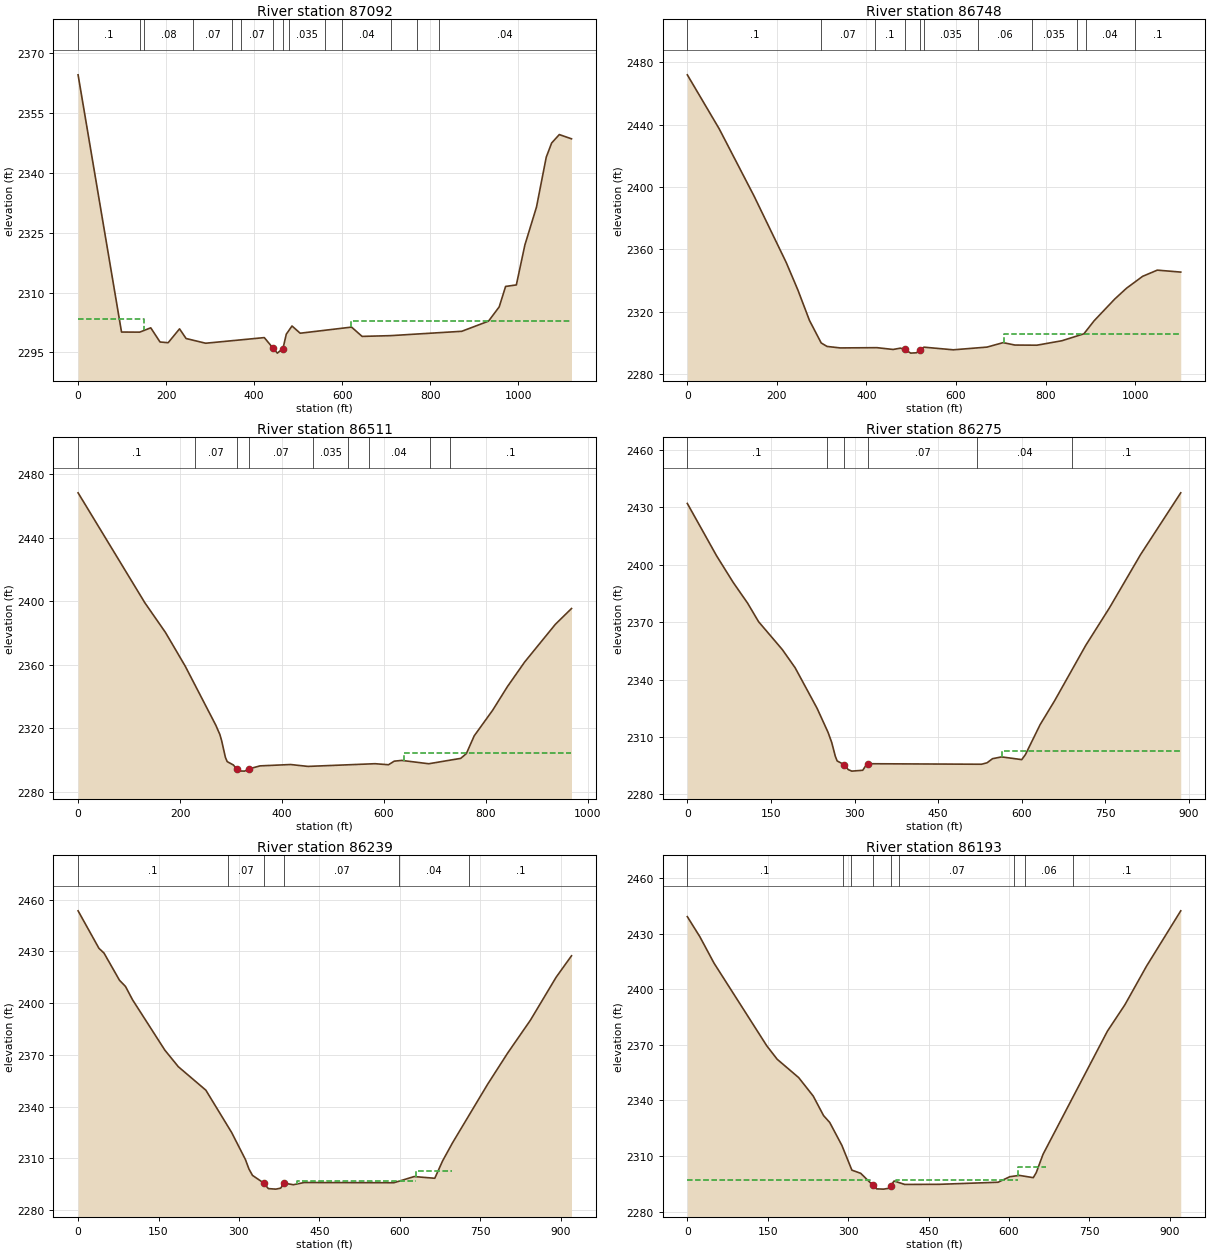
Type RM Length L Ch R = 1 ,87092   ,339.6,343.8,342.5
XS GIS Cut Line= 2
2136272.03848459 208998.075490552137265.26140087209517.844995961
#Sta/Elev= 30
       0 2364.54    98.7 2300.09     140 2300.07   165.1 2301.15   186.2  2297.6
   204.6 2297.42   230.5 2300.89   245.4 2298.47   289.8 2297.29   423.1  2298.7
  442.94 2296.05   452.7 2294.81   465.5 2295.96     473 2299.55     486 2301.61
   504.6  2299.8   621.3 2301.33   645.3    2299     710 2299.19   871.7 2300.28
   932.5 2302.82   956.8 2306.41   971.3 2311.52   995.7  2311.9  1015.1 2321.91
  1041.5 2331.42  1063.6  2343.9  1075.9 2347.46  1093.3 2349.57    1121 2348.51
#Mann= 14 ,-1 , 0
       0      .1       0     140     .07       0     150     .08       0
     260     .07       0     350    .035       0     370     .07       0
  442.94    .045       0   465.5     .07       0     480    .035       0
     560     .06       0     600     .04       0     710    .035       0
     770     .07       0     820     .04       0
#XS Ineff= 2 , 0
             150 2303.39  620.53          2302.9
Permanent Ineff=
       F       F
Bank Sta=442.94,465.5
XS Rating Curve= 0 ,0
Exp/Cntr(USF)=0,0
Exp/Cntr=0.3,0.1

Type RM Length L Ch R = 1 ,86748   ,234.6,237.9,236.5
XS GIS Cut Line= 3
     2136015.166      209347.886     2136283.395      209321.844
     2136979.968      209777.811
#Sta/Elev= 30
       0    2472    71.4 2437.25   149.4 2394.02   220.8 2351.64   246.8 2334.05
   272.8 2314.44     299 2299.98   312.1 2297.75   341.6  2296.8   423.5 2296.96
   459.6 2295.81     476 2296.67   485.8 2295.79   498.9 2293.46     512 2293.69
   518.6  2295.6   528.4 2297.28     594 2295.59   669.4 2297.33   705.4 2300.19
   731.6 2298.64   780.8 2298.55   836.5  2301.4   885.7 2305.85   908.6 2314.23
   954.5 2328.13   980.8 2335.08  1016.8 2342.72  1049.6  2346.7    1102 2345.45
#Mann= 11 ,-1 , 0
       0      .1       0  299.49     .07       0  419.49      .1       0
   485.8    .045       0   518.6     .07       0  529.49    .035       0
  649.49     .06       0  769.49    .035       0  869.49      .1       0
  889.49     .04       0  999.49      .1       0
#XS Ineff= 2 , 0
                          707.37         2305.44
Permanent Ineff=
       F       F
Bank Sta=485.8,518.6
XS Rating Curve= 0 ,0
Exp/Cntr=0.3,0.1

Type RM Length L Ch R = 1 ,86511   ,236.2,236,236.4
XS GIS Cut Line= 2
2136004.43438279209394.3354105172136848.41654999209867.788821386
#Sta/Elev= 30
       0 2468.13     131 2398.88   171.4  2380.2     210 2359.08   270.2 2321.76
   278.1 2315.93   281.5 2312.15     289 2301.48   292.5 2298.87   304.6 2296.77
   310.8  2294.4   315.3 2293.01   326.6  2292.9   335.9 2294.37   356.7  2296.2
   416.9 2297.06   450.8 2295.87   582.4 2297.57   608.8 2296.92     620 2299.17
   634.7 2299.65   687.8 2297.55   750.4 2300.93   761.5 2303.94   776.9 2315.11
   813.1 2331.25     842  2346.1   875.7 2361.55     936 2385.32   967.7 2395.28
#Mann= 9 ,-1 , 0
       0      .1       0     230     .07       0   310.8    .045       0
   335.9     .07       0     460    .035       0     530     .07       0
     570     .04       0     690    .035       0     730      .1       0
#XS Ineff= 2 , 0
                          639.47         2304.44
Permanent Ineff=
       F       F
Bank Sta=310.8,335.9
XS Rating Curve= 0 ,0
Exp/Cntr(USF)=0,0
Exp/Cntr=0.3,0.1

Type RM Length L Ch R = 1 ,86275   ,49.5,35.9,24.8
XS GIS Cut Line= 2
     2135937.041      209639.552     2136728.708      210035.386
#Sta/Elev= 30
       0 2432.11    52.4 2404.78      82 2390.94   108.2 2379.94   127.8 2370.28
   170.5 2355.66   193.4 2346.18   232.8 2324.96   252.4 2312.43     259 2307.14
   265.5 2299.84   268.8 2297.44   281.9 2295.45   288.5 2292.95     295 2292.13
   314.7 2292.58   321.3 2295.54   324.5    2296   527.8 2295.73   537.6 2296.48
   547.5 2298.64   563.8 2299.57   599.9 2298.15   606.5 2300.79   632.7 2316.36
   658.9 2328.97   714.6 2357.86   757.3 2377.56     813 2405.36   885.1 2437.67
#Mann= 6 ,-1 , 0
       0      .1       0     250     .07       0   281.9    .045       0
   324.5     .07       0     520     .04       0     690      .1       0
#XS Ineff= 2 , 0
                          564.26         2302.84
Permanent Ineff=
       F       F
Bank Sta=281.9,324.5
XS Rating Curve= 0 ,0
Exp/Cntr=0.5,0.3

Type RM Length L Ch R = 1 ,86239   ,43.8,45.6,45.8
XS GIS Cut Line= 4
2135866.87671295209653.9011868432136131.00674206209805.929517552
2136235.43024194209810.5364366642136696.12215318210031.668554058
#Sta/Elev= 30
       0 2453.47    38.9 2431.75    48.3 2429.01    77.3 2413.21    88.4 2409.66
   101.5 2401.96   161.8 2372.76     187 2363.12   238.3 2349.54   286.4 2325.02
   312.1 2309.35   318.7 2303.85   325.3 2300.15   346.5 2295.67   354.8 2292.49
   368.8 2292.19   377.8 2292.76   384.5 2295.64   401.5 2294.74   421.7 2296.02
   589.1 2295.89   626.8 2299.47   665.3 2298.48     680 2308.63   698.3 2318.97
   763.6 2352.84   801.2 2371.03   843.9  2390.2   891.5 2414.93920.2979 2427.41
#Mann= 6 ,-1 , 0
       0      .1       0     280     .07       0   346.5    .045       0
   384.5     .07       0  599.28     .04       0  729.28      .1       0
#XS Ineff= 4 ,-1
       0   332.5    2297   407.5  631.09    2297  631.09  697.66 2302.98
  697.66920.2979    2297
Permanent Ineff=
       F       F       F       F
Bank Sta=346.5,384.5
XS Rating Curve= 0 ,0
Exp/Cntr(USF)=0,0
Exp/Cntr=0.5,0.3

Type RM Length L Ch R = 1 ,86193   ,46.9,58.8,71
XS GIS Cut Line= 4
 2135855.6673403209696.0606364992136119.79736941209848.088967207
2136224.22086929 209852.695886322136684.91278053210073.828003714
#Sta/Elev= 30
       0 2439.21    23.4 2428.35    49.9 2414.06   148.3 2369.44   167.6 2362.23
   207.7 2352.32   234.9 2342.33   254.1 2331.82   265.6 2328.11   288.3 2315.72
   306.9 2302.39   323.4 2300.66   346.3 2294.16   352.9 2292.27     366 2292.13
   375.9 2292.59   379.2 2294.04   385.7 2296.51   405.5 2294.66   470.5 2294.73
   579.7 2295.85   601.6 2298.84   619.2 2299.54   645.2 2298.32   650.7 2300.97
   663.4 2310.89   783.5 2377.39   816.3 2391.72   856.3 2412.41920.2979 2442.35
#Mann= 9 ,-1 , 0
       0      .1       0     290     .07       0  304.76      .1       0
   346.3    .045       0   379.2      .1       0  394.76     .07       0
  609.28     .04       0  629.28     .06       0  719.28      .1       0
#XS Ineff= 4 ,-1
       0   340.8    2297   389.2  617.11    2297  617.11  668.42 2304.31
  668.42920.2979    2297
Permanent Ineff=
       F       F       F       F
Bank Sta=346.3,379.2
XS Rating Curve= 0 ,0
Exp/Cntr(USF)=0,0
Exp/Cntr=0.5,0.3

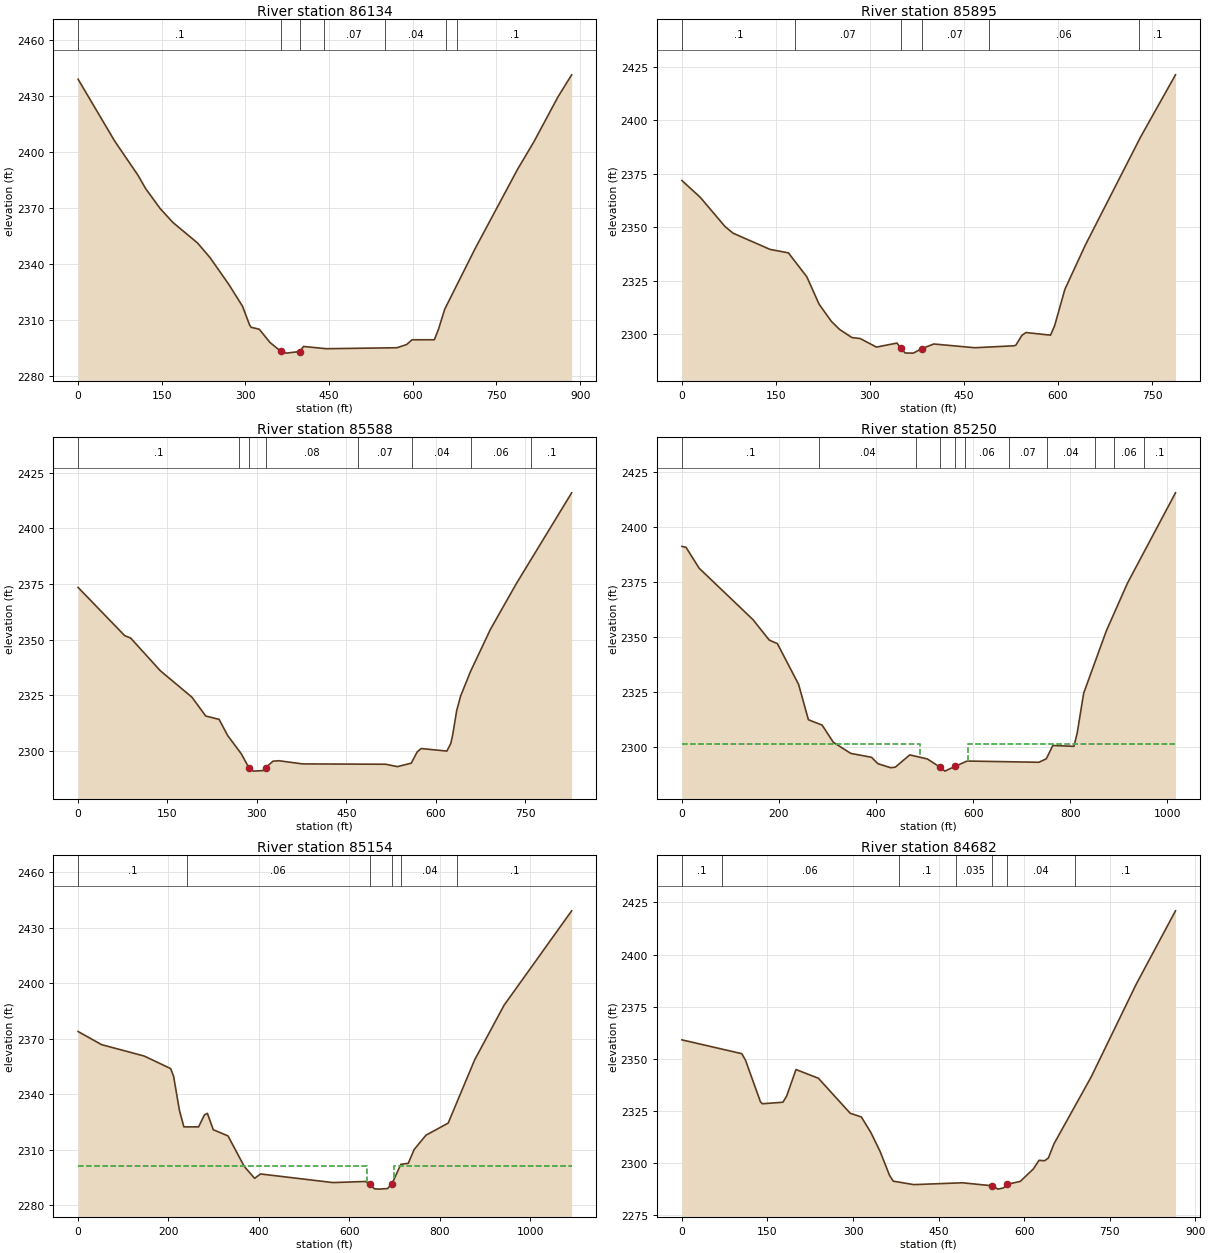
Type RM Length L Ch R = 1 ,86134   ,241.1,239.7,232.6
XS GIS Cut Line= 2
2135821.59140123209726.0207504472136601.35511766210144.056003238
#Sta/Elev= 30
       0 2439.13    65.7  2405.9   107.3 2387.63   121.2  2380.4   147.2 2369.71
   169.8 2362.31   214.3 2351.21   236.6 2343.38   270.1 2329.06   294.8  2317.3
   307.3 2307.36   310.2 2306.02   324.8 2304.97   344.1 2297.84   363.2 2293.18
   373.2 2292.15   397.5 2293.02   404.1 2295.72   445.1 2294.52   571.6 2295.04
   588.9 2296.75   598.6 2299.31   638.6 2299.32   646.1 2305.01   657.2 2315.69
   711.4 2348.05   787.5 2390.63   817.3 2405.67   860.3 2429.69884.7513 2441.49
#Mann= 7 ,-1 , 0
       0      .1       0   363.2    .045       0   397.5      .1       0
     440     .07       0     550     .04       0     660     .06       0
     680      .1       0
Bank Sta=363.2,397.5
XS Rating Curve= 0 ,0
Exp/Cntr(USF)=0,0
Exp/Cntr=0.3,0.1

Type RM Length L Ch R = 1 ,85895   ,313.1,306.1,291.5
XS GIS Cut Line= 2
     2135742.095      210010.276     2136489.125      210259.344
#Sta/Elev= 30
       0  2371.8    29.4 2363.94    68.6 2350.37    81.7  2347.2   140.5 2339.65
   169.9 2338.02   199.3 2326.83   218.9 2314.01   238.5    2306   251.6 2302.23
   271.2 2298.45   284.3    2298   310.4 2293.99   343.1 2295.87   349.6 2293.37
   356.2 2291.23   369.2 2291.17   382.3 2293.22   401.9 2295.44   467.2 2293.69
   529.3 2294.59   532.6 2294.81   542.4 2299.46   548.9 2300.79   588.1 2299.56
   594.7 2304.01     611 2320.97   643.7 2341.69   731.9 2392.21   787.5 2421.22
#Mann= 6 ,-1 , 0
       0      .1       0     180     .07       0   349.6    .045       0
   382.3     .07       0     490     .06       0     730      .1       0
Bank Sta=349.6,382.3
XS Rating Curve= 0 ,0
Exp/Cntr=0.3,0.1

Type RM Length L Ch R = 1 ,85588   ,363.7,338.9,292.1
XS GIS Cut Line= 2
2135650.88657352210427.2390087612136470.21963221210306.353803382
#Sta/Elev= 30
       0 2373.48    78.2 2351.77    88.2  2350.7   137.9    2336     191 2324.08
   214.2  2315.6   236.6  2314.1     251 2306.82   273.9 2298.58   287.2 2292.04
   293.8  2290.8   310.4 2291.04   314.6 2292.27   326.9 2295.27   336.9 2295.48
   376.7 2294.05     516  2293.9   535.9 2292.83   559.1 2294.39     569 2299.43
   575.7 2300.97   618.8 2299.82   625.4 2303.23   628.7 2307.28   635.3 2318.05
     642 2324.67   658.5 2335.64   691.7  2354.5   734.9 2374.96   828.2 2416.05
#Mann= 8 ,-1 , 0
       0      .1       0     270     .08       0   287.2    .045       0
   314.6     .08       0     470     .07       0     560     .04       0
     660     .06       0     760      .1       0
Bank Sta=287.2,314.6
XS Rating Curve= 0 ,0
Exp/Cntr(USF)=0,0
Exp/Cntr=0.5,0.3

Type RM Length L Ch R = 1 ,85250   ,98.2,95.5,94.5
XS GIS Cut Line= 4
     2135920.072      210902.811     2136176.849      210845.903
2136197.86924659210368.033812784     2136468.291      210314.031
#Sta/Elev= 30
       0 2391.06     8.5 2390.63    35.4 2381.17   146.3 2357.78   179.9 2348.47
   196.7 2346.84   240.4 2328.31   260.6 2312.23   288.9 2309.78   311.9 2301.97
     348 2296.91   390.7 2295.13   403.8 2292.23   430.1  2290.4   439.7 2290.65
   469.5 2296.22   505.7 2294.39   531.9 2290.64   541.8 2288.84   562.3 2290.95
   587.7 2293.43   735.5 2292.87   750.9 2294.45   764.3 2300.51   807.8 2300.12
   814.5 2306.12   827.9 2324.29   874.7 2352.71   918.2 2374.38  1017.1 2415.44
#Mann= 11 ,-1 , 0
       0      .1       0  283.01     .04       0  483.01     .07       0
   531.9    .045       0   562.3     .07       0  583.01     .06       0
  673.01     .07       0  751.34     .04       0  851.34      .1       0
  891.34     .06       0  951.34      .1       0
#XS Ineff= 2 , 0
             490    2301     590            2301
Permanent Ineff=
       F       F
Bank Sta=531.9,562.3
XS Rating Curve= 0 ,0
Exp/Cntr=0.5,0.3

Type RM Length L Ch R = 1 ,85154   ,436.5,472.4,509.6
XS GIS Cut Line= 4
     2135977.364      211004.374     2136275.921      210939.256
     2136283.395      210426.011     2136551.625      210373.927
#Sta/Elev= 30
       0 2373.92      52 2366.82   146.3 2360.65   204.8 2353.87   211.3 2349.75
   224.3 2331.23   234.1 2322.37   266.6 2322.36   279.6 2328.84   286.1 2329.68
   299.1 2320.82   331.7 2317.47   367.7 2300.97   390.6 2294.53   403.7  2296.9
   563.9 2292.24   635.8 2292.84   645.6 2291.37   655.4 2288.92   665.2  2288.7
   684.8 2289.02   694.6 2291.63   714.2 2302.12   730.6 2302.65   743.7 2310.16
   769.8 2317.86   818.9  2324.4   877.4 2358.54   942.5  2388.1  1092.1 2439.17
#Mann= 6 ,-1 , 0
       0      .1       0     240     .06       0   645.6    .045       0
   694.6     .06       0  715.58     .04       0  838.88      .1       0
#XS Ineff= 2 , 0
             640    2301     700            2301
Permanent Ineff=
       F       F
Bank Sta=645.6,694.6
XS Rating Curve= 0 ,0
Exp/Cntr=0.5,0.3

Type RM Length L Ch R = 1 ,84682   ,359.4,373.2,385.7
XS GIS Cut Line= 2
     2136047.677      211105.936     2136870.201      210836.601
#Sta/Elev= 30
       0 2359.11   104.9  2352.5   111.5 2349.36   137.7 2329.43     141 2328.51
     177 2329.23   183.6 2332.16     200  2344.9   239.3 2340.72   295.1 2323.96
   314.7 2322.16   331.1 2314.84   347.5 2305.67   363.9 2294.31   370.5 2291.43
   406.5 2289.77   491.8 2290.65   544.2 2289.21     554 2287.61   563.9 2288.17
   570.4 2289.93   593.4 2291.32   616.3  2297.3   626.2 2301.41     636 2301.21
   642.6 2302.52   652.4 2309.29     718 2341.54   796.6 2385.75   865.5 2420.92
#Mann= 7 ,-1 , 0
       0      .1       0      70     .06       0     380      .1       0
     480    .035       0   544.2    .045       0   570.4     .04       0
     690      .1       0
Bank Sta=544.2,570.4
XS Rating Curve= 0 ,0
Exp/Cntr=0.3,0.1

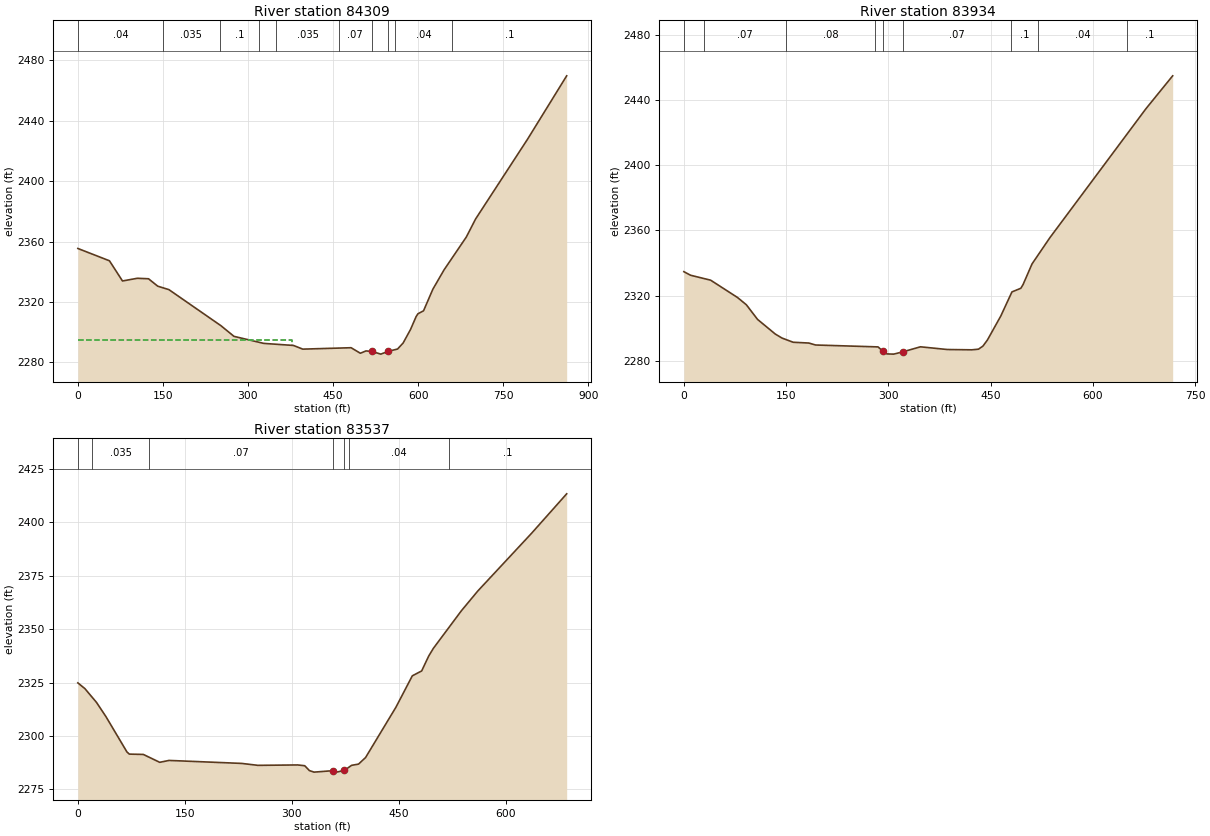
Type RM Length L Ch R = 1 ,84309   ,362.1,375,379.2
XS GIS Cut Line= 2
     2136065.906       211139.79     2136896.243      211371.323
#Sta/Elev= 30
       0  2355.4    55.7 2347.25    78.7 2333.87   104.9 2335.66   124.6 2335.33
   140.9 2330.42   160.6 2328.13   252.4 2304.23   275.3 2297.19   327.8 2292.53
   380.2 2291.17   396.6 2288.73   481.8 2289.66   498.2 2286.01     508 2287.53
   517.9 2287.29   534.2 2285.42   547.4 2287.26   563.8 2288.81   573.6 2292.78
   586.7 2301.79   596.5 2310.28   599.8 2312.18   609.6 2314.11     626  2328.4
   645.7 2341.19     685 2362.96   701.4 2374.94   793.2 2427.89     862 2469.75
#Mann= 10 ,-1 , 0
       0     .04       0     150    .035       0     250      .1       0
     320     .07       0     350    .035       0     460     .07       0
   517.9    .045       0   547.4     .07       0     560     .04       0
     660      .1       0
#XS Ineff= 2 , 0
          378.42 2294.68
Permanent Ineff=
       F       F
Bank Sta=517.9,547.4
XS Rating Curve= 0 ,0
Exp/Cntr=0.3,0.1

Type RM Length L Ch R = 1 ,83934   ,393.5,396.4,394.1
XS GIS Cut Line= 2
     2136084.135      211335.103       2136659.2      211763.516
#Sta/Elev= 30
       0 2334.64     9.8 2332.45    39.3 2329.42    78.6 2318.83    91.7 2314.34
   108.1 2305.37   134.2 2296.35   144.1  2293.9   160.4 2291.34   183.4 2290.86
   193.2 2289.66   284.9 2288.49   292.1 2285.78     298 2284.19   307.8 2284.06
   320.9 2285.42   347.1 2288.55   386.4 2286.89   422.4  2286.7   432.2  2287.1
   438.8    2289   445.3  2292.7     465 2307.48   481.3 2322.21   494.4 2324.47
   497.7  2326.8   510.8 2339.41     537  2355.5   677.8 2434.55   717.1 2454.77
#Mann= 9 ,-1 , 0
       0    .035       0      30     .07       0     150     .08       0
     280     .07       0   292.1    .045       0   320.9     .07       0
     480      .1       0     520     .04       0     650      .1       0
Bank Sta=292.1,320.9
XS Rating Curve= 0 ,0
Exp/Cntr=0.3,0.1

Type RM Length L Ch R = 1 ,83537   ,398.2,398.5,397.6
XS GIS Cut Line= 2
     2135937.909      211605.698     2136418.812      212093.545
#Sta/Elev= 30
       0 2324.84     9.8 2322.17    26.2 2315.67    39.3 2309.09    68.8 2292.52
    72.1 2291.52    91.8 2291.36   114.7 2287.68   127.8 2288.56   229.4 2287.17
   252.4 2286.26   308.1 2286.45   317.9 2286.08   324.5 2283.81     331 2283.09
   356.9 2283.75   363.8 2283.18   373.6  2283.9   383.5 2286.26   393.3 2286.84
   403.2 2289.92   445.8 2313.49   468.7 2328.14   481.8 2330.42   491.6 2337.34
   498.2 2340.99   537.5 2358.59   560.5 2367.82   635.9 2394.84     685 2413.26
#Mann= 7 ,-1 , 0
       0     .04       0      20    .035       0     100     .07       0
   356.9    .045       0   373.6     .07       0     380     .04       0
     520      .1       0
Bank Sta=356.9,373.6
XS Rating Curve= 0 ,0
Exp/Cntr=0.3,0.1