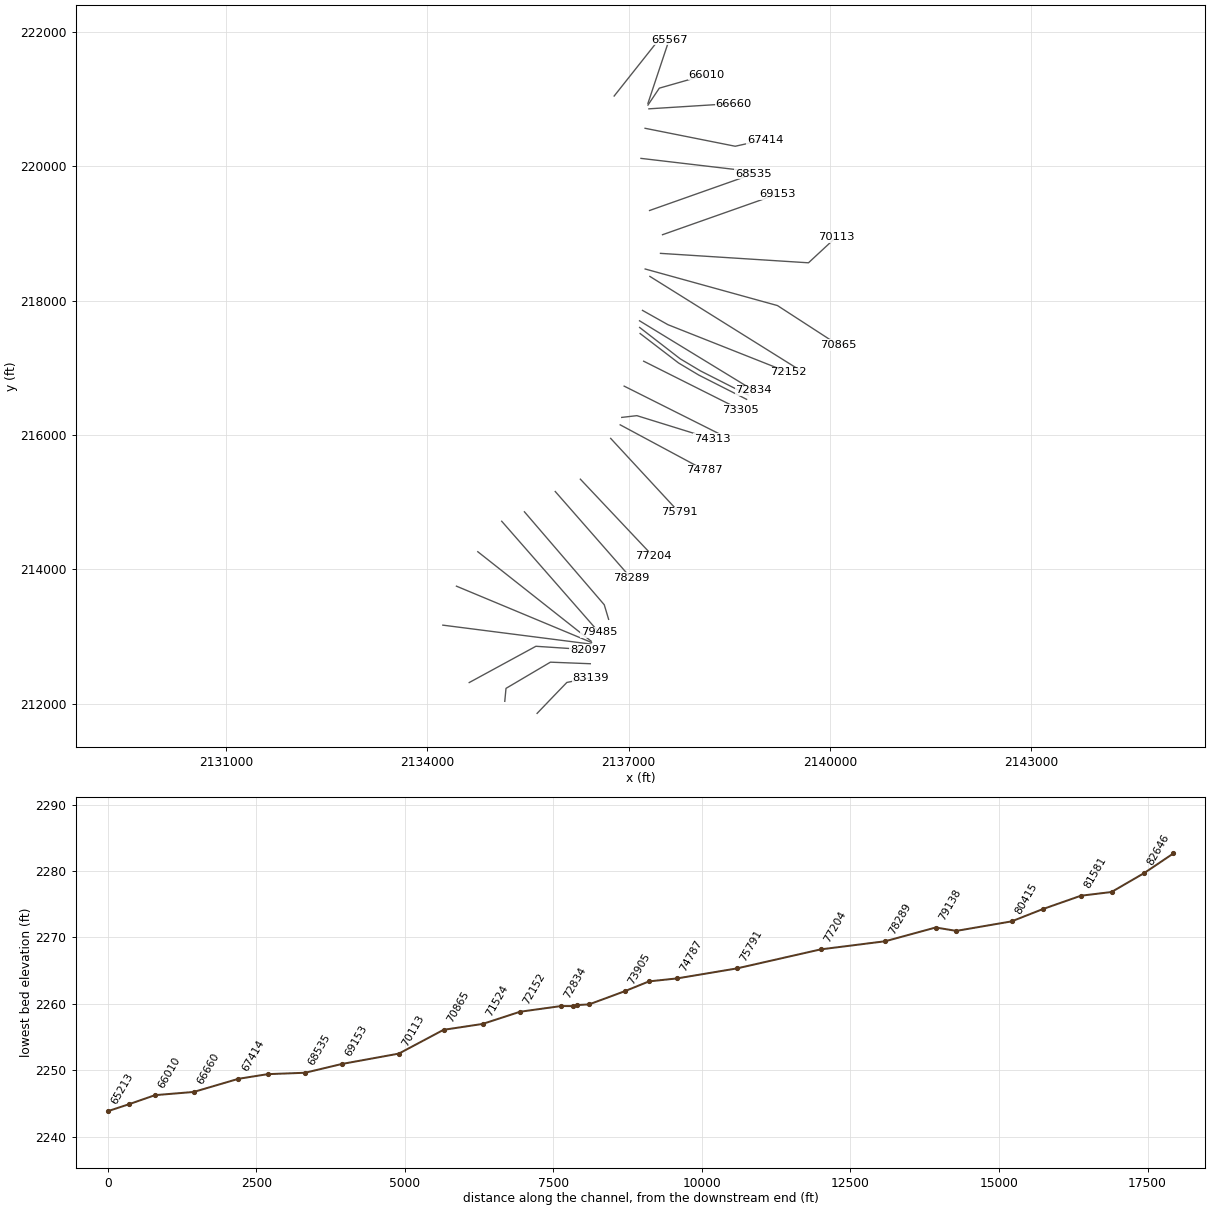
HEC-RAS study SECONDCK.prj: SECONDCK

--- SECONDCK.g01 (geometry) --- (continued)

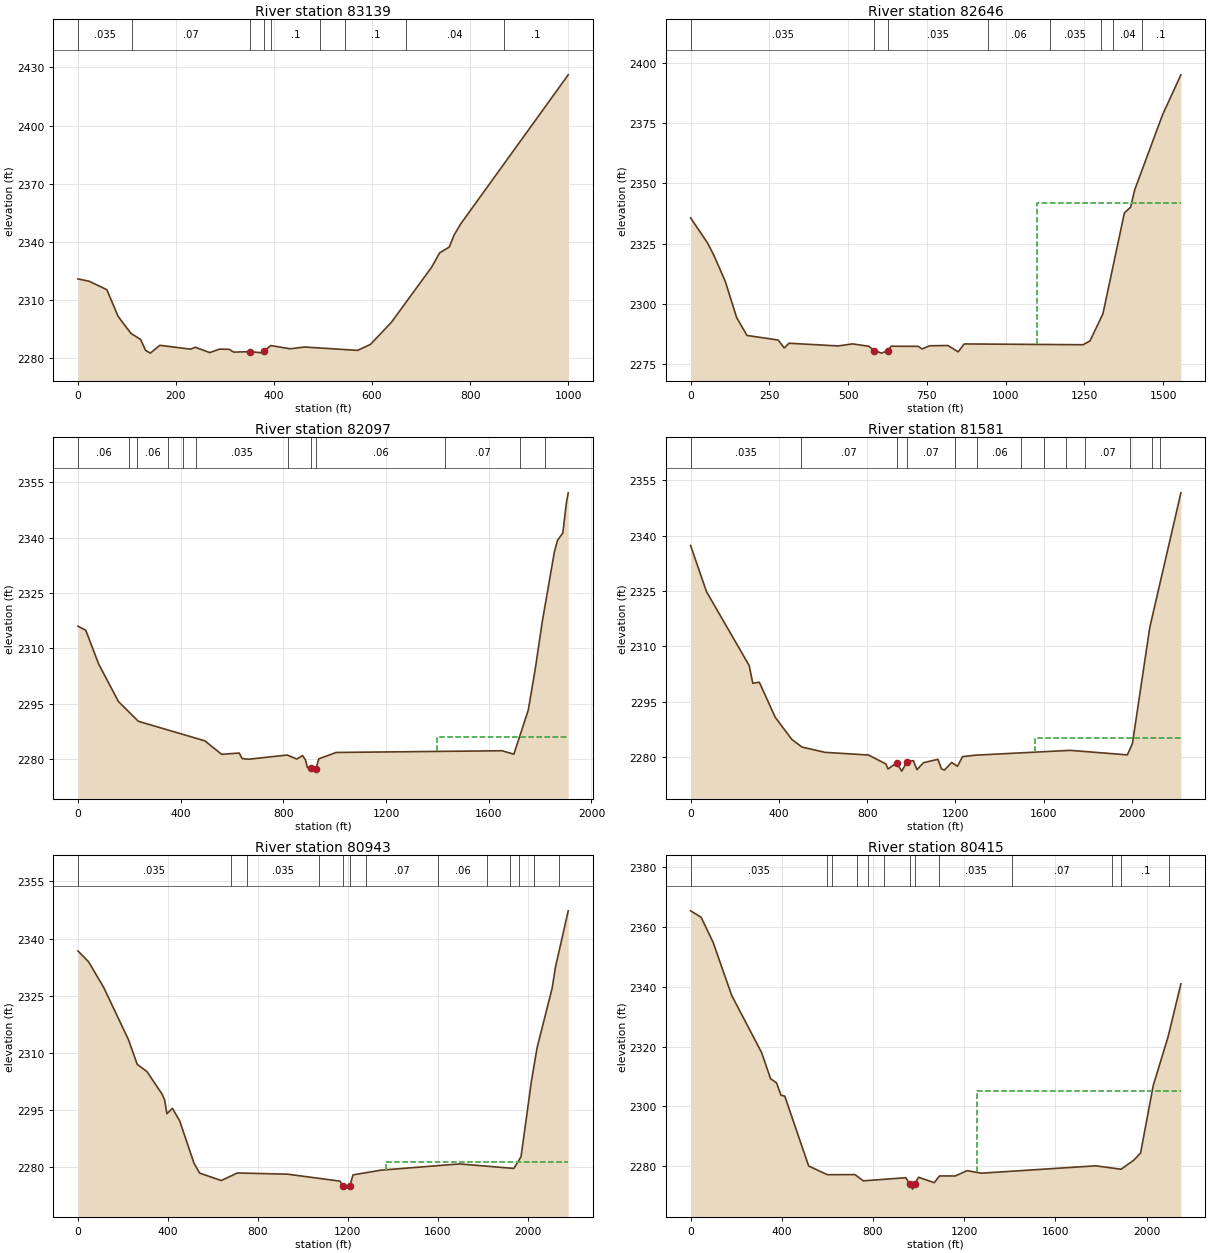
Type RM Length L Ch R = 1 ,83139   ,504.7,492.6,481.8
XS GIS Cut Line= 4
     2135636.417      211853.076     2135888.386      212115.768
     2136079.684      212313.848     2136433.569      212384.344
#Sta/Elev= 30
       0 2320.93      23 2319.71      59 2315.36      82 2301.58   108.2 2292.81
   127.9  2289.7   137.7 2284.15   147.6 2282.64   167.2 2286.68   229.6 2284.68
   239.4 2285.69   268.9 2282.92   288.6 2284.69   308.2 2284.62   318.1 2283.16
   350.9 2283.41   373.8 2282.85   380.4 2283.86   393.5 2286.55   432.8 2284.88
   462.4 2285.79   570.5 2284.06   596.8 2287.15   639.4 2298.52   721.4 2326.92
   737.8 2334.33   757.5 2337.36   767.3  2343.5   780.4 2349.13  1000.2 2426.19
#Mann= 9 ,-1 , 0
       0    .035       0     110     .07       0   350.9    .045       0
   380.4     .07       0     394      .1       0     494     .07       0
     544      .1       0  669.37     .04       0  869.37      .1       0
Bank Sta=350.9,380.4
XS Rating Curve= 0 ,0
Exp/Cntr=0.3,0.1

Type RM Length L Ch R = 1 ,82646   ,534,549.6,542.8
XS GIS Cut Line= 4
     2135154.923      212032.781     2135173.152       212225.49
2135834.60870281212615.8770975172136429.16623273212592.556690927
#Sta/Elev= 30
       0 2335.75    53.9 2325.32    73.7 2320.27   109.9 2309.51   146.2 2294.43
   179.1 2287.01   278.1 2285.11   297.2 2281.83   312.4 2283.78   468.6 2282.66
   514.3 2283.51   565.5 2282.53   583.6 2280.71   605.8 2279.68     6262280.628
   636.5 2282.54   722.6 2282.49   735.3  2281.4   758.5 2282.72   817.2 2282.84
   849.7 2280.19   868.6 2283.49    1246 2283.16    1268 2284.73  1309.1 2295.97
  1377.3  2337.8    1397 2340.17  1410.1  2347.4  1498.6 2378.52  1556.7 2395.04
#Mann= 8 ,-1 , 0
       0    .035       0   583.6    .045       0     626    .035       0
  943.57     .06       0 1141.64    .035       0 1301.64      .1       0
 1341.64     .04       0 1431.64      .1       0
#XS Ineff= 2 , 0
                         1099.62         2341.73
Permanent Ineff=
       F       F
Bank Sta=583.6,626
XS Rating Curve= 0 ,0
Exp/Cntr=0.3,0.1

Type RM Length L Ch R = 1 ,82097   ,515.9,515.6,449.1
XS GIS Cut Line= 3
  2134625.244012212312.2493666342135618.46692828212852.603802952
2136395.54807003212801.141475683
#Sta/Elev= 30
       0 2316.03    30.6 2314.93    80.7 2305.79   158.1 2295.62   235.5  2290.3
   494.4 2285.02   559.7 2281.38   628.2 2281.72   639.5 2280.24   663.8 2280.04
     815 2281.18   852.5  2280.1   874.7 2281.04   886.2 2279.86   893.7 2277.78
     908 2277.63   919.6 2276.83     927 2277.51   938.2 2280.15  1005.5 2281.88
  1651.7 2282.34  1697.8 2281.41  1753.7 2293.29  1781.4 2304.58  1809.1 2317.54
  1855.6 2336.12  1867.7 2339.24  1888.5 2341.22  1901.6    2349  1909.5 2352.08
#Mann= 12 ,-1 , 0
       0     .06       0     200     .04       0     230     .06       0
     350     .04       0     410     .06       0     460    .035       0
     820     .07       0     908    .045       0     927     .06       0
  1430.7     .07       0  1720.7    .035       0  1820.7     .04       0
#XS Ineff= 2 , 0
                            1400         2286.01
Permanent Ineff=
       F       F
Bank Sta=908,927
XS Rating Curve= 0 ,0
Exp/Cntr(USF)=0,0
Exp/Cntr=0.3,0.1

Type RM Length L Ch R = 1 ,81581   ,641.7,637.7,546.2
XS GIS Cut Line= 2
      2134232.18       213167.33     2136437.041      212885.212
#Sta/Elev= 30
       0 2337.33    72.1 2324.84   265.6 2304.84     282 2300.04   311.5 2300.34
   383.6 2290.85     459 2284.84   504.9 2282.79   609.8 2281.35   806.5 2280.63
   885.2 2278.22     895 2276.86   934.4 2278.48   957.3 2276.27   980.3 2278.76
  1009.8 2279.11  1026.2 2276.66  1055.7 2278.55  1121.2 2279.47  1137.6 2276.86
  1150.8 2276.57  1183.6 2278.61  1209.8 2277.57  1232.7 2280.18  1291.7 2280.59
  1721.2 2281.89  1980.2 2280.67  2003.2 2283.78  2081.9 2315.22  2222.8 2351.59
#Mann= 13 ,-1 , 0
       0    .035       0     500     .07       0   934.4    .045       0
   980.3     .07       0    1200    .035       0    1300     .06       0
    1500     .07       0    1600     .04       0    1700     .06       0
    1790     .07       0    1990    .035       0    2090      .1       0
    2130     .04       0
#XS Ineff= 2 , 0
                         1562.07         2285.28
Permanent Ineff=
       F       F
Bank Sta=934.4,980.3
XS Rating Curve= 0 ,0
Exp/Cntr=0.3,0.1

Type RM Length L Ch R = 1 ,80943   ,533.5,528.6,515.4
XS GIS Cut Line= 2
2134434.83340111213748.048297421 2136447.0103973212909.212362947
#Sta/Elev= 30
       0 2336.75    47.1 2333.94   114.8 2327.16   224.8 2313.47   263.9 2306.98
   306.5 2305.14   374.1  2299.2   385.6 2297.62   395.6 2294.05   420.3 2295.47
   452.3  2292.2     516 2281.08   541.1 2278.48   637.1 2276.52   709.2 2278.51
   932.1 2278.19  1165.8 2276.36  1178.3 2274.96  1184.5 2274.27  1208.72275.073
  1223.2 2278.01    1348 2279.25  1696.4 2280.88  1938.1  2279.7  1970.1 2282.75
  2016.3 2302.56  2041.7  2311.4  2108.7 2327.03  2122.9 2332.43    2180 2347.28
#Mann= 13 ,-1 , 0
       0    .035       0     680     .07       0     750    .035       0
    1070     .07       0  1178.3    .045       0  1208.7     .06       0
    1280     .07       0    1600     .06       0    1820     .07       0
    1920      .1       0    1960    .035       0    2030      .1       0
    2140     .04       0
#XS Ineff= 2 , 0
                         1368.42         2281.33
Permanent Ineff=
       F       F
Bank Sta=1178.3,1208.7
XS Rating Curve= 0 ,0
Exp/Cntr(USF)=0,0
Exp/Cntr=0.3,0.1

Type RM Length L Ch R = 1 ,80415   ,938.7,929.3,893.3
XS GIS Cut Line= 2
     2134753.013       214261.08     2136441.381      212928.615
#Sta/Elev= 30
       0  2365.3    45.9 2363.18    98.4 2354.86   180.3 2337.06   311.5 2317.99
   350.8 2309.26     377 2307.88   396.7 2303.72   413.1 2303.46     518 2280.12
     600 2277.23   721.3 2277.26   757.4 2275.17   944.3 2276.22   960.7 2274.08
   973.8 2272.41   983.6 2274.14    1000 2276.37  1068.9 2274.56  1091.8 2276.81
  1160.7  2276.8  1213.1 2278.58  1275.4 2277.73    1777 2280.19  1888.5 2279.05
  1944.3 2282.08  1973.8 2284.43  2029.5    2307  2095.1 2323.39  2150.8 2340.94
#Mann= 13 ,-1 , 0
       0    .035       0     600     .07       0     620    .035       0
     730     .07       0     780    .035       0     850     .07       0
   960.7    .045       0   983.6     .07       0    1090    .035       0
    1410     .07       0    1850    .035       0    1890      .1       0
    2100     .04       0
#XS Ineff= 2 , 0
                         1257.88            2305
Permanent Ineff=
       F       F
Bank Sta=960.7,983.6
XS Rating Curve= 0 ,0
Exp/Cntr=0.3,0.1

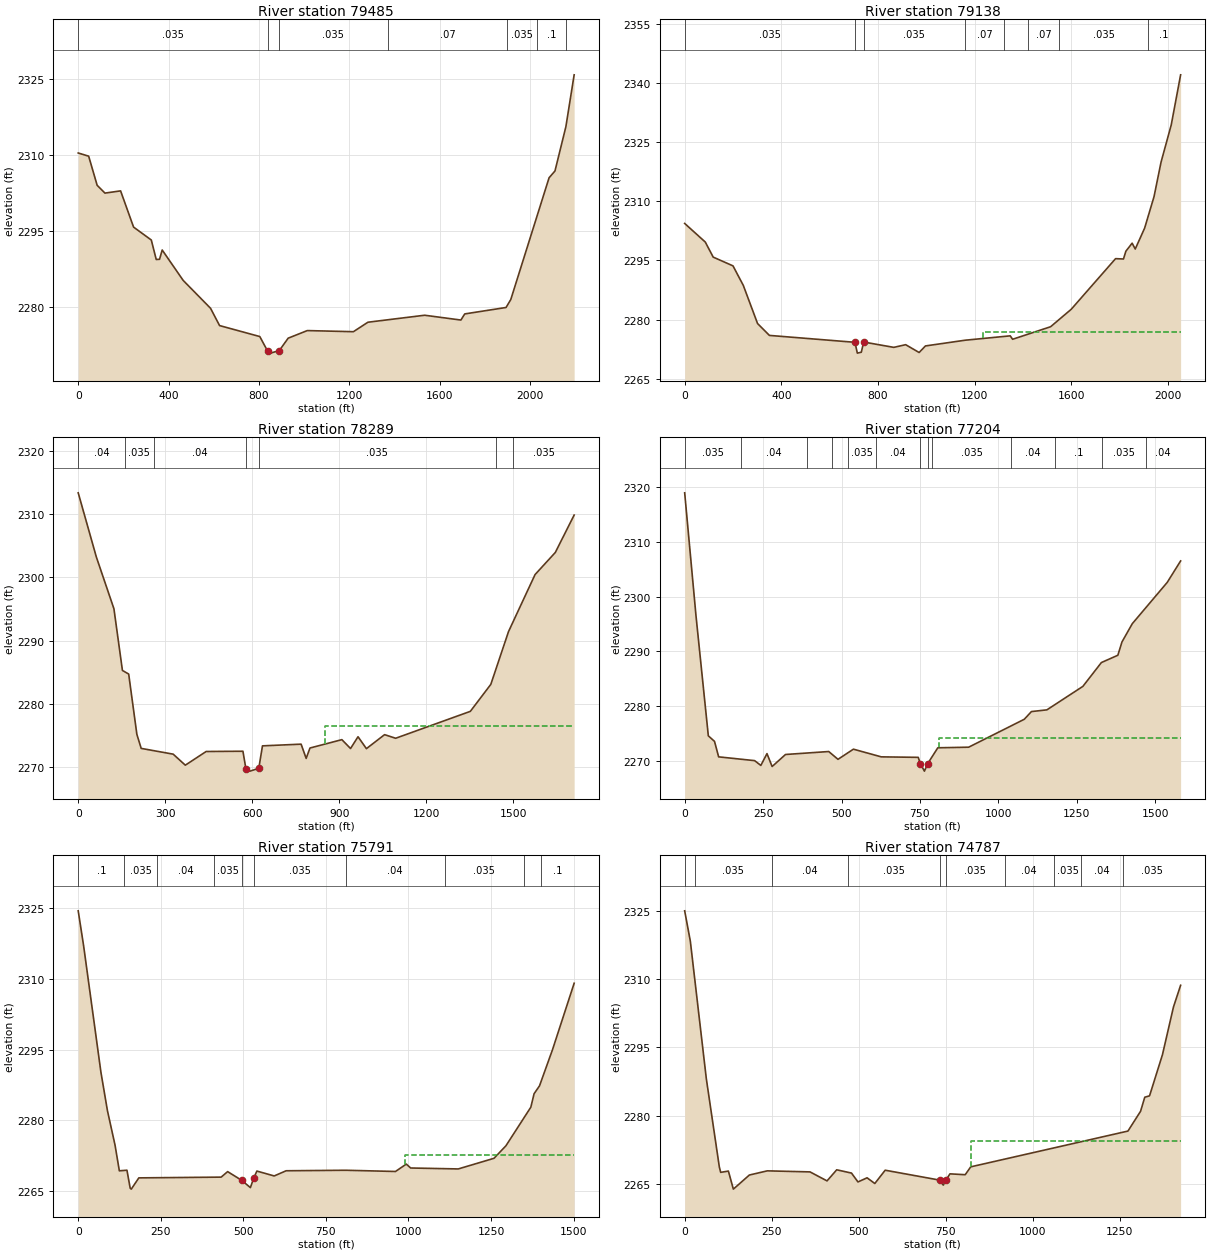
Type RM Length L Ch R = 1 ,79485   ,346.1,347.3,346.4
XS GIS Cut Line= 2
2135109.26115051214715.1445062152136555.92435039213062.631997264
#Sta/Elev= 30
       0 2310.49    46.3 2309.86    83.9 2304.11   118.4 2302.57   187.7 2303.01
   245.2 2295.86   323.7 2293.31   345.5 2289.47   360.2  2289.5   371.9 2291.34
   464.8 2285.34   586.1 2279.83     626 2276.42   804.2 2274.25  838.57  2271.4
   851.3 2270.98   890.5 2271.48   929.8 2273.93  1014.5 2275.43  1218.7 2275.21
    1283 2277.08  1534.3 2278.46  1694.7 2277.51  1711.8 2278.72  1894.7 2279.99
  1915.6 2281.55  2085.3  2305.6  2111.4 2306.94  2159.7 2315.68  2196.3 2325.92
#Mann= 7 ,-1 , 0
       0    .035       0  838.57    .045       0   890.5    .035       0
    1370     .07       0    1900    .035       0    2030      .1       0
    2160     .04       0
Bank Sta=838.57,890.5
XS Rating Curve= 0 ,0
Exp/Cntr(USF)=0,0
Exp/Cntr=0.3,0.1

Type RM Length L Ch R = 1 ,79138   ,833,849.1,834
XS GIS Cut Line= 3
     2135447.458      214855.698     2136636.694      213471.149
     2136701.798      213254.136
#Sta/Elev= 30
       0 2304.35    85.2 2299.64     118 2295.82   199.9  2293.6   242.5 2288.66
   301.5 2278.99   350.6 2275.98   704.5 2274.23   714.3 2271.49   730.7 2271.72
   740.6  2274.3   865.1 2272.95   914.2 2273.63   969.9 2271.65   996.1 2273.31
    1160 2274.76  1346.8 2275.87  1356.6    2275  1513.9 2278.18  1599.1  2282.6
  1782.6 2295.43  1815.3 2295.34  1825.2 2297.31  1851.1 2299.35    1864 2297.87
  1902.8 2303.16  1941.7 2311.14  1970.8  2319.9  2012.9 2329.32  2051.7 2342.01
#Mann= 8 ,-1 , 0
       0    .035       0   704.5    .045       0   740.6    .035       0
    1160     .07       0    1320    .035       0    1420     .07       0
    1550    .035       0 1915.17      .1       0
#XS Ineff= 2 , 0
                         1235.92         2276.79
Permanent Ineff=
       F       F
Bank Sta=704.5,740.6
XS Rating Curve= 0 ,0
Exp/Cntr=0.3,0.1

Type RM Length L Ch R = 1 ,78289   ,1065,1084.9,1025.4
XS GIS Cut Line= 2
2135906.65596098215158.1160645752137033.68092816213871.557882865
#Sta/Elev= 30
       0 2313.37    62.5 2303.24   123.2 2295.06   152.5 2285.32   174.1 2284.75
   202.3 2275.23   217.2 2273.01   327.5  2272.1   369.4 2270.36   441.3 2272.52
   568.1 2272.56   578.6 2269.72   592.6 2269.42   622.8 2269.87   635.5 2273.41
   768.7 2273.68   786.2 2271.43   799.3 2273.07   909.3 2274.39   939.2 2272.99
     965 2274.85     994 2272.97  1056.6 2275.18  1094.8 2274.61  1352.4 2278.86
    1423 2283.12    1484 2291.45  1575.6 2300.46  1645.4 2303.95  1710.4 2309.86
#Mann= 7 ,-1 , 0
       0     .04       0     160    .035       0     260     .04       0
   578.6    .045       0   622.8    .035       0    1440      .1       0
    1500    .035       0
#XS Ineff= 2 , 0
                          852.63         2276.57
Permanent Ineff=
       F       F
Bank Sta=578.6,622.8
XS Rating Curve= 0 ,0
Exp/Cntr(USF)=0,0
Exp/Cntr=0.3,0.1

Type RM Length L Ch R = 1 ,77204   ,1388,1412.8,1361.9
XS GIS Cut Line= 2
     2136280.791      215341.809     2137365.861      214191.636
#Sta/Elev= 30
       0  2318.9    36.1 2296.49    75.4 2274.63    95.1 2273.62   108.3  2270.8
   223.1 2270.11   242.8 2269.24   262.4 2271.39   278.8 2269.04   321.5 2271.23
   459.3 2271.77   488.8 2270.35     538  2272.2   626.6  2270.8   744.7 2270.71
   751.2 2269.58   764.4  2268.2  775.05 2269.58     807 2272.45   905.4 2272.56
  1082.6 2277.64  1105.6 2279.05  1154.8 2279.36  1269.6 2283.64  1328.6 2287.98
  1381.1 2289.31  1394.2 2291.73    1427 2295.05  1538.6 2302.59  1581.2 2306.49
#Mann= 13 ,-1 , 0
       0    .035       0     180     .04       0     390    .035       0
     470     .04       0     520    .035       0     610     .04       0
   751.2    .045       0  775.05     .04       0     790    .035       0
    1040     .04       0    1180      .1       0    1330    .035       0
    1470     .04       0
#XS Ineff= 2 , 0
                          810.53         2274.15
Permanent Ineff=
       F       F
Bank Sta=751.2,775.05
XS Rating Curve= 0 ,0
Exp/Cntr=0.3,0.1

Type RM Length L Ch R = 1 ,75791   ,982.9,1004.2,984.4
XS GIS Cut Line= 2
      2136732.18      215949.448     2137752.145      214847.018
#Sta/Elev= 30
       0 2324.47    16.4 2317.03    68.9 2290.12    88.5 2282.01   111.5 2274.69
   124.6 2269.22   147.6 2269.35   157.4 2265.53   160.7 2265.33   183.6 2267.72
   432.9 2267.88   452.5 2269.05   495.2  2267.2   521.4 2265.65   531.2  2267.6
   541.1 2269.17   593.5 2268.13   629.6 2269.23     810 2269.34   960.8 2269.08
   993.6 2270.65  1006.7 2269.82    1151 2269.62  1259.2 2271.88  1295.3 2274.54
  1370.7 2282.74  1380.6  2285.6    1397 2287.28  1436.3 2294.95  1501.9 2309.08
#Mann= 10 ,-1 , 0
       0      .1       0     140    .035       0     240     .04       0
     410    .035       0   495.2    .045       0   531.2    .035       0
     810     .04       0    1110    .035       0    1350     .04       0
    1400      .1       0
#XS Ineff= 2 , 0
                          989.47         2272.56
Permanent Ineff=
       F       F
Bank Sta=495.2,531.2
XS Rating Curve= 0 ,0
Exp/Cntr=0.3,0.1

Type RM Length L Ch R = 1 ,74787   ,469.5,474,464.7
XS GIS Cut Line= 2
2136874.14771363216151.3389808542138129.82849898215477.182493639
#Sta/Elev= 30
       0 2325.05    16.3 2318.35    62.3 2288.06    99.6  2268.7   103.5 2267.52
   125.6  2267.8   139.9 2263.83   185.9 2266.93   237.3 2267.85   360.2 2267.62
   409.1 2265.64   436.9 2268.08   479.4 2267.36     498 2265.41   524.1 2266.32
   546.4 2265.07   576.2 2267.99  732.99 2265.81   743.2 2264.71   750.4 2265.79
   762.4 2267.19   806.2    2267     822 2268.73  1273.8  2276.6  1310.1 2280.95
  1322.2 2284.05  1335.9 2284.35    1373  2293.4  1404.6 2303.88  1425.2 2308.67
#Mann= 10 ,-1 , 0
       0      .1       0      30    .035       0     250     .04       0
     470    .035       0  732.99    .045       0   750.4    .035       0
     920     .04       0    1060    .035       0    1140     .04       0
    1260    .035       0
#XS Ineff= 2 , 0
                          823.16          2274.4
Permanent Ineff=
       F       F
Bank Sta=732.99,750.4
XS Rating Curve= 0 ,0
Exp/Cntr(USF)=0,0
Exp/Cntr=0.3,0.1

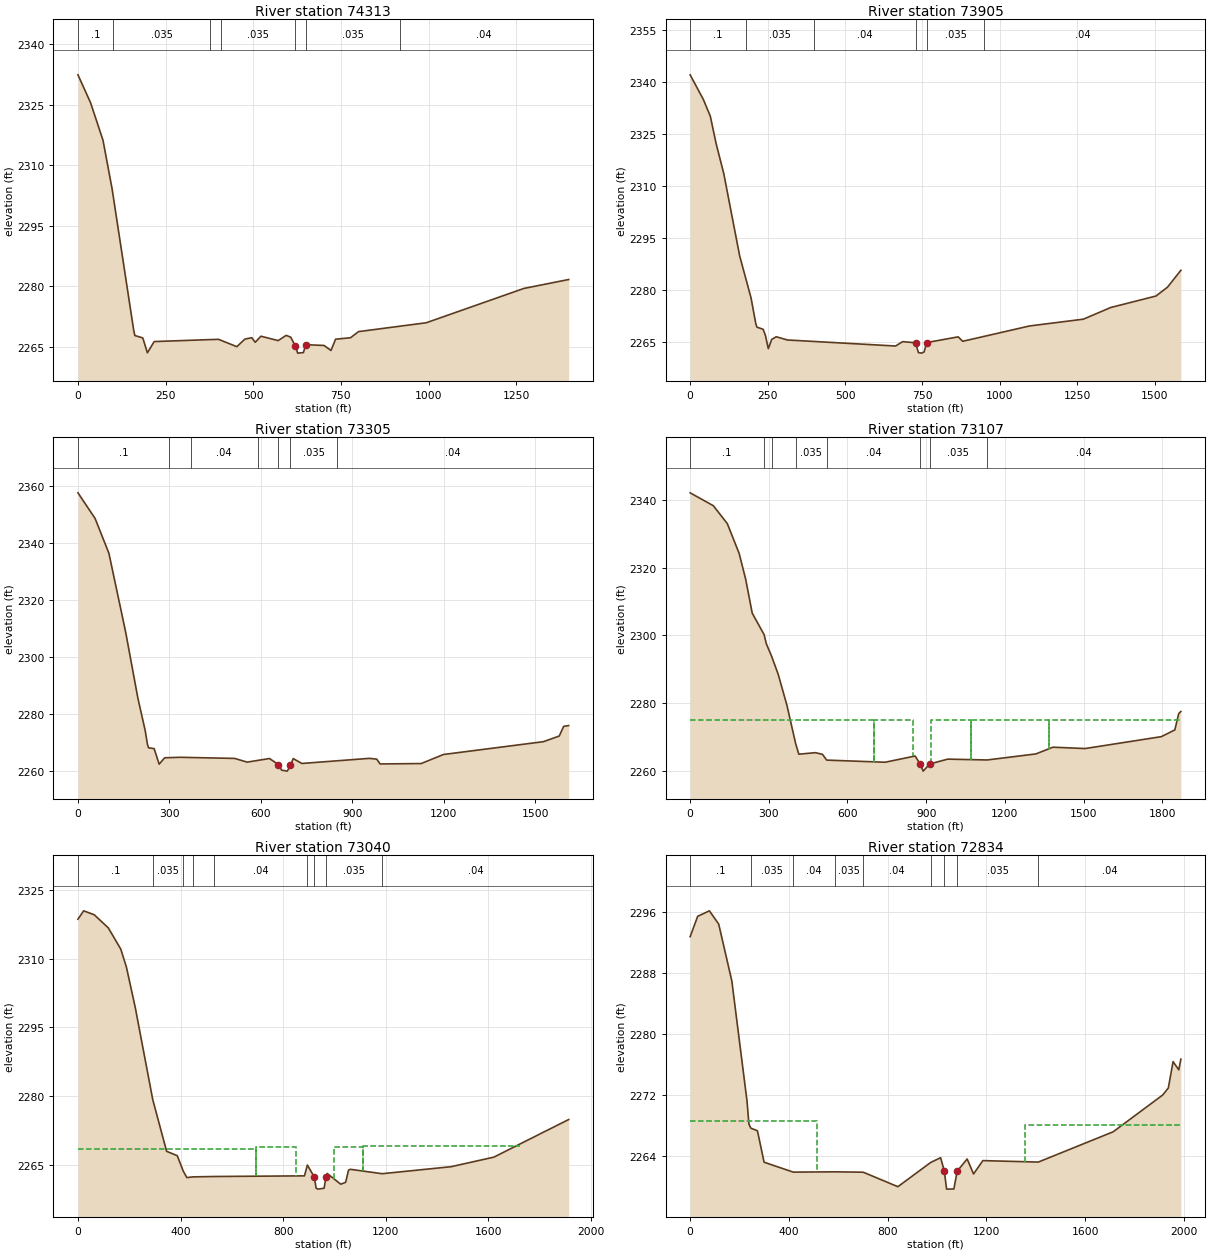
Type RM Length L Ch R = 1 ,74313   ,405.4,408.2,387.6
XS GIS Cut Line= 3
     2136897.111      216261.948     2137122.805       216287.99
     2138242.597      215940.768
#Sta/Elev= 30
       0 2332.46    35.7  2325.6    71.4 2316.24    97.4 2304.15     159 2269.06
   162.3 2267.75     185 2267.15     198 2263.46   217.5 2266.25   400.8 2266.81
   453.2 2264.98   476.1 2266.86   495.7 2267.21   505.6 2266.07   521.9 2267.58
     571 2266.49     594 2267.79   607.1 2267.32   620.2 2265.09   626.7 2263.38
   643.1 2263.52   649.6 2265.48     702 2265.28   721.7 2264.04   734.8 2266.84
   777.4  2267.2   800.3 2268.72   993.5 2270.92  1271.9 2279.44  1399.6 2281.65
#Mann= 7 ,-1 , 0
       0      .1       0     100    .035       0  377.19     .04       0
  407.19    .035       0   620.2    .045       0   649.6    .035       0
  917.19     .04       0
Bank Sta=620.2,649.6
XS Rating Curve= 0 ,0
Exp/Cntr=0.3,0.1

Type RM Length L Ch R = 1 ,73905   ,590.7,599.3,581.6
XS GIS Cut Line= 2
 2136933.1975115216727.8062114972138349.34909575216017.724538938
#Sta/Elev= 30
       0 2342.12    42.6 2335.02    65.1  2330.2    83.5 2322.42   108.6 2313.62
   159.9 2289.92   196.6 2277.81   211.9 2270.39   215.6 2269.39   235.7 2268.77
   243.1 2266.97   252.3 2263.19   263.3 2265.85     278 2266.62   313.9 2265.69
   663.3 2263.95   685.8 2265.21   727.72264.884   736.8 2262.07   746.6  2261.9
   755.1 2262.21   763.62264.943   865.2 2266.59   879.9 2265.31  1095.7 2269.73
  1269.7 2271.69  1357.7 2275.05  1503.8 2278.36  1541.1 2280.92  1584.2 2285.78
#Mann= 6 ,-1 , 0
       0      .1       0     180    .035       0     400     .04       0
   727.7    .045       0   763.6    .035       0     950     .04       0
Bank Sta=727.7,763.6
XS Rating Curve= 0 ,0
Exp/Cntr(USF)=0,0
Exp/Cntr=0.3,0.1

Type RM Length L Ch R = 1 ,73305   ,200.4,198.8,197.7
XS GIS Cut Line= 2
 2137223.9426115217099.1228749922138663.12181651216377.332692663
#Sta/Elev= 30
       0 2357.63    56.2 2348.65   101.5 2336.43   156.5 2308.76   196.6 2285.56
   220.7 2274.12     228 2269.32   231.7 2268.12     250 2267.81   266.4 2262.37
   284.5  2264.6   334.9 2264.78   514.3 2264.38   555.2 2263.08   628.4 2264.35
   657.82262.204   668.4 2260.26   686.8 2259.92     6972261.921   706.4 2264.33
   734.5 2262.61   955.7  2264.4   980.2 2264.13   991.4 2262.44  1126.1 2262.58
  1199.2 2265.76  1527.3 2270.26    1579 2272.24  1593.7 2275.65    1610 2275.91
#Mann= 7 ,-1 , 0
       0      .1       0     300    .035       0     370     .04       0
     590    .035       0   657.8    .045       0     697    .035       0
     850     .04       0
Bank Sta=657.8,697
XS Rating Curve= 0 ,0
Exp/Cntr(USF)=0,0
Exp/Cntr=0.5,0.3

Type RM Length L Ch R = 1 ,73107   ,66.8,66.3,66.1
XS GIS Cut Line= 4
      2137170.94      217511.318     2137743.465      217072.712
     2138045.548      216892.156     2138757.354      216531.045
#Sta/Elev= 30
       0 2342.16    88.4 2338.35   141.7 2333.05   187.1 2324.19   211.9 2316.53
   236.7 2306.56   282.2 2300.18   290.4 2297.52   310.7  2293.8   335.9 2288.43
     369 2279.32     402 2268.07   414.4 2264.83   477.5 2265.28   504.5  2264.8
   520.6 2263.08   743.3 2262.45   857.9 2264.29   877.62261.851   888.5 2259.82
   913.52261.936   982.3 2263.37  1132.2 2263.12  1318.5 2264.91  1383.4  2266.9
  1506.1  2266.5  1796.8 2270.02  1848.3 2272.02    1863 2276.84  1871.3 2277.46
#Mann= 8 ,-1 , 0
       0      .1       0   282.2    .035       0   310.7      .1       0
     402    .035       0   520.6     .04       0   877.6    .045       0
   913.5    .035       0  1132.2     .04       0
#XS Ineff= 5 ,-1
       0     700    2275     700     850    2275     920    1070    2275
    1070    1370    2275    1370  1871.3    2275
Permanent Ineff=
       F       F       F       F       F
Bank Sta=877.6,913.5
XS Rating Curve= 0 ,0
Exp/Cntr=0.5,0.3

Type RM Length L Ch R = 1 ,73040   ,199.8,206.1,199
XS GIS Cut Line= 4
     2137163.996      217601.596      2137767.77      217135.212
     2138069.854      216954.656     2138781.659      216593.545
#Sta/Elev= 30
       0 2318.65    22.3 2320.48    63.8 2319.61   118.2 2316.76     167 2312.11
   188.9 2308.19   223.2 2299.41   291.8 2279.17   345.7 2267.92   387.2 2266.97
   410.3 2263.62   424.5 2262.19     450 2262.34   532.3 2262.42   883.1 2262.56
   894.3 2264.92   921.4 2262.31   928.5 2259.85   936.3 2259.66   959.6 2259.86
   966.7 2262.28   971.6 2263.09  1024.3 2260.74  1043.5 2261.14  1054.8 2263.81
  1062.1 2263.99  1185.9 2263.03  1454.5 2264.56  1621.3 2266.65    1913 2274.87
#Mann= 9 ,-1 , 0
       0      .1       0   291.8    .035       0   410.3     .04       0
     450    .035       0   532.3     .04       0   894.3    .035       0
   921.4    .045       0   966.7    .035       0  1185.9     .04       0
#XS Ineff= 4 ,-1
       0  695.11  2268.5  695.11  848.412268.886  997.43    11102268.945
    1110    1722    2269
Permanent Ineff=
       F       F       F       F
Bank Sta=921.4,966.7
XS Rating Curve= 0 ,0
Exp/Cntr=0.5,0.3

Type RM Length L Ch R = 1 ,72834   ,667.6,691.8,677.3
XS GIS Cut Line= 2
2137162.24964505217701.1631874112138858.93956829216665.058516996
#Sta/Elev= 30
       0 2292.79    30.5 2295.46    77.9 2296.18   115.7 2294.44   168.8 2286.99
   230.4 2271.22     238 2268.22   245.7 2267.67   272.6 2267.33   299.5  2263.2
   417.8  2261.9   587.8 2261.94   701.1 2261.89   841.6 2259.99   974.5 2263.17
  1014.6 2263.79  1029.4 2262.09  1038.9 2259.67  1068.4 2259.69  1081.7 2262.02
  1122.2 2263.63  1148.1 2261.66  1185.8 2263.41  1410.5 2263.22  1713.6 2267.19
  1914.1 2272.01  1937.2 2272.94  1956.4  2276.4  1979.5 2275.32    1988 2276.72
#Mann= 9 ,-1 , 0
       0      .1       0   245.7    .035       0   417.8     .04       0
   587.8    .035       0   701.1     .04       0   974.5    .035       0
  1029.4    .045       0  1081.7    .035       0  1410.5     .04       0
#XS Ineff= 2 , 0
          513.13 2268.64 1355.56         2268.04
Permanent Ineff=
       F       F
Bank Sta=1029.4,1081.7
XS Rating Curve= 0 ,0
Exp/Cntr(USF)=0,0
Exp/Cntr=0.3,0.1

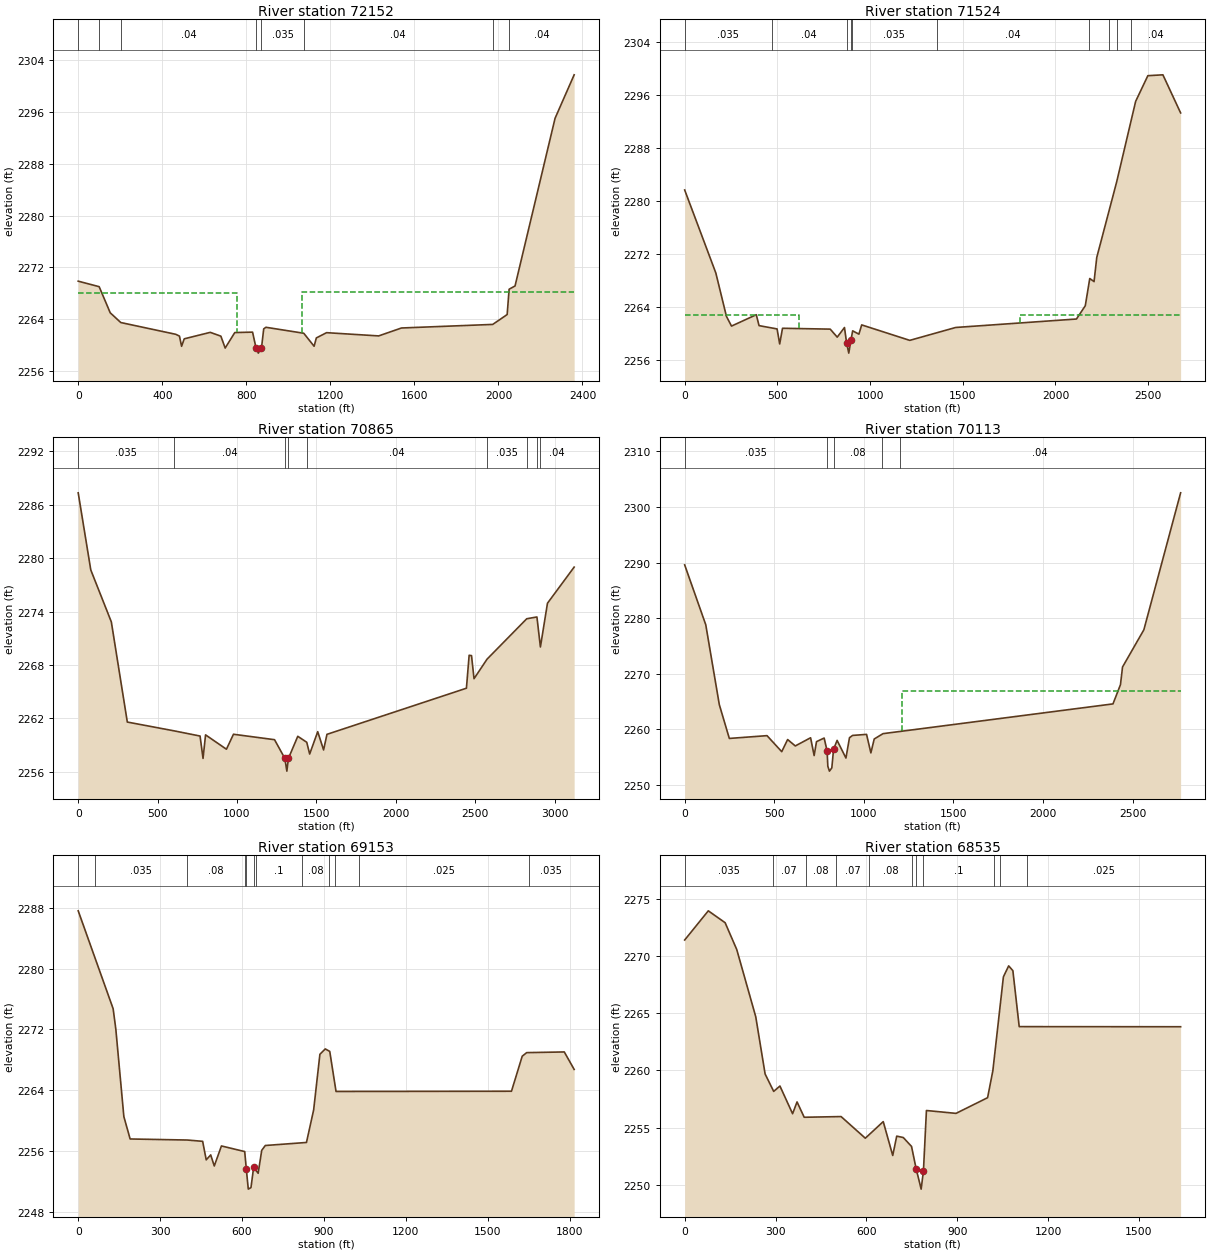
Type RM Length L Ch R = 1 ,72152   ,623.1,627.8,610.5
XS GIS Cut Line= 3
2137206.33797291217856.1223345072137585.72116359217642.934092852
2139375.65630167216934.239129826
#Sta/Elev= 30
       0 2269.89    99.7 2269.04   152.4 2265.02   202.6 2263.52   464.2 2261.71
   481.9 2261.43     492 2259.86   504.6 2261.01   628.5 2262.01     679 2261.42
   699.4 2259.59   745.2 2261.98   829.8 2262.04     846 2259.66   857.1 2258.81
   872.2 2259.58   882.8 2262.54   893.4 2262.79  1073.4 2261.87  1122.7 2259.87
  1133.3 2261.15  1182.1 2261.96    1430 2261.46  1538.5 2262.68  1972.8 2263.23
  2041.5 2264.75  2050.8 2268.65    2079 2269.15  2269.5 2294.97  2360.3 2301.66
#Mann= 8 ,-1 , 0
       0     .04       0    99.7    .035       0   202.6     .04       0
     846    .045       0   872.2    .035       0  1073.4     .04       0
  1972.8    .035       0  2050.8     .04       0
#XS Ineff= 2 , 0
          755.05 2268.05 1063.13         2268.19
Permanent Ineff=
       F       F
Bank Sta=846,872.2
XS Rating Curve= 0 ,0
Exp/Cntr(USF)=0,0
Exp/Cntr=0.3,0.1

Type RM Length L Ch R = 1 ,71524   ,636.9,659.2,647.4
XS GIS Cut Line= 2
     2137316.774      218362.013 2139585.4730327216944.428785468
#Sta/Elev= 30
       0 2281.66   168.1  2269.1   225.3 2262.54   252.6 2261.07   386.2 2262.79
   401.2 2261.14   498.4 2260.64   512.6 2258.37   527.7 2260.74   785.1 2260.61
   822.9  2259.4     862 2260.85   873.6 2258.51   885.2 2256.98   896.8 2258.95
   906.2 2260.35   939.8 2259.85   954.9 2261.25  1214.1 2258.91  1461.7 2260.86
  2113.4 2262.14    2161 2264.15  2185.1 2268.27  2208.3  2267.8  2222.9 2271.46
    2330 2282.85  2432.7 2295.07  2498.5 2298.95  2579.7 2299.08  2675.2 2293.32
#Mann= 10 ,-1 , 0
       0    .035       0     470     .04       0   873.6    .045       0
   896.8     .04       0     900    .035       0    1360     .04       0
    2180    .035       0    2290     .04       0    2330    .035       0
    2410     .04       0
#XS Ineff= 2 , 0
             619 2262.75 1809.56         2262.75
Permanent Ineff=
       F       F
Bank Sta=873.6,896.8
XS Rating Curve= 0 ,0
Exp/Cntr=0.3,0.1

Type RM Length L Ch R = 1 ,70865   ,728.1,752.3,718.7
XS GIS Cut Line= 3
2137246.37143755218472.6880165992139216.77165193217927.909501314
2140122.37749551217340.680712111
#Sta/Elev= 30
       0 2287.34    79.2 2278.68   208.6 2272.85   309.3  2261.6   604.8 2260.61
   767.5 2260.03   786.2 2257.52   802.2 2260.16   933.6 2258.55   977.9 2260.23
  1236.6 2259.62  1301.3 2257.53  1314.2 2256.09  1323.9 2257.51    1383    2260
  1439.5 2259.33  1457.8 2258.01  1508.6 2260.52  1545.5 2258.47  1566.8 2260.22
  2445.2  2265.4  2462.3  2269.1  2477.2 2269.06  2493.1 2266.47    2575 2268.66
  2825.1  2273.2  2889.2  2273.4  2911.2 2270.03  2955.6 2274.94  3123.7    2279
#Mann= 9 ,-1 , 0
       0    .035       0   604.8     .04       0  1301.3    .045       0
  1323.9    .035       0  1439.5     .04       0    2575    .035       0
  2825.1     .04       0  2889.2    .035       0  2911.2     .04       0
Bank Sta=1301.3,1323.9
XS Rating Curve= 0 ,0
Exp/Cntr(USF)=0,0
Exp/Cntr=0.3,0.1

Type RM Length L Ch R = 1 ,70113   ,944.4,959.4,955.8
XS GIS Cut Line= 3
     2137474.368      218705.5242139678.84454975218564.922129741
2140088.77738542218945.028454513
#Sta/Elev= 30
       0  2289.6   117.7 2278.83   193.3 2264.47   249.2 2258.39   459.6 2258.89
   541.7 2256.01   574.6 2258.19   617.4 2257.04   702.8 2258.51   722.6 2255.31
   735.7 2257.81   778.4 2258.46   794.9 2256.15     799 2253.38     808 2252.51
   821.2 2253.09     831 2256.44   850.8 2258.04   900.1 2254.86   919.8 2258.52
   937.3 2258.93  1015.1 2259.12  1039.3 2255.79  1057.9 2258.29  1107.1 2259.25
  2390.5  2264.6  2432.3 2268.06  2443.9 2271.24  2562.9 2277.93    2768 2302.56
#Mann= 5 ,-1 , 0
       0    .035       0   794.9    .045       0     831     .08       0
    1100    .035       0    1200     .04       0
#XS Ineff= 2 , 0
                         1212.12         2266.99
Permanent Ineff=
       F       F
Bank Sta=794.9,831
XS Rating Curve= 0 ,0
Exp/Cntr=0.3,0.1

Type RM Length L Ch R = 1 ,69153   ,614.3,618.4,610.2
XS GIS Cut Line= 2
      2137504.75      218983.302     2139217.815      219587.707
#Sta/Elev= 30
       0 2287.63   127.9 2274.73   137.7 2272.06   167.2 2260.51   190.2 2257.56
     400 2257.42   455.8 2257.25   468.9 2254.81   485.3 2255.46   498.4    2254
   524.6 2256.64   609.9  2255.9   615.9 2253.54     623 2250.95   632.8 2251.15
   642.7 2253.84   659.1 2253.04   672.2 2256.06   685.3  2256.7   836.1  2257.1
   862.4 2261.39   885.3 2268.72     905 2269.43   921.4  2269.1   944.4 2263.82
    1587 2263.85  1626.4 2268.47  1642.8 2268.94  1780.5 2269.03  1816.6 2266.73
#Mann= 12 ,-1 , 0
       0     .04       0      60    .035       0     400     .08       0
     610     .07       0   615.9    .045       0   642.7     .07       0
     650      .1       0     820     .08       0     920      .1       0
     940    .035       0    1030    .025       0    1650    .035       0
Bank Sta=615.9,642.7
XS Rating Curve= 0 ,0
Exp/Cntr=0.3,0.1

Type RM Length L Ch R = 1 ,68535   ,641.7,628.6,599.2
XS GIS Cut Line= 2
2137311.57749541 219343.958839932138855.44731346219889.459508975
#Sta/Elev= 30
       0  2271.4      78 2273.95   133.6 2272.91   171.9 2270.57   234.6  2264.7
   265.6 2259.69   293.9 2258.17   314.5 2258.64   356.3 2256.22     371 2257.25
   394.6 2255.91   516.4 2255.97   596.4 2254.08   655.6 2255.53   686.9 2252.57
   700.1 2254.26   721.7 2254.14     749 2253.36   764.4 2251.39   780.8 2249.63
   788.3 2251.22   798.2  2256.5   895.9 2256.25  1000.1 2257.62  1017.5 2259.98
  1052.3 2268.18  1069.7 2269.14  1083.6 2268.72  1104.5 2263.83  1637.4 2263.82
#Mann= 11 ,-1 , 0
       0    .035       0     290     .07       0     400     .08       0
     500     .07       0     610     .08       0     750      .1       0
   764.4    .045       0   788.3      .1       0    1020     .08       0
    1040      .1       0    1130    .025       0
Bank Sta=764.4,788.3
XS Rating Curve= 0 ,0
Exp/Cntr(USF)=0,0
Exp/Cntr=0.3,0.1

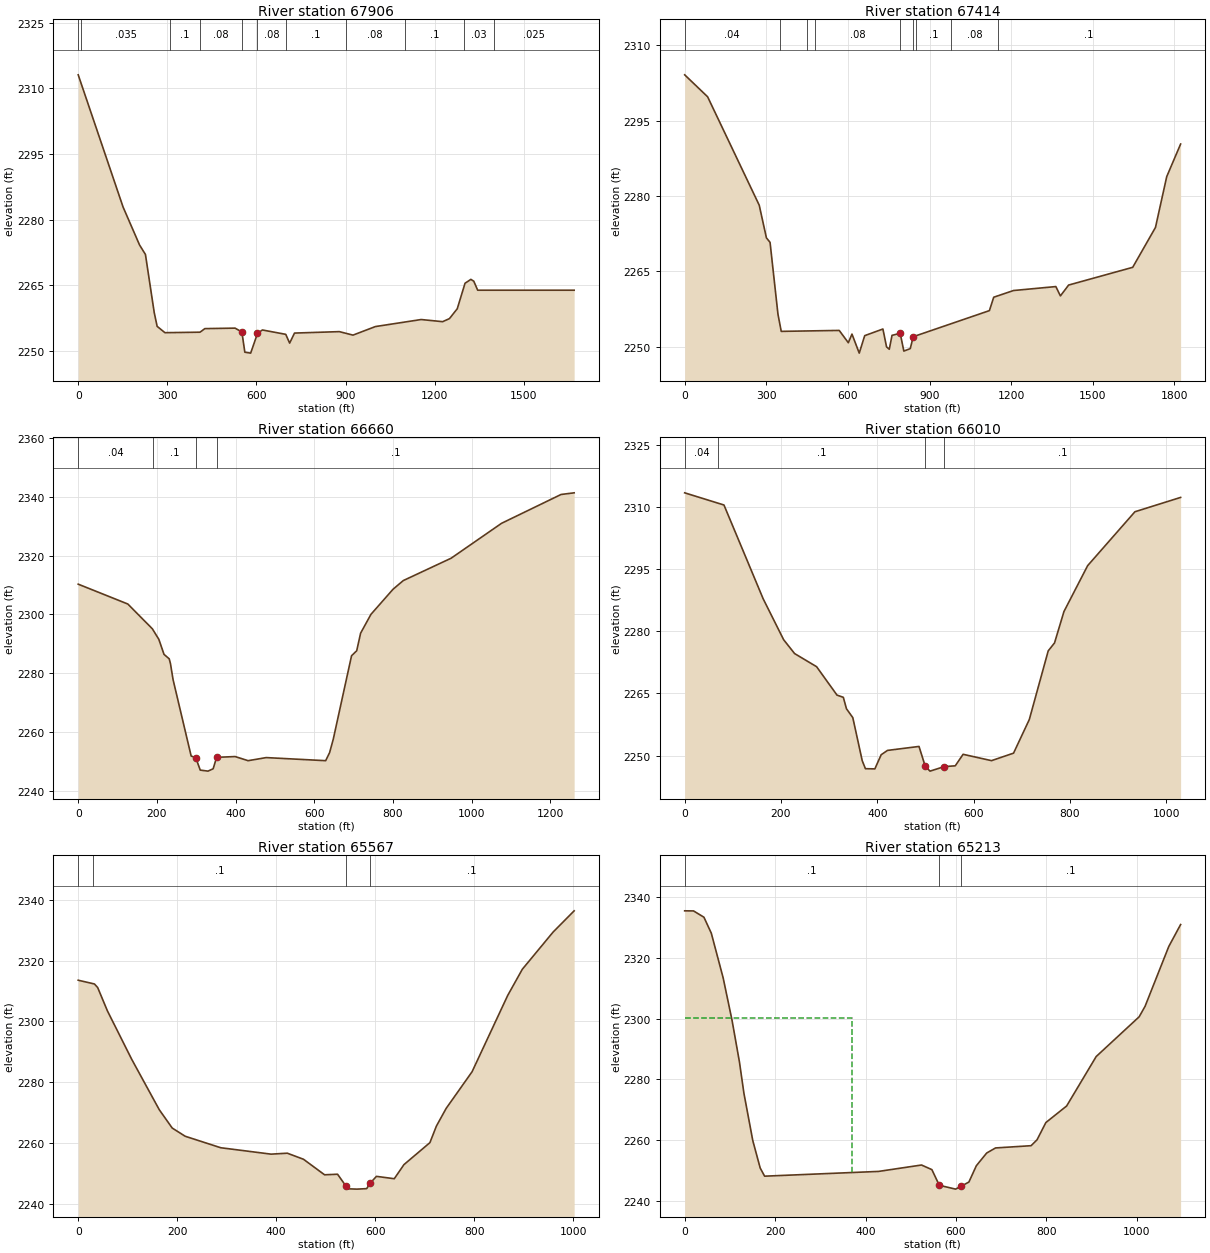
Type RM Length L Ch R = 1 ,67906   ,490.5,492.2,479.6
XS GIS Cut Line= 2
     2137183.569      220120.455     2138841.555      219925.143
#Sta/Elev= 30
       0 2313.12   150.9 2282.88   206.6 2274.16   226.3 2272.01   255.8 2258.74
   265.7 2255.55   291.9  2254.1     410 2254.21   426.4 2255.03   528.1 2255.14
     551 2254.25   560.9 2249.63   580.5 2249.42   603.5 2253.94   619.9 2254.72
   698.6 2253.72   711.7 2251.71   728.1 2254.01     879 2254.34   924.9 2253.54
  1000.4  2255.5  1154.5 2257.11  1226.7 2256.62  1249.6 2257.32  1275.9 2259.57
  1302.1 2265.42  1321.8  2266.3  1331.6 2265.88  1344.7 2263.82  1669.4 2263.82
#Mann= 11 ,-1 , 0
       0     .04       0      10    .035       0     310      .1       0
     410     .08       0     551    .045       0   603.5     .08       0
     700      .1       0     900     .08       0    1100      .1       0
    1300     .03       0    1400    .025       0
Bank Sta=551,603.5
XS Rating Curve= 0 ,0
Exp/Cntr=0.3,0.1

Type RM Length L Ch R = 1 ,67414   ,745.9,754.4,756.8
XS GIS Cut Line= 3
2137244.67646996220568.7622289172138587.84321166220301.158127122
2139030.41922617220398.936548931
#Sta/Elev= 30
       0 2304.12    84.3 2299.75     274 2278.17   300.4 2271.67   313.8 2270.77
   342.8 2256.49   354.9 2253.05     568 2253.24   601.5 2250.79   614.9 2252.51
   641.6 2248.72   661.7  2252.2   728.6 2253.52     742 2249.96     752 2249.49
   762.1 2252.26   792.2 2252.66   805.5 2249.13     829 2249.61   840.12251.991
    1120 2257.18  1135.9 2259.85  1208.5 2261.18  1364.2 2261.97    1381 2260.11
  1411.2 2262.27  1646.7  2265.8  1730.4 2273.74  1771.7 2283.85  1822.8 2290.34
#Mann= 9 ,-1 , 0
       0     .04       0     350     .08       0     450      .1       0
     480     .08       0   792.2    .045       0   840.1     .08       0
     850      .1       0     980     .08       0    1150      .1       0
Bank Sta=792.2,840.1
XS Rating Curve= 0 ,0
Exp/Cntr(USF)=0,0
Exp/Cntr=0.3,0.1

Type RM Length L Ch R = 1 ,66660   ,629.6,650.1,610.3
XS GIS Cut Line= 2
2137301.92960441220858.5547805842138559.99237505220937.867433515
#Sta/Elev= 30
       0  2310.3   126.1 2303.55   188.5 2295.12     205 2291.53   218.1 2286.43
   231.3 2284.92   234.5 2283.29   241.1 2277.85   287.1 2251.86   298.62251.349
   310.2 2247.09   329.9 2246.74     343 2247.54   351.82251.431   398.9 2251.69
   431.9 2250.29   477.8 2251.34     629 2250.29   638.9    2253   648.2 2257.53
   694.8 2285.97   707.9 2287.66   717.8 2293.63   744.1 2300.04   800.3 2308.58
   826.3 2311.52   947.9 2319.12  1076.1 2330.99  1227.3 2340.79  1260.6 2341.35
#Mann= 4 ,-1 , 0
       0     .04       0     190      .1       0   298.6    .045       0
   351.8      .1       0
Bank Sta=298.6,351.8
XS Rating Curve= 0 ,0
Exp/Cntr(USF)=0,0
Exp/Cntr=0.3,0.1

Type RM Length L Ch R = 1 ,66010   ,397.7,442.6,462.6
XS GIS Cut Line= 3
     2137287.736      220914.726     2137457.006      221166.462
     2138155.791      221366.115
#Sta/Elev= 30
       0 2313.44    81.6  2310.5   163.1 2287.84   205.5 2277.99   228.3 2274.64
     274 2271.47   316.4 2264.61   329.5 2264.08   336.1  2261.3   349.2 2259.18
   368.8 2248.77   375.4 2246.85     395  2246.8   408.1 2250.21   421.2 2251.26
   486.7 2252.22   499.8 2247.39   509.6 2246.26   539.1 2247.35     562 2247.54
   578.3 2250.32   637.3 2248.79   683.1  2250.6   715.8 2258.71   755.1 2275.29
   768.2  2277.2   787.8 2284.79     837 2295.86   935.2 2308.87  1030.1 2312.33
#Mann= 4 ,-1 , 0
       0     .04       0      70      .1       0   499.8    .045       0
   539.1      .1       0
Bank Sta=499.8,539.1
XS Rating Curve= 0 ,0
Exp/Cntr=0.3,0.1

Type RM Length L Ch R = 1 ,65567   ,357.7,354.3,338.8
XS GIS Cut Line= 2
     2137287.736      220940.768     2137604.576      221891.288
#Sta/Elev= 30
       0 2313.55    32.7 2312.32    39.3 2311.15    58.9 2303.51     108 2287.58
   163.7    2271   189.9 2264.96   216.1 2262.26   288.1 2258.48   389.6 2256.38
   422.4 2256.69   455.1  2254.7   497.7 2249.59   523.9 2249.78   540.3 2246.02
   546.8 2244.97   563.2 2244.88   582.8 2245.04   589.4 2246.76   602.5 2249.08
   638.5  2248.3   658.1 2252.94   710.5 2260.16   723.6  2265.6   743.3 2271.41
   795.7 2283.47   867.7 2308.56   897.2 2317.15   959.4 2329.38  1001.9 2336.36
#Mann= 4 ,-1 , 0
       0     .04       0      30      .1       0   540.3    .045       0
   589.4      .1       0
Bank Sta=540.3,589.4
XS Rating Curve= 0 ,0
Exp/Cntr=0.3,0.1

Type RM Length L Ch R = 1 ,65213   ,451.7,454.2,444.7
XS GIS Cut Line= 2
     2136784.263      221049.274     2137465.687      221908.649
#Sta/Elev= 30
       0  2335.6    19.6 2335.57    42.6 2333.49    58.9 2328.22    85.1 2313.49
   104.8 2299.46   121.1 2285.79     131 2275.47   150.6 2259.86     167  2250.8
   176.8 2248.11   428.9 2249.68   523.8 2251.79   546.7 2250.27   563.1 2245.11
   599.1 2243.84   612.2 2244.86   628.6 2246.18     645 2251.55   667.9 2255.74
   687.5 2257.42   766.1 2258.16   779.2 2260.09   798.8 2265.79   844.7 2271.25
   910.1 2287.56  1005.1 2300.66  1018.2 2304.12  1070.6 2323.83  1096.8 2331.08
#Mann= 3 ,-1 , 0
       0      .1       0   563.1    .045       0   612.2      .1       0
#XS Ineff= 2 , 0
          369.23 2300.33
Permanent Ineff=
       F       F
Bank Sta=563.1,612.2
XS Rating Curve= 0 ,0
Exp/Cntr=0.3,0.1