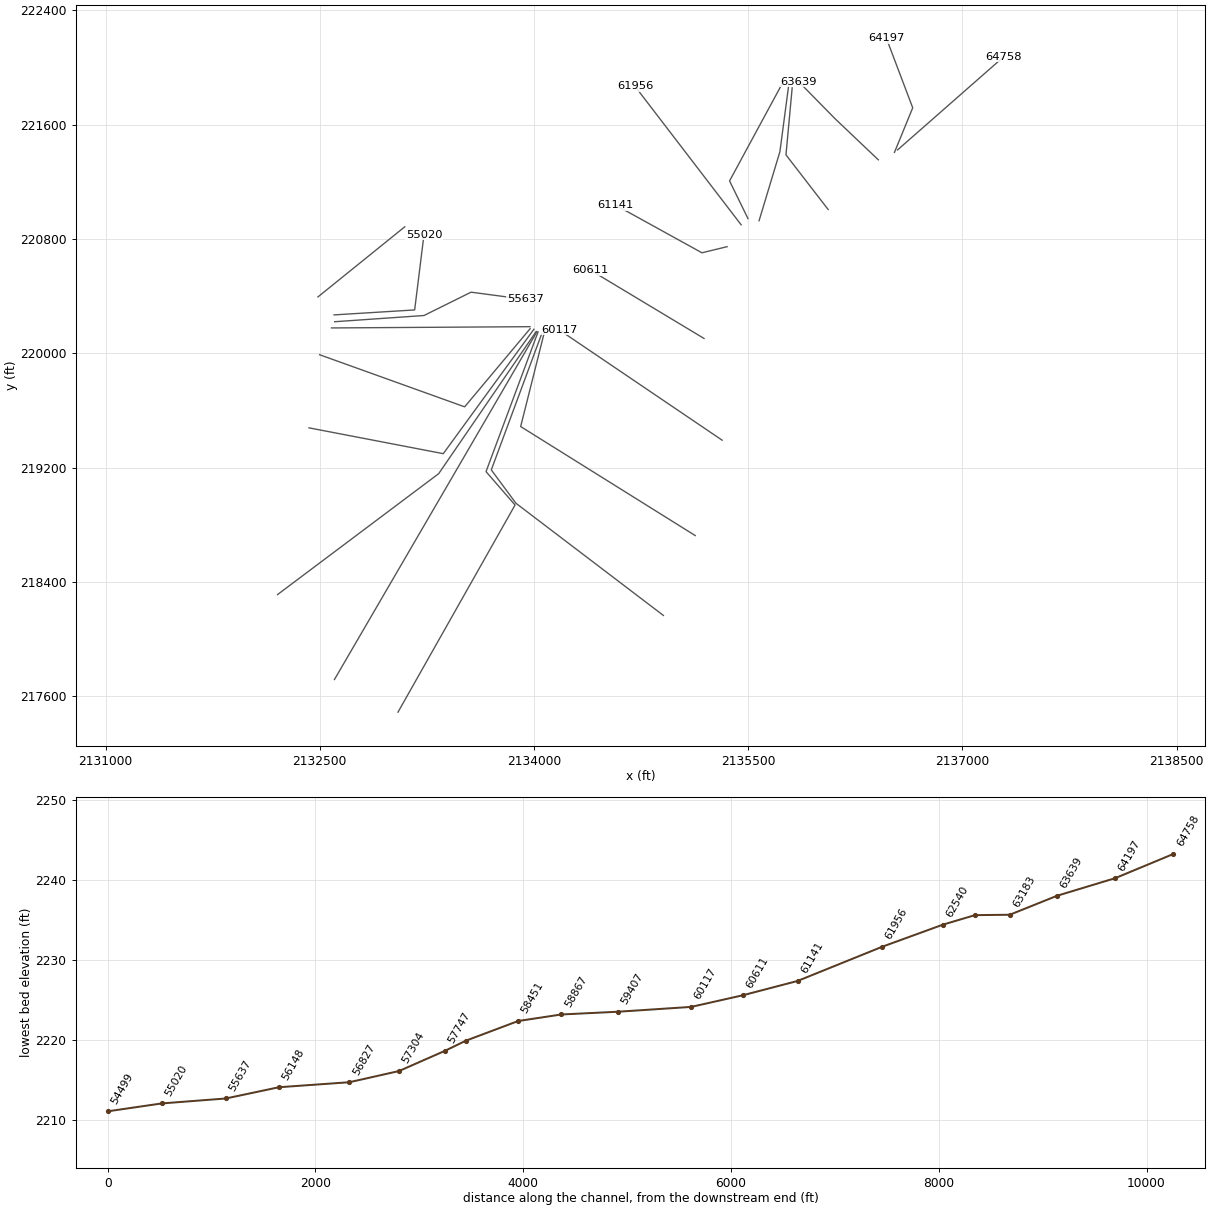
HEC-RAS study SECONDCK.prj: SECONDCK

--- SECONDCK.g01 (geometry) --- (continued)

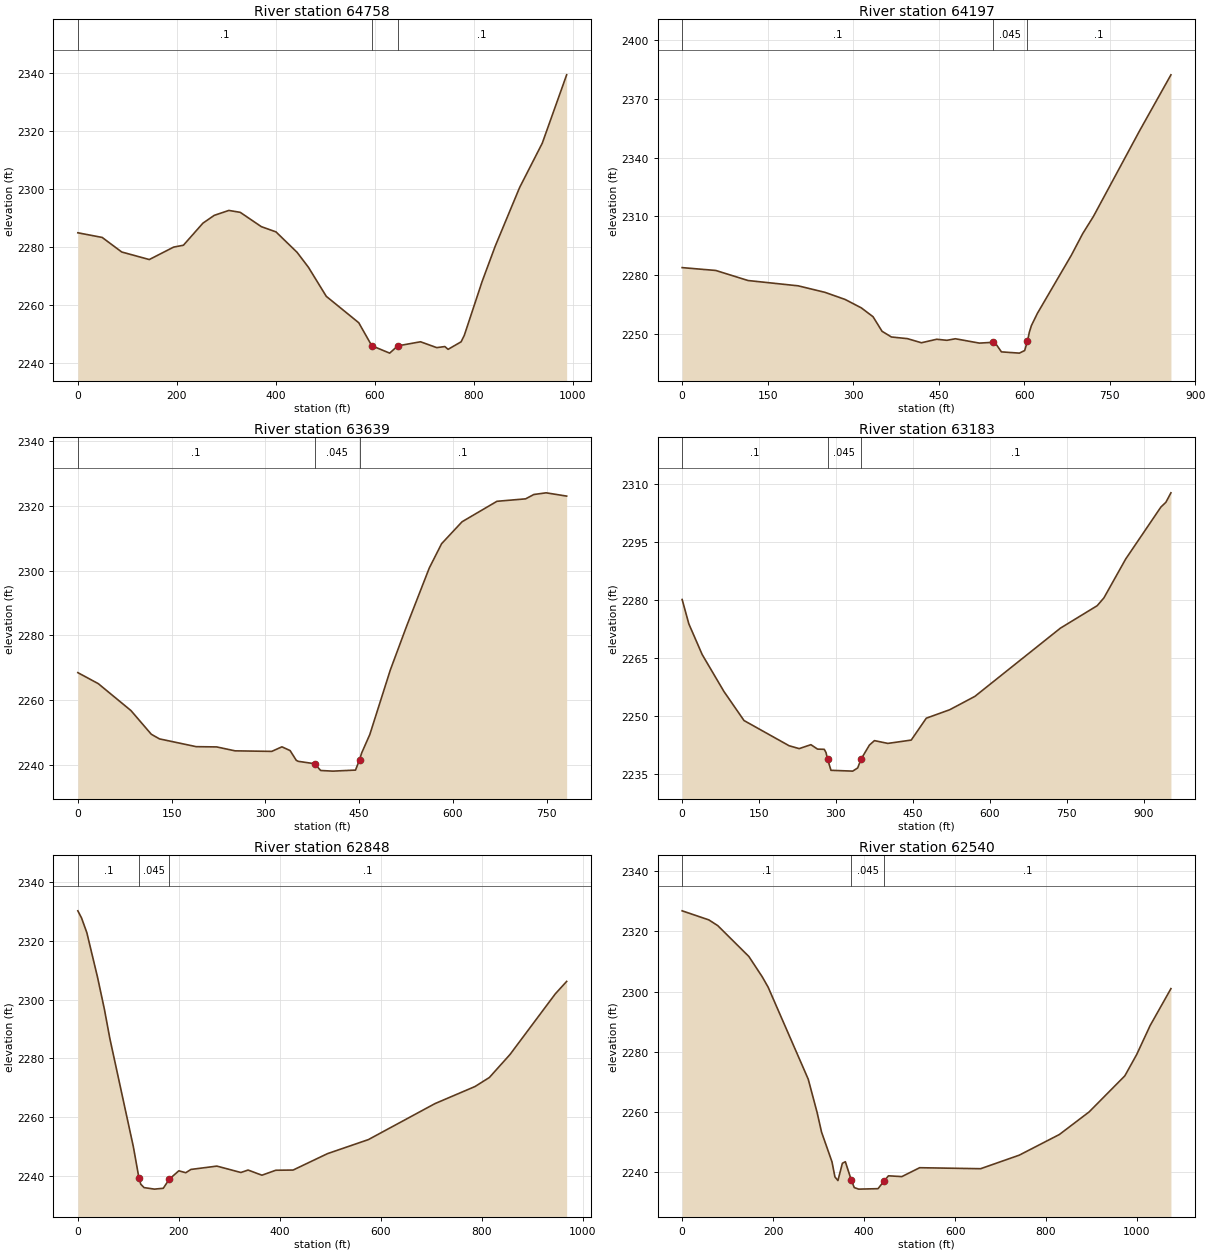
Type RM Length L Ch R = 1 ,64758   ,504.7,561.6,597.6
XS GIS Cut Line= 2
     2136545.548      221422.538     2137287.736       222073.58
#Sta/Elev= 30
       0 2284.84    49.2 2283.23    88.6 2278.21   144.3  2275.6   193.5  2279.9
   213.2 2280.54   252.6 2288.16   275.5 2290.86     305 2292.56     328  2291.9
   370.6 2286.96   400.2 2285.15   442.8  2278.1   465.8 2272.92   501.8  2262.9
   567.4 2253.78   593.7 2245.84   629.8 2243.29   646.2 2245.79   692.1 2247.21
   724.9 2245.19   741.3 2245.56   747.8  2244.6   774.1 2247.19   780.6 2249.44
   816.7 2268.09     843  2280.2   892.2 2300.43   938.1 2315.79   987.3 2339.38
#Mann= 3 ,-1 , 0
       0      .1       0   593.7    .045       0   646.2      .1       0
Bank Sta=593.7,646.2
XS Rating Curve= 0 ,0
Exp/Cntr=0.3,0.1

Type RM Length L Ch R = 1 ,64197   ,536.3,558.2,573.7
XS GIS Cut Line= 3
     2136523.847      221405.1772136651.68363781221717.256043935
     2136467.423      222203.788
#Sta/Elev= 30
       0 2283.88      59 2282.43   115.7 2277.29   203.5 2274.59   250.5 2271.27
   285.9 2267.64   314.3 2263.35   334.9 2258.82   350.7  2251.4   367.1 2248.49
   395.2 2247.64   419.8 2245.54   446.6 2247.33   464.4 2246.79   479.4 2247.58
   521.5 2245.36   546.1 2245.78   549.6  2245.3   560.1 2240.89   591.6 2240.25
   600.9 2241.58   605.7 2246.25   609.2 2251.03   612.7 2254.29   623.2 2260.53
   682.9 2290.26   702.7 2301.22   721.5 2309.99   802.8 2353.86   857.5 2382.25
#Mann= 3 ,-1 , 0
       0      .1       0   546.1    .045       0   605.7      .1       0
Bank Sta=546.1,605.7
XS Rating Curve= 0 ,0
Exp/Cntr=0.3,0.1

Type RM Length L Ch R = 1 ,63639   ,460.5,455.6,450.6
XS GIS Cut Line= 3
        2136411.      221353.094     2136108.021       221640.82
      2135852.96      221900.462
#Sta/Elev= 30
       0 2268.48    32.6 2265.09    84.9 2256.77   117.5 2249.44   130.6 2248.01
   189.3 2245.61     222 2245.53   251.4 2244.32   310.1 2244.15   326.4 2245.56
   339.5  2244.4   349.3  2241.4   352.5 2241.08   378.7 2240.34   388.4 2238.24
     408 2238.05   444.1 2238.37   450.6 2241.58   453.9 2243.64     467 2249.38
   499.8 2269.32     526 2282.93   562.1 2300.82   581.8 2308.33   614.6 2315.12
   670.3 2321.43   716.2 2322.19   729.3 2323.53     749 2324.05   781.8 2323.04
#Mann= 3 ,-1 , 0
       0      .1       0   378.7    .045       0   450.6      .1       0
Bank Sta=378.7,450.6
XS Rating Curve= 0 ,0
Exp/Cntr=0.3,0.1

Type RM Length L Ch R = 1 ,63183   ,375.6,335.5,304.7
XS GIS Cut Line= 3
     2136059.437      221005.872     2135764.298      221387.816
     2135807.701      221856.566
#Sta/Elev= 30
       0 2280.12      13 2273.83    39.1 2265.86    81.5  2256.3   120.7 2248.77
   208.7 2242.24   228.3  2241.5   251.1 2242.52   264.2 2241.37   277.2 2241.32
   280.5 2240.52   283.7 2238.79   290.3 2235.88   332.7 2235.67   342.4  2236.5
     349 2238.78   365.3 2242.42   375.1 2243.57   401.2 2242.85   446.8 2243.71
   476.2 2249.38   521.9 2251.57     571 2255.03   737.7 2272.69   809.6 2278.52
   822.7 2280.55   865.2 2290.62   933.8 2304.06   943.6 2305.31   953.4 2307.75
#Mann= 3 ,-1 , 0
       0      .1       0   283.7    .045       0     349      .1       0
Bank Sta=283.7,349
XS Rating Curve= 0 ,0
Exp/Cntr=0.3,0.1

Type RM Length L Ch R = 1 ,62848   ,312.4,307.7,300.7
XS GIS Cut Line= 3
2135575.94880495220927.1683135892135721.81115517221410.337348685
2135782.58713443221869.195992079
#Sta/Elev= 30
       0 2330.14     7.3 2327.72    17.8 2322.71    38.9 2307.63    52.6 2296.67
    63.4 2286.73   109.9 2249.99   121.1 2239.26   124.5 2237.31     131 2236.14
   151.7 2235.62   169.1 2235.91     181    2239   199.9 2241.85   213.6 2241.19
   223.9 2242.31   275.3 2243.44   322.7 2241.27     337  2242.1   364.4 2240.35
   391.8 2242.03   426.1  2242.1   494.3 2247.68     575 2252.43   706.8 2264.65
   786.2 2270.47   814.6 2273.53   855.5 2281.35   945.1 2301.93   967.6 2306.16
#Mann= 3 ,-1 , 0
       0      .1       0   121.1    .045       0     181      .1       0
Bank Sta=121.1,181
XS Rating Curve= 0 ,0
Exp/Cntr(USF)=0,0
Exp/Cntr=0.3,0.1

Type RM Length L Ch R = 1 ,62540   ,554,584.5,636
XS GIS Cut Line= 3
     2135498.197      220941.874     2135369.333      221205.524
     2135741.253      221892.395
#Sta/Elev= 30
       0 2326.82    58.7 2323.81    78.3 2321.91   146.7 2311.66   176.1 2304.91
   189.1 2301.46   277.2 2270.93   296.7 2259.88   306.5 2253.35   329.4  2243.5
   335.9 2238.48   342.5 2237.28   352.3 2243.02   358.8 2243.53   371.9 2237.42
   378.4 2234.94   388.2 2234.43   430.7 2234.58   443.8 2237.11   453.6 2238.85
     483 2238.59   522.2 2241.54   656.2 2241.21   741.2 2245.71   829.4 2252.57
   894.8 2260.07   973.2 2272.03   999.4 2279.15  1028.8 2288.71  1074.6 2300.99
#Mann= 3 ,-1 , 0
       0      .1       0   371.9    .045       0   443.8      .1       0
Bank Sta=371.9,443.8
XS Rating Curve= 0 ,0
Exp/Cntr=0.3,0.1

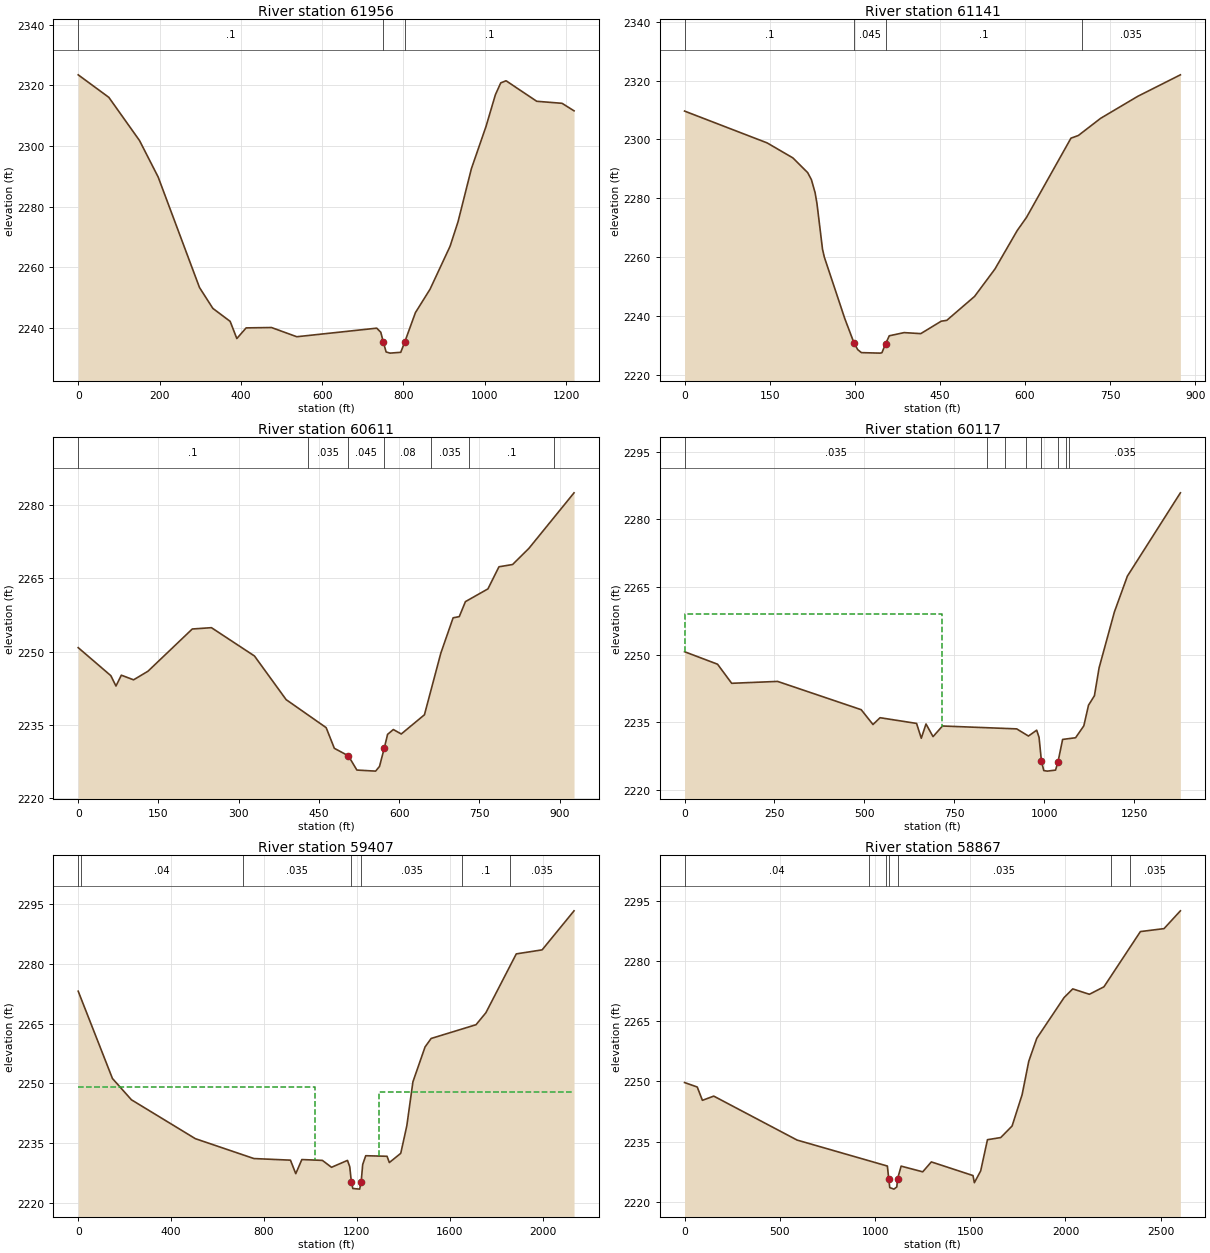
Type RM Length L Ch R = 1 ,61956   ,813,814.9,841.1
XS GIS Cut Line= 2
     2135450.454      220898.471     2134708.267      221866.353
#Sta/Elev= 30
       0  2323.5    75.4 2316.06   150.8 2301.82   196.7 2289.77   298.4  2253.3
   331.2 2246.43   373.8 2242.14   390.2 2236.47   413.1 2239.99   475.4 2240.11
   537.7 2237.07   734.4  2239.9   744.3 2238.55   750.8  2235.2   757.4 2232.05
   767.2 2231.66   793.4 2231.93   803.3 2235.35   829.5 2245.02   865.6 2252.78
   914.8 2266.94   934.4 2275.05   967.2 2292.53  1003.3 2306.52  1026.2 2316.92
  1039.4 2320.84  1052.5 2321.54  1127.9 2314.77  1190.2  2314.1  1219.7 2311.62
#Mann= 3 ,-1 , 0
       0      .1       0   750.8    .045       0   803.3      .1       0
Bank Sta=750.8,803.3
XS Rating Curve= 0 ,0
Exp/Cntr=0.3,0.1

Type RM Length L Ch R = 1 ,61141   ,524.9,529.3,527.4
XS GIS Cut Line= 3
     2135351.972      220745.455     2135176.024       220702.61
     2134569.378       221037.36
#Sta/Elev= 30
       0 2309.63   145.5 2298.82   190.9 2293.72     217 2288.72   223.6 2286.32
   230.1  2281.9   233.4  2278.2   243.2 2262.65   246.4 2259.99   282.4 2239.12
   298.8 2230.78   305.3 2228.54   311.8 2227.54   344.5 2227.37   347.8 2227.48
   354.3 2230.47   360.8 2233.26     387 2234.34   416.4    2234   452.4 2238.22
   462.2 2238.51   511.2 2246.64   547.1 2255.95   586.4 2269.04   602.7 2273.49
   681.1 2300.42   694.2 2301.34   733.4 2307.17   798.8 2314.64     874 2321.95
#Mann= 4 ,-1 , 0
       0      .1       0   298.8    .045       0   354.3      .1       0
  701.09    .035       0
Bank Sta=298.8,354.3
XS Rating Curve= 0 ,0
Exp/Cntr=0.3,0.1

Type RM Length L Ch R = 1 ,60611   ,496.1,494.4,492.3
XS GIS Cut Line= 2
2135190.38210553220103.2074740372134396.11110553220580.638474037
#Sta/Elev= 30
       0 2250.83      61  2245.1    70.6 2242.98    80.6  2245.2   103.5 2244.25
   130.4 2246.01   213.2 2254.65     249 2254.92   329.4 2249.13   388.6  2240.2
   463.4 2234.47   478.7 2230.24     5052228.694   520.8 2225.79   555.9 2225.57
   563.1 2226.53   572.12230.306   578.2 2233.09     589 2234.08   603.8 2233.17
   647.1  2237.1   677.7  2249.7   700.7 2256.94   712.2 2257.18   723.7 2260.25
   765.8 2262.86   786.4 2267.38   811.8 2267.84   842.3 2271.14   926.7 2282.51
#Mann= 7 ,-1 , 0
       0      .1       0     430    .035       0     505    .045       0
   572.1     .08       0     660    .035       0     730      .1       0
     890    .035       0
Bank Sta=505,572.1
XS Rating Curve= 0 ,0
Exp/Cntr=0.3,0.1

Type RM Length L Ch R = 1 ,60117   ,706.6,709.5,709.5
XS GIS Cut Line= 2
      2135317.25      219391.288     2134175.756      220163.858
#Sta/Elev= 30
       0 2250.63    91.7 2247.86     131 2243.62   258.6 2244.04   491.1 2237.76
   523.8 2234.47   543.5 2235.98     645 2234.71   658.1 2231.42   671.2 2234.59
   690.8 2231.78     717 2234.14   923.3  2233.5     956 2231.91   978.9 2233.21
   985.5 2231.62     992 2226.37   998.6 2224.25  1008.4 2224.12  1031.3 2224.35
  1037.9 2226.08    1051 2231.16    1087 2231.53  1109.9 2234.17    1123 2238.76
  1139.4 2240.86  1152.4 2247.06    1195 2259.48    1231 2267.41  1378.4 2285.91
#Mann= 8 ,-1 , 0
       0    .035       0     840     .07       0     890      .1       0
     950     .08       0     992    .045       0  1037.9     .08       0
    1060     .07       0    1070    .035       0
#XS Ineff= 2 , 0
          715.01 2259.11
Permanent Ineff=
       F       F
Bank Sta=992,1037.9
XS Rating Curve= 0 ,0
Exp/Cntr=0.3,0.1

Type RM Length L Ch R = 1 ,59407   ,544.2,540.5,536.8
XS GIS Cut Line= 3
       2135129.1      218723.645     2133906.659      219486.774
      2134075.93      220159.518
#Sta/Elev= 30
       0  2273.1   147.4 2251.23   229.3 2245.89   504.4 2236.15   756.6 2231.17
   913.8 2230.77   936.7 2227.38   962.9 2230.92  1051.3 2230.71  1090.6 2228.98
  1159.4 2230.71  1169.2  2229.1  1175.8 2225.39  1182.4 2223.67  1211.8 2223.51
  1218.4 2225.39  1224.9 2229.69    1238 2231.88  1329.7 2231.74  1339.6 2230.17
  1388.7 2232.48  1414.9  2239.4  1441.1  2250.4  1493.4 2259.14  1519.6 2261.26
  1712.7  2264.7  1755.2  2267.7  1886.1 2282.45  1997.4 2283.46  2134.8 2293.24
#Mann= 7 ,-1 , 0
       0      .1       0      10     .04       0     710    .035       0
  1175.8    .045       0  1218.4    .035       0 1651.09      .1       0
 1861.09    .035       0
#XS Ineff= 2 , 0
         1021.44 2248.98 1295.71         2247.96
Permanent Ineff=
       F       F
Bank Sta=1175.8,1218.4
XS Rating Curve= 0 ,0
Exp/Cntr=0.3,0.1

Type RM Length L Ch R = 1 ,58867   ,471.9,415.9,371.6
XS GIS Cut Line= 4
2134906.00239332218164.8731247192133873.81259284218949.734807238
2133701.02724119219183.3292314612134054.12230906220136.084017365
#Sta/Elev= 30
       0 2249.72    66.6 2248.61    93.7 2245.29   153.3 2246.34   590.9 2235.39
  1064.9 2228.92  1072.2  2225.7  1077.3 2223.55  1099.6 2223.17  1114.4 2223.72
  1118.3 2225.72  1137.1  2228.9  1250.4 2227.48  1295.7 2229.95  1514.4 2226.55
  1521.6 2224.77  1554.7 2227.71  1590.3 2235.48  1660.2 2236.02  1719.7  2238.9
  1772.2 2246.69  1807.2 2255.02  1849.2 2260.73  1992.6 2270.89  2038.1 2273.05
  2125.6 2271.71  2201.9 2273.57  2393.3 2287.33  2517.5 2288.07  2603.3  2292.5
#Mann= 7 ,-1 , 0
       0     .04       0     970    .035       0    1060     .07       0
  1072.2    .045       0  1118.3    .035       0 2237.25      .1       0
 2337.25    .035       0
Bank Sta=1072.2,1118.3
XS Rating Curve= 0 ,0
Exp/Cntr(USF)=0,0
Exp/Cntr=0.3,0.1

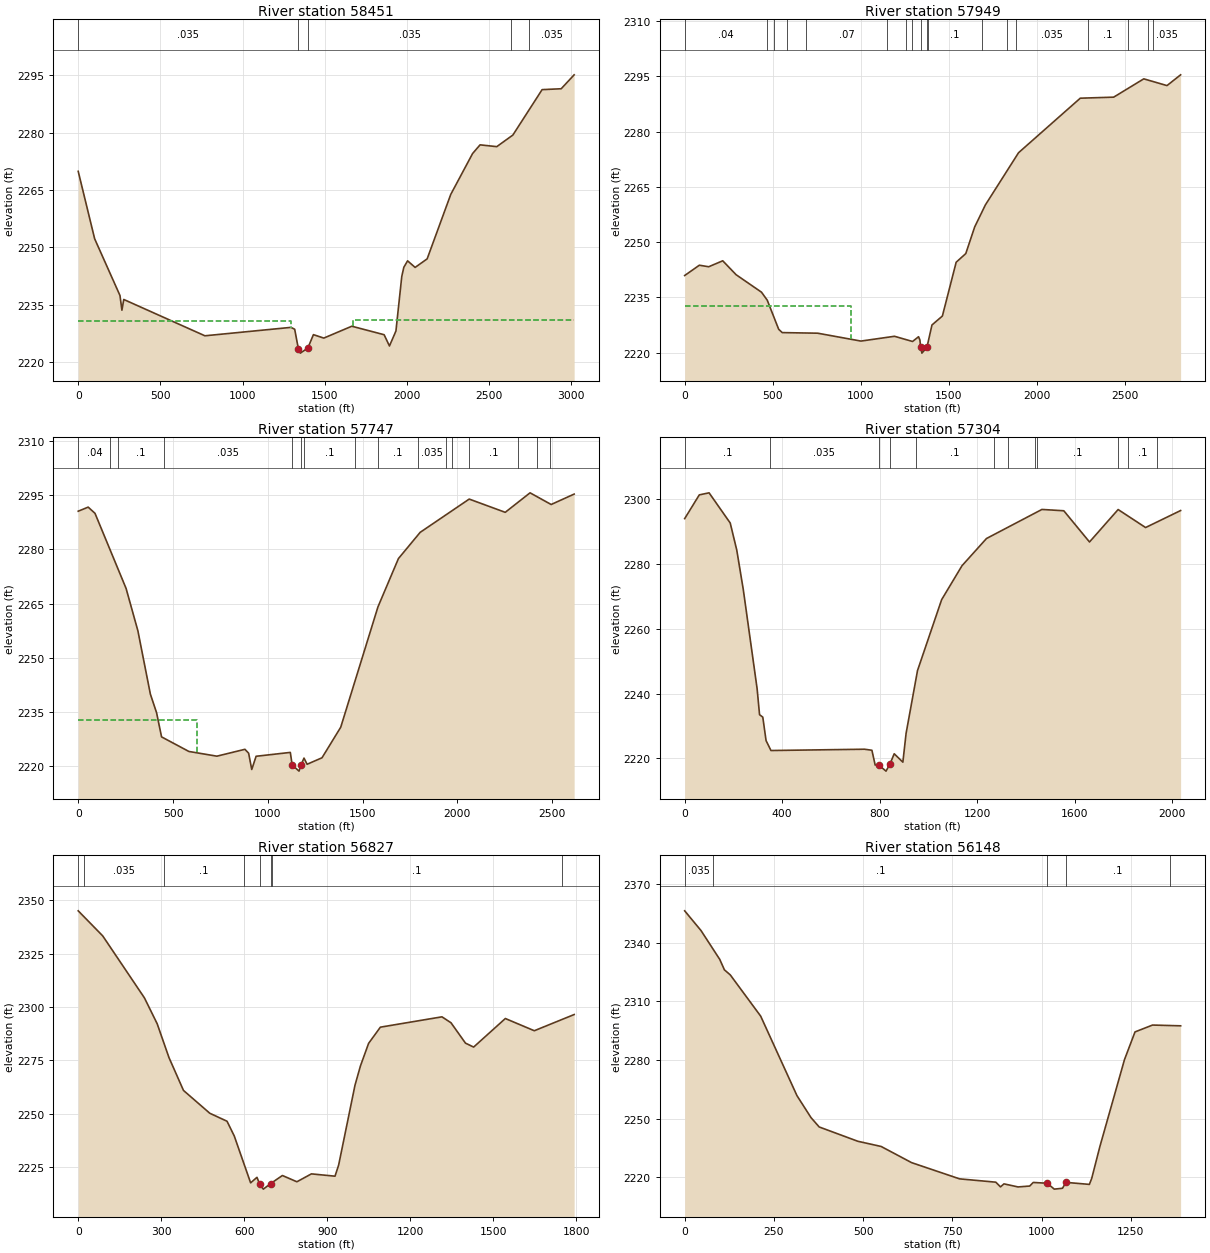
Type RM Length L Ch R = 1 ,58451   ,498.6,502.1,499.2
XS GIS Cut Line= 4
2133047.81825449217488.0498022452133867.42002417218937.580885113
2133664.17769979 219171.260479862134028.47090963220149.184507317
#Sta/Elev= 30
       0 2269.86     100 2252.24   254.2 2237.41     266 2233.57   277.3 2236.37
   771.1 2226.88    1295 2229.08  1317.6 2228.59  1340.6 2223.35  1352.1 2222.35
  1397.8 2223.69  1431.6 2227.18  1494.7 2226.28  1665.2 2229.38  1861.9 2227.16
  1894.4 2224.22  1933.8 2228.13  1969.2 2242.34  1981.7 2244.77  2004.7 2246.47
  2050.6 2244.75  2123.8 2246.98  2267.4 2263.82  2400.4 2274.51  2445.9 2276.78
  2547.5 2276.31  2645.5 2279.34  2823.5 2291.21  2939.6 2291.44  3018.5 2295.08
#Mann= 5 ,-1 , 0
       0    .035       0  1340.6    .045       0  1397.8    .035       0
  2634.9      .1       0  2744.9    .035       0
#XS Ineff= 2 , 0
         1296.85 2230.77 1671.49         2230.96
Permanent Ineff=
       F       F
Bank Sta=1340.6,1397.8
XS Rating Curve= 0 ,0
Exp/Cntr(USF)=0,0
Exp/Cntr=0.3,0.1

Type RM Length L Ch R = 1 ,57949   ,210.5,201.5,185.4
XS GIS Cut Line= 2
 2132602.9203093  217716.50728332134020.95148536  220151.1043472
#Sta/Elev= 30
       0 2240.95    83.3 2243.75   136.5 2243.33   216.2 2244.95   292.2 2241.17
   436.4 2236.43   469.2 2234.25     534 2226.37   554.1 2225.46   755.4  2225.3
  1001.3 2223.16    1192 2224.46  1294.6 2223.05  1328.7 2224.34  1336.3 2223.46
  1340.1 2221.68  1347.7 2219.89  1376.1 2221.44  1404.9 2227.53  1464.1 2229.96
  1542.4 2244.56  1596.9  2246.9  1647.6 2254.14  1708.4 2260.12  1896.8 2274.28
  2247.5 2289.08  2437.3 2289.36  2608.2 2294.33  2740.1  2292.5  2817.5 2295.42
#Mann= 18 ,-1 , 0
       0     .04       0     470    .035       0     510     .04       0
     580    .035       0     690     .07       0    1150     .04       0
    1260    .035       0    1290     .04       0  1340.1    .045       0
  1376.1     .04       0    1380      .1       0    1690    .035       0
    1830      .1       0    1880    .035       0    2290      .1       0
    2520    .035       0    2630      .1       0    2660    .035       0
#XS Ineff= 2 , 0
          942.39 2232.61
Permanent Ineff=
       F       F
Bank Sta=1340.1,1376.1
XS Rating Curve= 0 ,0
Exp/Cntr(USF)=0,0
Exp/Cntr=0.3,0.1

Type RM Length L Ch R = 1 ,57747   ,460.7,443.4,401.2
XS GIS Cut Line= 3
     2132204.295      218310.776     2133332.768       219157.13
     2134014.517      220150.728
#Sta/Elev= 30
       0 2290.57    52.5  2291.7    88.6 2289.98   252.6 2269.18   314.9 2257.43
   380.5 2239.96   413.3 2234.79   439.6  2228.1   583.9 2224.06   731.5 2222.76
   879.2 2224.66   898.8 2223.58   915.2 2219.07   938.2 2222.73  1118.6  2223.8
  1128.5 2220.33  1164.6 2218.62  1174.4 2220.22  1190.8 2222.23  1207.2 2220.52
  1285.9 2222.32  1384.4 2230.76  1580.9 2264.09  1688.9 2277.46  1803.5 2284.72
  2062.2 2293.93  2252.1 2290.26  2383.1 2295.66  2494.4 2292.43  2615.6 2295.31
#Mann= 16 ,-1 , 0
       0     .04       0     170    .035       0     210      .1       0
     450    .035       0  1128.5    .045       0  1174.4    .035       0
    1190      .1       0 1460.59    .035       0 1580.59      .1       0
 1790.59    .035       0 1940.59      .1       0 1970.59    .035       0
 2060.59      .1       0 2320.59    .035       0 2420.59      .1       0
 2490.59    .035       0
#XS Ineff= 2 , 0
          627.81 2232.68
Permanent Ineff=
       F       F
Bank Sta=1128.5,1174.4
XS Rating Curve= 0 ,0
Exp/Cntr=0.3,0.1

Type RM Length L Ch R = 1 ,57304   ,478.4,476.9,468.2
XS GIS Cut Line= 3
2132424.64341683219477.5810814562133364.86013602219296.948312744
2133999.39063124220167.690890125
#Sta/Elev= 30
       0  2293.9      60 2301.22   100.1 2301.85   186.9 2292.54   213.6 2284.24
   240.4 2272.08   297.2 2241.49   307.2 2233.48   320.5 2232.72   333.9  2225.5
     354 2222.43   738.1 2222.83   768.2 2222.51   781.6 2217.95   795.3    2218
   826.1 2216.08   841.7 2218.18   859.7 2221.43   895.2 2218.84   908.5 2227.75
   955.3 2247.07  1054.2 2268.91  1137.7 2279.37  1238.3 2287.77  1465.8 2296.73
  1555.5 2296.32    1661  2286.7  1778.4  2296.7  1891.1 2291.15  2034.8 2296.39
#Mann= 12 ,-1 , 0
       0      .1       0     350    .035       0   795.3    .045       0
   841.7    .035       0     950      .1       0 1267.41    .035       0
 1327.41      .1       0 1437.41    .035       0 1447.41      .1       0
 1777.41    .035       0 1817.41      .1       0 1937.41    .035       0
Bank Sta=795.3,841.7
XS Rating Curve= 0 ,0
Exp/Cntr(USF)=0,0
Exp/Cntr=0.3,0.1

Type RM Length L Ch R = 1 ,56827   ,659.3,678.9,687.9
XS GIS Cut Line= 3
     2132498.892       219989.27     2133514.517      219624.686
      2133972.85      220171.561
#Sta/Elev= 30
       0    2345    88.6 2333.26   239.4 2304.23   285.4 2292.13     328 2276.31
   380.5  2260.9   475.6 2250.21   537.9 2246.47   564.1 2239.55   623.2 2217.62
   646.1  2220.2     656 2216.99   669.1 2214.68   695.3 2217.25     738 2221.06
   790.4 2218.12   842.9 2221.82   928.2 2220.74   941.3 2225.92  1000.4 2263.31
    1020 2272.31  1049.6 2282.92  1092.2 2290.52  1314.8 2295.36  1347.5 2292.58
  1399.8 2283.04  1429.3  2281.2  1543.9 2294.57  1648.6 2288.85  1792.6 2296.43
#Mann= 8 ,-1 , 0
       0     .04       0      20    .035       0     310      .1       0
     600     .07       0     656    .045       0   695.3     .07       0
     700      .1       0 1749.08    .035       0
Bank Sta=656,695.3
XS Rating Curve= 0 ,0
Exp/Cntr=0.3,0.1

Type RM Length L Ch R = 1 ,56148   ,507.5,511.1,489.7
XS GIS Cut Line= 2
     2132582.225       220176.77     2133971.763      220185.559
#Sta/Elev= 30
       0 2356.28    45.9 2346.16    98.3 2331.45   111.4 2326.11   127.8 2323.53
     213 2302.45   314.6 2261.84     354 2250.59   376.9 2245.82     485 2238.52
   550.6 2235.84   635.8 2227.59   770.2  2219.3   871.8  2217.6   884.9  2215.2
   894.7 2216.74     934 2215.17   966.8 2215.63   976.6 2217.46    1016 2217.05
  1035.6 2214.05  1058.6 2214.49  1068.4  2217.5  1133.9 2216.47  1140.5 2219.54
  1163.4 2235.82  1232.3 2280.21  1261.8 2294.39  1310.9  2297.9  1389.6 2297.51
#Mann= 5 ,-1 , 0
       0    .035       0      80      .1       0    1016    .045       0
  1068.4      .1       0    1360    .035       0
Bank Sta=1016,1068.4
XS Rating Curve= 0 ,0
Exp/Cntr=0.3,0.1

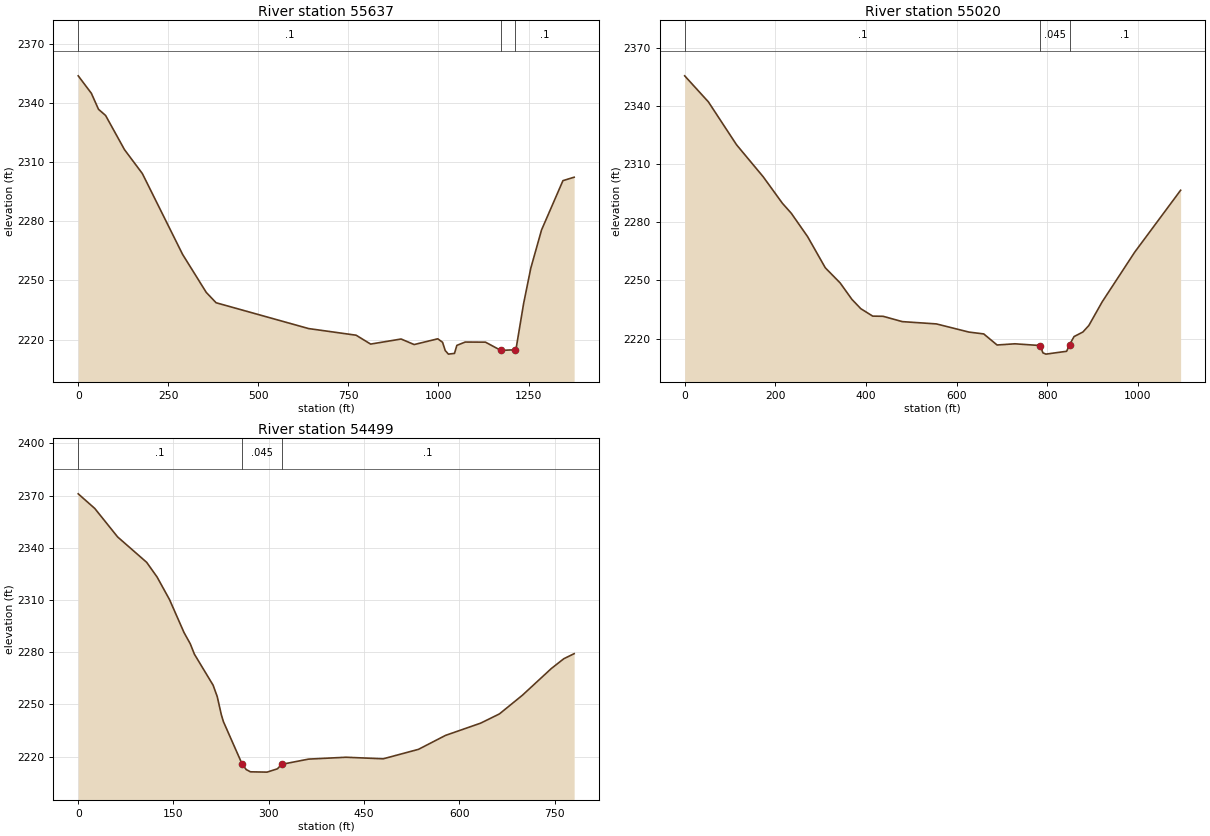
Type RM Length L Ch R = 1 ,55637   ,577.3,617.1,672.5
XS GIS Cut Line= 4
     2132604.576      220220.281     2133229.576      220263.684
 2133559.3877331220427.0610195582133938.23657963220376.733184017
#Sta/Elev= 30
       0 2353.71    36.5 2344.86    56.3 2336.76      76 2333.62   128.6 2316.26
   178.1 2304.16   289.8 2263.19   355.5 2243.92   382.8 2238.68   639.7 2225.59
   771.4 2222.23   811.8 2217.73   896.3  2220.3   932.6 2217.49   998.1 2220.41
  1011.4 2218.65  1018.8 2214.46  1027.6 2212.64  1044.5 2213.01  1051.1 2217.08
  1074.3 2218.76  1130.5 2218.71  1173.4 2214.51  1213.3 2214.87  1216.6 2216.57
  1236.4 2238.28  1256.3 2256.18  1286.1 2275.54  1345.6 2300.58  1376.7 2302.32
#Mann= 3 ,-1 , 0
       0      .1       0  1173.4    .045       0  1213.3      .1       0
Bank Sta=1173.4,1213.3
XS Rating Curve= 0 ,0
Exp/Cntr=0.3,0.1

Type RM Length L Ch R = 1 ,55020   ,552.8,520.4,491
XS GIS Cut Line= 3
     2132600.236      220268.024     2133164.472      220302.747
     2133229.576       220827.92
#Sta/Elev= 30
       0 2355.45    52.3 2342.04   114.4 2319.94   173.2 2303.45   215.7 2289.76
   235.3 2284.61   271.2 2272.61   310.4  2256.5   343.1 2248.71   369.2 2240.21
   388.8 2235.42     415 2231.61   437.9 2231.52   480.3 2228.77   555.5 2227.59
   627.4 2223.38     660 2222.43   689.4 2216.73   728.6 2217.34   784.2 2216.46
   790.7 2212.67   797.2 2212.02     843 2213.49   849.5 2216.93   859.3 2221.06
   878.9 2223.43     892 2226.79   921.4 2238.97   993.2 2264.58  1094.5 2296.48
#Mann= 3 ,-1 , 0
       0      .1       0   784.2    .045       0   849.5      .1       0
Bank Sta=784.2,849.5
XS Rating Curve= 0 ,0
Exp/Cntr=0.3,0.1

Type RM Length L Ch R = 1 ,54499   ,469.2,440.9,409.4
XS GIS Cut Line= 2
     2132487.388      220393.893     2133095.027      220884.344
#Sta/Elev= 30
       0 2370.98    26.1 2362.56    62.1 2346.19   107.8  2331.6   124.2 2323.17
   143.8 2310.18   166.6 2291.26   176.4 2284.82     183 2278.78   212.4 2261.01
   218.9 2254.43   225.4 2243.96   228.7 2239.99   258.1 2215.67   264.6 2212.49
   271.2 2211.21   297.3 2211.03   313.7 2212.93   320.2 2215.49   362.7 2218.51
   421.5 2219.58   480.3 2218.69   535.8 2224.13   578.3 2232.13   633.8  2239.2
   663.2 2244.48   699.2 2255.15   744.9 2270.55   764.5 2276.18   780.9 2279.11
#Mann= 3 ,-1 , 0
       0      .1       0   258.1    .045       0   320.2      .1       0
Bank Sta=258.1,320.2
XS Rating Curve= 0 ,0
Exp/Cntr=0.3,0.1