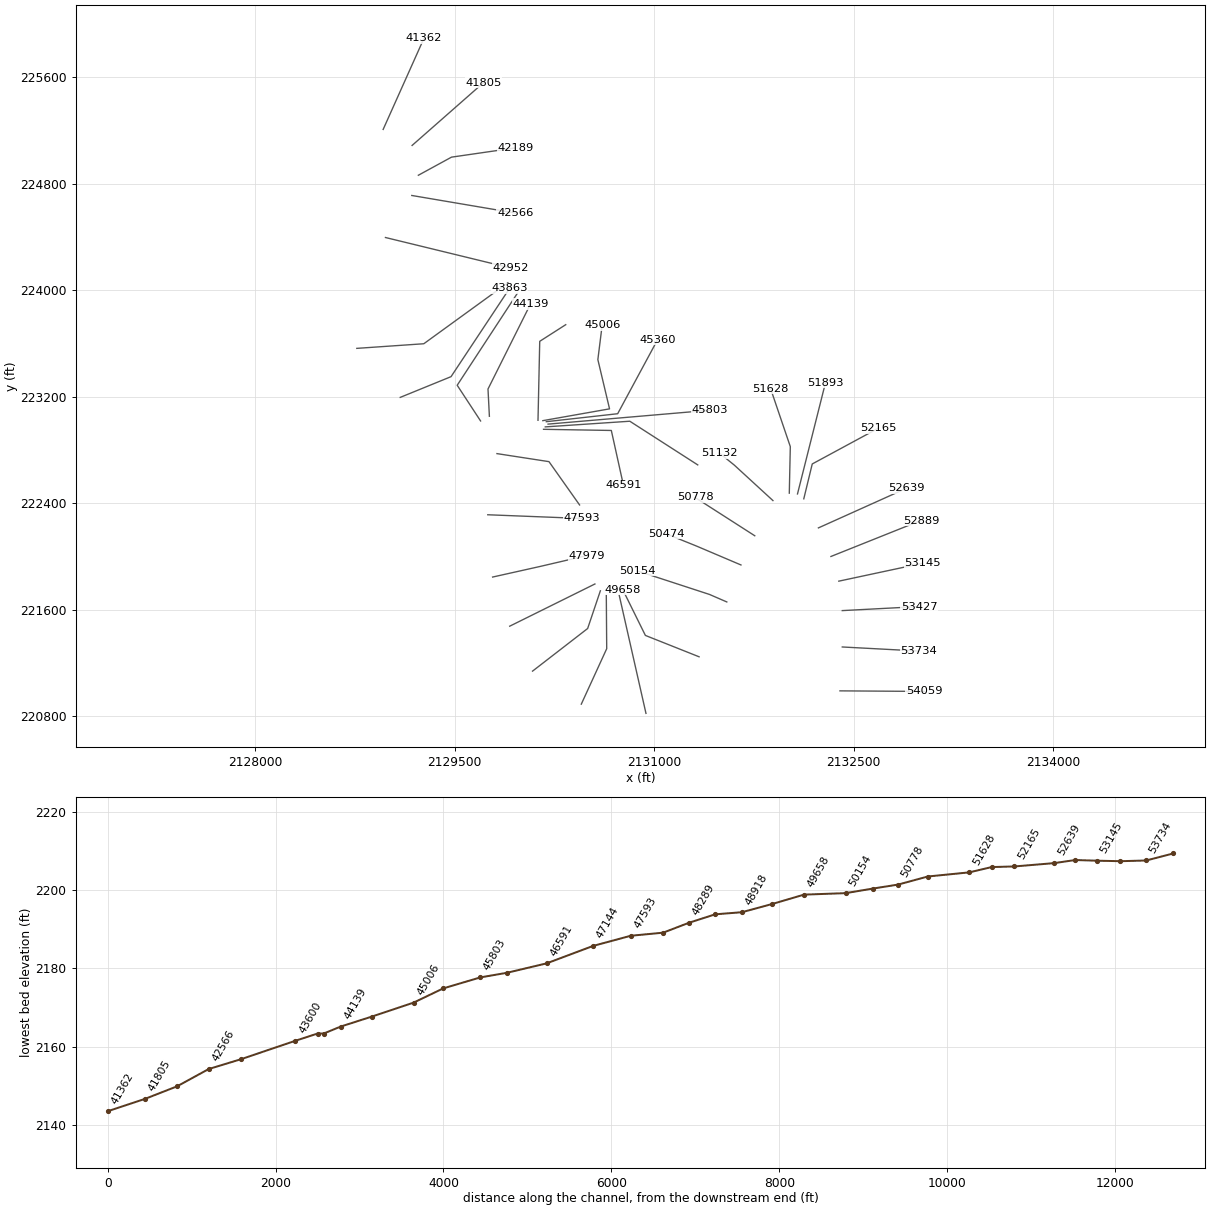
HEC-RAS study SECONDCK.prj: SECONDCK

--- SECONDCK.g01 (geometry) --- (continued)

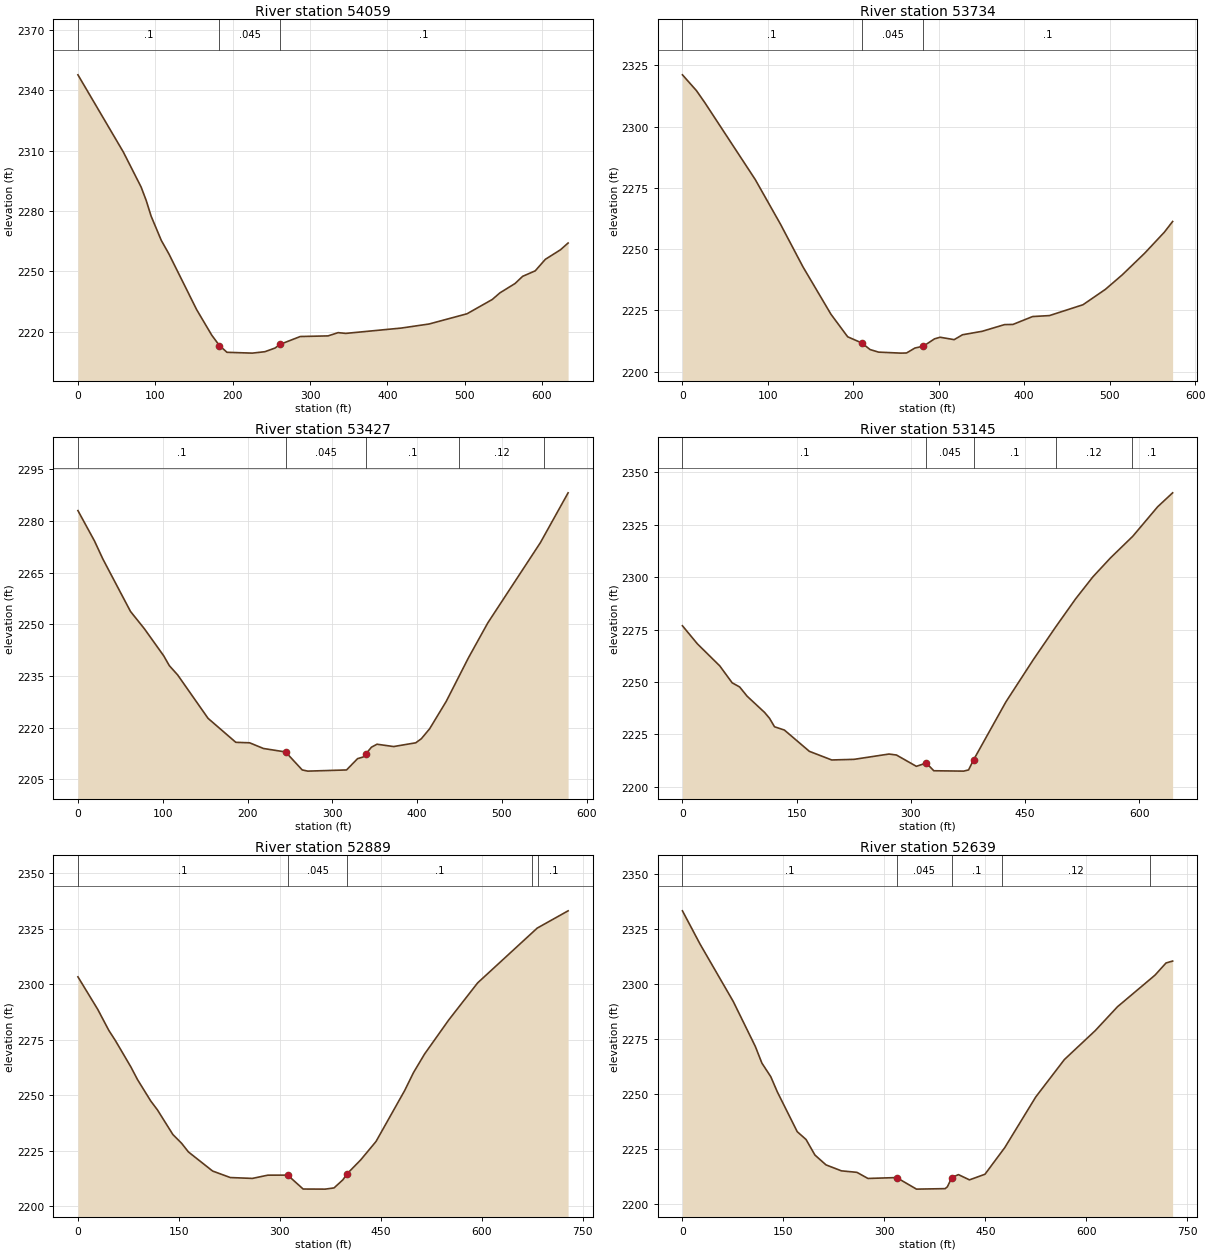
Type RM Length L Ch R = 1 ,54059   ,325,324.2,320.1
XS GIS Cut Line= 2
     2132396.243      220988.511     2133029.923       220984.17
#Sta/Elev= 30
       0 2347.79    58.8 2309.33    81.7 2291.98    88.2 2285.37    94.7 2277.43
   107.8 2265.42   117.6 2258.73   153.5 2230.99   173.1 2218.25   182.9 2213.16
   192.7 2209.78   225.4 2209.37   241.7 2210.08   254.8 2211.89   261.3 2213.72
   287.4 2217.63   323.4 2217.94   336.4 2219.56   346.2 2219.18   418.1 2221.84
     454 2223.86     503 2228.94   535.7 2236.06   545.5 2239.33   565.1 2243.99
   574.9 2247.56   591.2  2250.3   604.3 2256.03   623.9 2260.79   633.7 2264.14
#Mann= 3 ,-1 , 0
       0      .1       0   182.9    .045       0   261.3      .1       0
Bank Sta=182.9,261.3
XS Rating Curve= 0 ,0
Exp/Cntr=0.3,0.1

Type RM Length L Ch R = 1 ,53734   ,299.2,307.4,313
XS GIS Cut Line= 2
     2132413.604      221318.372      2132986.52       221287.99
#Sta/Elev= 30
       0 2321.15    16.4  2314.7    26.2 2309.79    85.2 2278.42   114.7 2260.22
     141 2242.81   173.8 2223.44   193.4 2214.22   209.8 2211.73   219.6 2209.02
   229.5 2207.97   255.7 2207.56   262.3 2207.62   272.1 2209.64   281.9 2210.38
   295.1  2213.4   301.6 2214.04     318 2213.06   327.8 2215.06   350.8 2216.47
     377  2219.2   386.8 2219.27   409.8 2222.49   429.5 2222.88   468.8 2227.31
     495 2233.59   514.7  2239.5   540.9 2248.31   563.9 2256.88   573.7 2261.29
#Mann= 3 ,-1 , 0
       0      .1       0   209.8    .045       0   281.9      .1       0
Bank Sta=209.8,281.9
XS Rating Curve= 0 ,0
Exp/Cntr=0.3,0.1

Type RM Length L Ch R = 1 ,53427   ,278.7,282.2,286.6
XS GIS Cut Line= 2
     2132413.604      221591.809     2132990.861      221622.191
#Sta/Elev= 30
       0 2282.98    19.6 2274.14    29.4 2268.94      62 2253.72    78.4 2248.69
   101.2 2240.83   107.8 2237.99   117.6  2235.3   153.5 2222.69   186.2 2215.74
   202.5  2215.6   218.8 2213.95   244.9 2212.94   264.5 2207.73   271.1 2207.38
   316.8 2207.72   329.8    2211   336.4 2211.48   339.6 2212.38   346.2 2214.33
   352.7 2215.19   372.3 2214.51   398.4  2215.6     405 2216.78   414.8 2219.67
   434.4 2227.64   460.5 2240.23   483.4  2250.4   545.4 2273.68   578.1 2288.14
#Mann= 5 ,-1 , 0
       0      .1       0   244.9    .045       0   339.6      .1       0
     450     .12       0     550      .1       0
Bank Sta=244.9,339.6
XS Rating Curve= 0 ,0
Exp/Cntr=0.3,0.1

Type RM Length L Ch R = 1 ,53145   ,247.3,256.1,263.6
XS GIS Cut Line= 2
     2132387.562      221813.163     2133016.902      221947.712
#Sta/Elev= 30
       0 2276.83    19.6 2268.22      49  2257.7    65.3 2249.62    75.1 2247.65
    84.9 2243.25   107.8 2235.52   114.3 2232.73   120.9 2228.66   133.9 2227.09
   166.6 2216.96     196 2212.83   225.4 2213.13   271.2 2215.66     281 2215.19
   307.1  2209.8   320.2 2211.38     330 2207.69   369.2 2207.51   375.7 2208.09
   382.2 2212.86   424.7 2240.53   460.6 2260.62     490 2276.23   516.2 2289.66
     539  2300.2   561.9 2309.15   591.3 2319.52     624  2333.6   643.6 2340.23
#Mann= 5 ,-1 , 0
       0      .1       0   320.2    .045       0   382.2      .1       0
     490     .12       0     590      .1       0
Bank Sta=320.2,382.2
XS Rating Curve= 0 ,0
Exp/Cntr=0.3,0.1

Type RM Length L Ch R = 1 ,52889   ,247.5,250,251.9
XS GIS Cut Line= 3
     2132328.418       221998.73     2132666.384      222133.916
      2133004.35      222269.101
#Sta/Elev= 30
       0 2303.36    29.5 2288.66    45.9 2279.22    55.8 2274.57    78.7 2262.72
    88.5 2257.04   108.2 2247.38     118 2243.44     141  2232.3   154.1  2228.3
     164 2224.47     200 2215.84   226.3  2212.9   259.1 2212.51     282 2213.97
   311.5    2214   334.5 2207.72   367.3 2207.68   380.4 2208.23   393.5 2211.88
   400.1  2214.7   419.8  2220.8   442.7 2229.15   485.3 2252.13   498.4 2260.21
   514.8 2268.56   550.9    2284   593.6 2300.62   682.1 2325.32     728 2333.11
#Mann= 5 ,-1 , 0
       0      .1       0   311.5    .045       0   400.1      .1       0
     674     .12       0     684      .1       0
Bank Sta=311.5,400.1
XS Rating Curve= 0 ,0
Exp/Cntr=0.3,0.1

Type RM Length L Ch R = 1 ,52639   ,469.5,473.6,478.4
XS GIS Cut Line= 3
     2132234.238      222213.547     2132566.177       222362.92
     2132898.116      222512.293
#Sta/Elev= 30
       0 2333.37    26.2 2318.23    75.4 2292.21   108.2 2271.77     118 2264.16
   131.2 2257.98     141 2251.02   170.5 2232.99   183.6 2229.44   196.8 2222.37
   213.2 2217.91   236.1  2215.2   259.1 2214.52   275.5 2211.74   318.1 2212.14
   347.6 2206.89   390.2 2207.11   393.5 2207.98   400.1 2212.16   409.9 2213.48
   426.3  2211.1   449.3 2213.65   478.8  2225.8   524.7 2248.77   567.3  2265.8
   613.2 2278.96     646 2289.75   701.8 2304.13   718.2 2309.67     728 2310.54
#Mann= 5 ,-1 , 0
       0      .1       0   318.1    .045       0   400.1      .1       0
     474     .12       0     694      .1       0
Bank Sta=318.1,400.1
XS Rating Curve= 0 ,0
Exp/Cntr=0.3,0.1

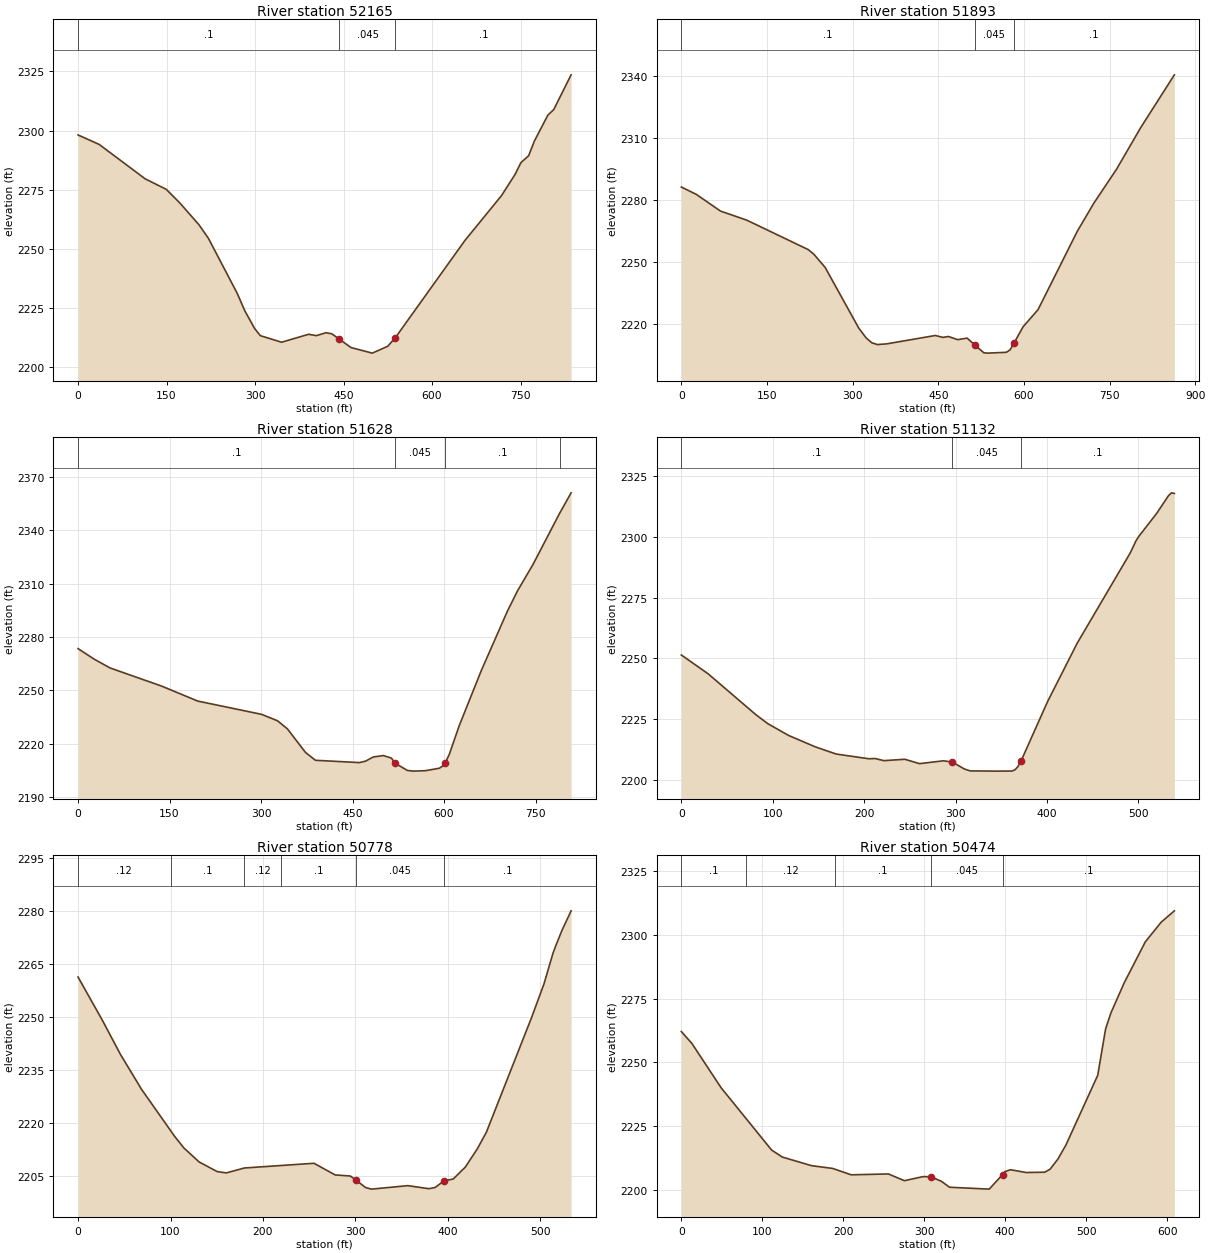
Type RM Length L Ch R = 1 ,52165   ,233.2,272,311.5
XS GIS Cut Line= 3
     2132124.284      222432.122     2132187.909       222694.24
     2132685.759      222963.369
#Sta/Elev= 30
       0 2298.15    35.8 2294.15   113.7 2279.64   149.5 2275.19   172.2 2269.52
   204.7 2260.31     221 2254.49   269.7  2231.3   282.8 2223.84   299.2 2216.45
     309 2213.41     345 2210.64   390.8    2214   403.8 2213.42   420.2 2214.65
     430 2214.21   443.1 2211.89   462.7 2208.39   498.7 2206.04   524.9 2208.93
     538 2212.63   655.7  2253.6   717.9  2272.6   740.8 2281.52   750.6 2286.45
   763.7 2289.39   773.5  2295.6   796.4 2306.56   806.2 2308.84   835.7 2323.54
#Mann= 3 ,-1 , 0
       0      .1       0   443.1    .045       0     538      .1       0
Bank Sta=443.1,538
XS Rating Curve= 0 ,0
Exp/Cntr=0.3,0.1

Type RM Length L Ch R = 1 ,51893   ,236.8,265.5,292.8
XS GIS Cut Line= 2
     2132076.946      222468.767     2132287.736      223306.219
#Sta/Elev= 30
       0 2286.28    26.2 2282.72    68.7 2274.62   114.5 2270.25   222.4 2255.97
   232.2 2253.73   251.9 2247.35   310.8 2217.98   323.8 2213.22   333.6 2210.88
   343.5 2210.02   359.8 2210.37   444.9 2214.42     458  2213.5   467.8 2213.93
   484.1  2212.4   500.5 2213.15   513.6 2209.94   529.9 2206.04   536.5 2205.88
   569.2 2206.28   575.7 2207.44   582.3 2210.54   598.6 2218.63   624.8 2226.93
   693.5 2264.82   722.9 2278.62   762.2 2294.84   804.7 2315.06   863.6 2340.58
#Mann= 3 ,-1 , 0
       0      .1       0   513.6    .045       0   582.3      .1       0
Bank Sta=513.6,582.3
XS Rating Curve= 0 ,0
Exp/Cntr=0.3,0.1

Type RM Length L Ch R = 1 ,51628   ,469.2,495.2,520.4
XS GIS Cut Line= 3
     2132015.345      222474.651     2132022.979      222824.448
     2131875.409      223258.476
#Sta/Elev= 30
       0 2273.41    26.2 2267.54    52.3 2262.57   137.3  2252.3   196.2 2243.92
   300.8 2236.47     327 2232.84   343.3 2228.26   372.8 2215.06   389.2 2210.62
   461.2 2209.33     471  2210.1   484.1  2212.5   500.5 2213.28   513.6 2211.88
   520.2 2208.91   539.8 2204.92   549.6 2204.53   569.3 2204.77   592.2 2206.15
   598.7 2207.55     602 2209.24   608.6 2213.94   624.9  2230.1     661 2261.02
   703.5 2294.19   719.9 2305.56   746.1  2320.9   788.7    2349   808.3 2361.02
#Mann= 4 ,-1 , 0
       0      .1       0   520.2    .045       0     602      .1       0
  789.88     .04       0
Bank Sta=520.2,602
XS Rating Curve= 0 ,0
Exp/Cntr=0.3,0.1

Type RM Length L Ch R = 1 ,51132   ,346,354.7,362
XS GIS Cut Line= 3
     2131892.385       222418.94     2131601.972      222685.559
     2131489.125      222776.705
#Sta/Elev= 30
       0 2251.36    29.3  2243.6    81.4 2226.78    94.5 2223.06   117.3 2218.18
   146.6 2213.47   169.4 2210.51   205.3 2208.56   211.8 2208.68   221.6 2207.79
   244.4 2208.36   260.6 2206.56   286.7 2207.72   296.5 2207.21   309.5 2204.36
     316 2203.56   345.4 2203.47   361.7 2203.51   364.9    2204   368.2 2205.35
   371.4  2207.5   400.7 2232.22   432.9 2256.15     491 2293.42   497.4  2298.5
   500.6 2300.36     520 2309.78   532.8 2317.02   536.1 2318.22   539.3 2317.97
#Mann= 3 ,-1 , 0
       0      .1       0   296.5    .045       0   371.4      .1       0
Bank Sta=296.5,371.4
XS Rating Curve= 0 ,0
Exp/Cntr=0.3,0.1

Type RM Length L Ch R = 1 ,50778   ,292.2,303.4,311.9
XS GIS Cut Line= 2
      2131755.76      222154.429     2131306.833      222442.504
#Sta/Elev= 30
       0 2261.38    26.2 2249.21    45.8 2239.53    68.7 2229.62   104.7 2216.25
   114.5 2213.04   130.9  2209.1   150.5 2206.36   160.4 2205.99     180 2207.38
   255.2 2208.71   278.2 2205.41   294.5 2205.11   301.1 2203.88   310.9 2201.87
   317.4  2201.4   356.7 2202.38   379.6 2201.52   386.2 2201.86     396 2203.75
   405.8 2204.25   418.9 2207.62     432 2212.82   441.8 2217.54   490.9 2250.11
     504 2259.41   513.8 2268.14     517 2270.36   523.6 2274.64   533.4 2280.12
#Mann= 6 ,-1 , 0
       0     .12       0     100      .1       0     180     .12       0
     220      .1       0   301.1    .045       0     396      .1       0
Bank Sta=301.1,396
XS Rating Curve= 0 ,0
Exp/Cntr=0.3,0.1

Type RM Length L Ch R = 1 ,50474   ,314.3,320.2,321.7
XS GIS Cut Line= 3
     2131652.018      221934.918     2131317.017      222077.294
     2131089.819      222169.066
#Sta/Elev= 30
       0 2262.07    13.1 2257.38    49.2 2240.03   111.5 2215.68   124.6 2212.95
   160.7 2209.57   186.9 2208.48   209.9 2205.98   255.8 2206.32   275.5 2203.68
   298.4 2205.27   308.2 2205.23   321.4 2203.42   331.2 2201.12   380.3 2200.38
   396.7 2206.05   399.9 2207.24   406.5 2207.97   426.1 2206.88   448.9    2207
   455.5 2208.19   465.3 2212.22   475.1 2217.69   514.3 2244.92   524.1 2263.17
   530.6 2269.35     547 2281.12   573.1 2297.18   592.7 2304.87     609 2309.32
#Mann= 5 ,-1 , 0
       0      .1       0      80     .12       0     190      .1       0
   308.2    .045       0   396.7      .1       0
Bank Sta=308.2,396.7
XS Rating Curve= 0 ,0
Exp/Cntr=0.3,0.1

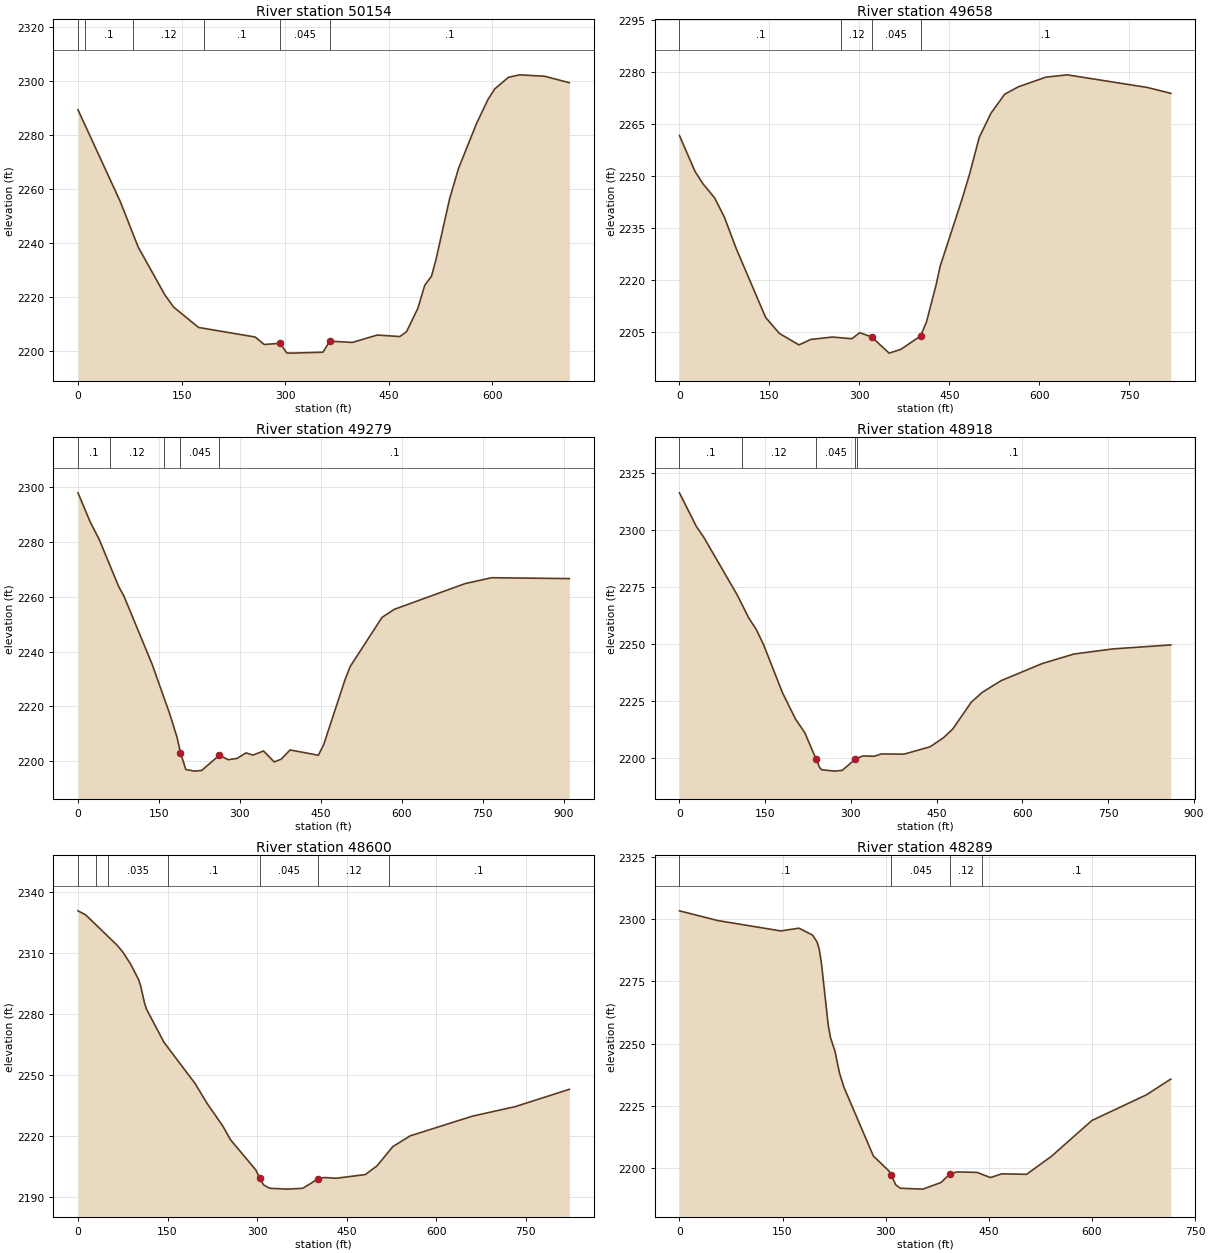
Type RM Length L Ch R = 1 ,50154   ,494.3,496,493.4
XS GIS Cut Line= 3
     2131545.548      221656.913      2131415.34      221713.337
     2130873.938      221890.083
#Sta/Elev= 30
       0 2289.33    61.3 2255.29    87.1 2238.54   125.8 2220.76   138.7 2216.21
   174.6 2208.72   256.5 2205.19   269.6 2202.42   292.5 2202.85   302.3 2199.29
   308.8 2199.22   354.7 2199.56   364.5 2203.66   397.2 2203.18   433.2 2205.91
     466 2205.36   475.8 2207.22   492.1 2215.85     502 2224.33   511.8 2227.71
   518.3 2233.85     538 2256.33     551 2267.67   577.2 2284.37   593.6 2293.16
   603.4 2297.06   623.1 2301.34   639.4 2302.27   675.4 2301.75   711.4 2299.35
#Mann= 6 ,-1 , 0
       0     .12       0      10      .1       0      80     .12       0
  181.91      .1       0   292.5    .045       0   364.5      .1       0
Bank Sta=292.5,364.5
XS Rating Curve= 0 ,0
Exp/Cntr=0.3,0.1

Type RM Length L Ch R = 1 ,49658   ,407.1,379.2,314.1
XS GIS Cut Line= 3
     2131337.215      221244.587     2130933.569      221405.177
     2130763.215      221749.845
#Sta/Elev= 30
       0 2261.64    26.1 2251.23    39.2 2247.72    58.8  2243.6    75.1    2238
    94.7 2228.98   143.7 2209.12   166.6 2204.52   199.2 2201.21   218.8 2202.79
   254.8 2203.48   287.4    2203   300.5 2204.74   320.1 2203.54   349.5 2198.84
   369.1 2199.94   401.8 2203.78   411.6 2207.79   427.9 2218.66   434.4 2223.87
   470.3 2242.92   483.3 2250.37   499.6  2261.1   519.1 2268.06   541.9 2273.55
   564.8  2275.7   610.4 2278.48   646.2 2279.16   779.8 2275.51   818.9 2273.82
#Mann= 4 ,-1 , 0
       0      .1       0     270     .12       0   320.1    .045       0
   401.8      .1       0
Bank Sta=320.1,401.8
XS Rating Curve= 0 ,0
Exp/Cntr=0.3,0.1

Type RM Length L Ch R = 1 ,49279   ,382.1,360.4,329.5
XS GIS Cut Line= 2
     2130937.909       220819.24     2130736.802      221707.039
#Sta/Elev= 30
       0 2297.81    22.9  2287.1    39.3 2280.84    75.3 2263.72    85.1 2260.22
   137.5  2235.3   170.3  2217.1   183.4 2208.84   189.9 2203.21   199.7 2197.05
   216.1 2196.45   229.2 2196.71     262 2202.25   278.3 2200.61   294.7 2201.08
   311.1 2203.09   324.2 2202.29   343.8 2203.79   363.5  2199.8   376.6 2200.82
   392.9 2204.17   445.3 2202.23   455.2 2206.11   494.4 2229.58   504.3 2234.56
   563.2 2252.44   586.1 2255.39   717.1 2264.75   766.2 2266.89   910.3 2266.57
#Mann= 5 ,-1 , 0
       0      .1       0      60     .12       0     160      .1       0
   189.9    .045       0     262      .1       0
Bank Sta=189.9,262
XS Rating Curve= 0 ,0
Exp/Cntr=0.3,0.1

Type RM Length L Ch R = 1 ,48918   ,336.3,318.1,291.2
XS GIS Cut Line= 3
     2130451.798      220888.684      2130642.77      221305.351
     2130639.744      221706.596
#Sta/Elev= 30
       0 2316.12    29.5 2301.44    42.6 2296.66   101.5 2271.24   121.1 2261.43
   134.2 2256.45   147.3  2249.6   180.1 2228.73     203 2217.16   219.4  2211.1
     239 2199.62   245.5  2195.8   248.8 2194.96   271.7 2194.35   284.8 2194.69
   307.8 2199.63   320.8 2200.99   340.5 2200.84   353.6 2201.88   392.9 2201.78
   438.7 2205.03   461.6  2208.9   477.9 2212.71   510.5 2224.52   530.1 2228.89
   562.7 2233.94   634.5 2241.41     690 2245.58   758.5 2247.83   859.6 2249.57
#Mann= 5 ,-1 , 0
       0      .1       0     110     .12       0     239    .045       0
   307.8     .12       0     310      .1       0
Bank Sta=239,307.8
XS Rating Curve= 0 ,0
Exp/Cntr=0.3,0.1

Type RM Length L Ch R = 1 ,48600   ,321,311.3,297.7
XS GIS Cut Line= 3
     2130085.305      221136.847     2130499.541      221457.261
     2130595.117      221740.687
#Sta/Elev= 30
       0 2330.75    13.1  2328.7    65.5 2313.84    75.3 2310.38    88.4 2304.43
   101.5 2296.91   104.7 2294.14   111.3 2285.54   114.6 2282.42     144 2266.06
   196.4 2245.65     216 2236.07   242.2 2224.99   255.3 2218.16   297.8 2203.22
   304.4  2199.1   310.9 2195.86   320.8 2194.24   350.2 2193.81   376.4 2194.22
   402.6 2198.94   412.4 2199.54     432 2199.16   481.1 2200.97   500.8 2205.28
     527 2214.68   556.2 2220.02   660.2  2229.7   731.8 2234.38   822.8 2242.93
#Mann= 7 ,-1 , 0
       0    .035       0      30      .1       0      50    .035       0
     150      .1       0   304.4    .045       0   402.6     .12       0
     520      .1       0
Bank Sta=304.4,402.6
XS Rating Curve= 0 ,0
Exp/Cntr=0.3,0.1

Type RM Length L Ch R = 1 ,48289   ,318.7,309.6,296.3
XS GIS Cut Line= 2
     2129913.604      221474.622     2130554.057      221791.886
#Sta/Elev= 30
       0 2303.25    55.7 2299.35   147.5 2295.19   173.8 2296.29   193.4 2293.56
     200 2290.85   203.3 2287.96   206.6 2282.08   216.4 2257.43   219.7 2252.39
   226.2 2246.98   232.8 2238.22   239.3  2232.5     282 2204.98   304.9 2198.89
   308.2 2197.16   314.7 2193.36   321.3 2192.02   354.1 2191.67   380.3 2194.31
   393.4 2197.71   403.3 2198.56   432.8 2198.38   452.4 2196.31   468.8  2197.8
   504.9 2197.61     541 2204.82     600 2219.21   678.7 2229.41   714.7  2235.8
#Mann= 4 ,-1 , 0
       0      .1       0   308.2    .045       0   393.4     .12       0
     440      .1       0
Bank Sta=308.2,393.4
XS Rating Curve= 0 ,0
Exp/Cntr=0.3,0.1

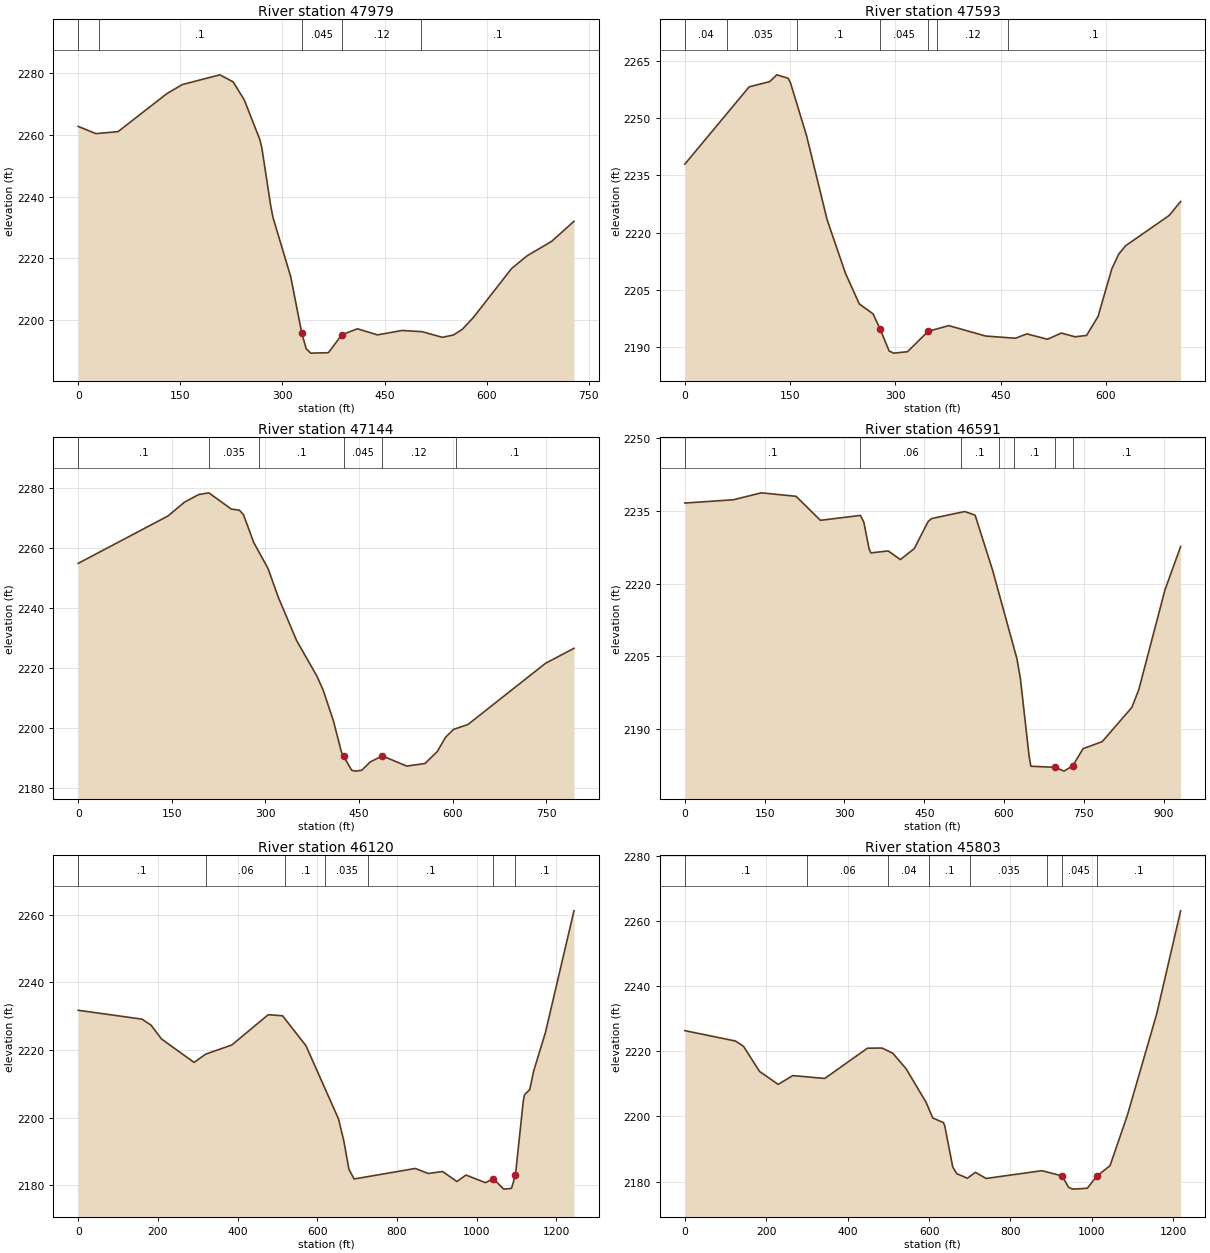
Type RM Length L Ch R = 1 ,47979   ,396.9,386.1,373.8
XS GIS Cut Line= 3
     2129785.128      221844.026     2130140.621      221923.387
     2130495.029      222006.023
#Sta/Elev= 30
       0 2262.78      26 2260.43    58.5 2261.07   130.1  2273.4   152.8 2276.36
   208.1 2279.53   227.6 2277.24   243.9  2271.4   266.7 2258.56   269.9  2255.6
   282.9  2236.8   286.2 2233.14   312.2  2213.9   328.5 2195.52     335 2190.52
   341.5 2189.12   367.5 2189.26   387.2 2195.07   410.1 2197.03   439.6 2195.05
   475.7 2196.48   505.2 2196.09   534.7 2194.26   551.1    2195   564.2 2196.85
   580.6 2200.74   636.4 2216.57   659.3 2220.73   695.4 2225.43   728.2 2231.94
#Mann= 5 ,-1 , 0
       0     .04       0      30      .1       0   328.5    .045       0
   387.2     .12       0  504.24      .1       0
Bank Sta=328.5,387.2
XS Rating Curve= 0 ,0
Exp/Cntr=0.3,0.1

Type RM Length L Ch R = 1 ,47593   ,479,449.4,400.6
XS GIS Cut Line= 2
     2129748.673      222312.295      2130454.78      222284.547
#Sta/Elev= 30
       0 2237.96    91.6 2258.24     121 2259.62   130.9  2261.4   147.2  2260.5
   150.5 2259.33   173.4 2245.47   202.8 2223.32     229 2209.25   248.6 2201.26
   268.3 2198.62   278.1 2194.74   291.2 2188.88   297.7 2188.33   317.3  2188.7
   346.8 2194.07   376.2 2195.55   428.6 2192.82   471.1 2192.24   487.5 2193.38
   516.9 2191.97   536.5  2193.6   556.2 2192.62   572.5 2192.97   588.9 2197.96
   608.5 2210.44   618.3 2214.31   628.1 2216.51   690.3 2224.48   706.6 2228.14
#Mann= 7 ,-1 , 0
       0     .04       0      60    .035       0     160      .1       0
   278.1    .045       0   346.8      .1       0     360     .12       0
     460      .1       0
Bank Sta=278.1,346.8
XS Rating Curve= 0 ,0
Exp/Cntr=0.3,0.1

Type RM Length L Ch R = 1 ,47144   ,559.6,552.5,520.6
XS GIS Cut Line= 3
     2129817.764      222771.954     2130208.743      222711.601
     2130438.777       222386.08
#Sta/Elev= 30
       0  2254.8   143.9 2270.56     170 2275.11   192.9 2277.67   209.2 2278.25
   245.2 2272.86   258.3 2272.47   264.8 2270.98   281.2 2261.73   304.1  2253.1
   320.4 2243.61   349.8 2229.18   382.5 2217.27   392.3 2212.72   408.7 2202.55
   421.8 2192.01     425 2190.77   438.1 2186.02   444.6 2185.73   454.4 2186.04
   467.5 2188.74   487.1 2190.81   526.3  2187.4   555.7 2188.28   575.3 2192.26
   588.4 2196.97   601.4 2199.62   624.3 2201.22   748.5 2221.56   794.2 2226.56
#Mann= 6 ,-1 , 0
       0      .1       0     210    .035       0     290      .1       0
     425    .045       0   487.1     .12       0  605.61      .1       0
Bank Sta=425,487.1
XS Rating Curve= 0 ,0
Exp/Cntr=0.3,0.1

Type RM Length L Ch R = 1 ,46591   ,446.8,471.6,508.2
XS GIS Cut Line= 3
     2130167.944      222954.656     2130677.493      222945.976
     2130768.638      222533.649
#Sta/Elev= 30
       0 2236.64    91.5 2237.32   143.7 2238.75   209.1 2238.03   254.8 2233.07
     330 2234.09   336.5 2232.64   346.3  2227.2   349.6 2226.35   382.2 2226.75
   405.1 2224.97   431.2 2227.23   457.4 2232.85   463.9 2233.44     526 2234.89
   545.6 2234.14   578.4 2222.79   624.2 2204.49   630.7  2200.4   647.1 2184.36
   650.4 2182.29   696.2 2182.06   712.6 2181.28     729 2182.36   748.6 2185.92
   784.6 2187.38   840.2 2194.43   853.3 2198.12   902.4 2218.68   931.9 2227.66
#Mann= 7 ,-1 , 0
       0      .1       0     330     .06       0  519.62      .1       0
  589.62    .035       0  619.62      .1       0   696.2    .045       0
     729      .1       0
Bank Sta=696.2,729
XS Rating Curve= 0 ,0
Exp/Cntr=0.3,0.1

Type RM Length L Ch R = 1 ,46120   ,296.1,316.8,341.1
XS GIS Cut Line= 3
     2130180.965      222972.886     2130816.381       223015.42
     2131327.017      222687.186
#Sta/Elev= 30
       0 2231.72     160  2229.1   182.9 2227.32     209 2223.24   290.7 2216.32
     320 2218.77   385.4 2221.46   476.8 2230.41   512.7  2230.1   571.5 2221.24
   653.2  2199.6   666.2 2193.27   679.3 2184.73   692.3 2181.88   845.7 2184.98
   878.4  2183.5   914.2 2184.09   950.1 2181.13     973 2183.04  1021.9 2180.79
  1041.5 2181.98  1067.6 2178.88  1087.2  2179.1    1097    2183  1116.6 2204.77
  1119.8 2206.79  1132.9 2208.25  1142.7 2213.76  1172.1 2225.06  1243.9  2261.1
#Mann= 7 ,-1 , 0
       0      .1       0     320     .06       0     520      .1       0
     620    .035       0  726.84      .1       0  1041.5    .045       0
    1097      .1       0
Bank Sta=1041.5,1097
XS Rating Curve= 0 ,0
Exp/Cntr=0.3,0.1

Type RM Length L Ch R = 1 ,45803   ,406.5,443.1,495.4
XS GIS Cut Line= 2
     2130201.798      222993.719      2131415.34      223097.886
#Sta/Elev= 30
       0 2226.33   124.4 2223.15   144.1 2221.52   183.4 2213.83   229.2 2209.84
   265.2 2212.54   343.8 2211.67   448.6 2220.95   484.6 2220.99   510.8  2219.4
   543.5 2214.65   592.6 2204.34     609 2199.54   635.2 2198.13   638.5 2197.13
   658.1 2184.52   667.9 2182.45   694.1 2181.04   713.8 2182.86     740 2180.97
   877.5 2183.36   926.6 2181.76     943 2178.23   952.8  2177.7   988.8 2177.96
  1011.7 2181.65  1044.5 2184.88    1087 2200.31  1159.1 2231.42    1218  2263.1
#Mann= 8 ,-1 , 0
       0      .1       0     300     .06       0     500     .04       0
     600      .1       0     700    .035       0     890      .1       0
   926.6    .045       0  1011.7      .1       0
Bank Sta=926.6,1011.7
XS Rating Curve= 0 ,0
Exp/Cntr=0.3,0.1

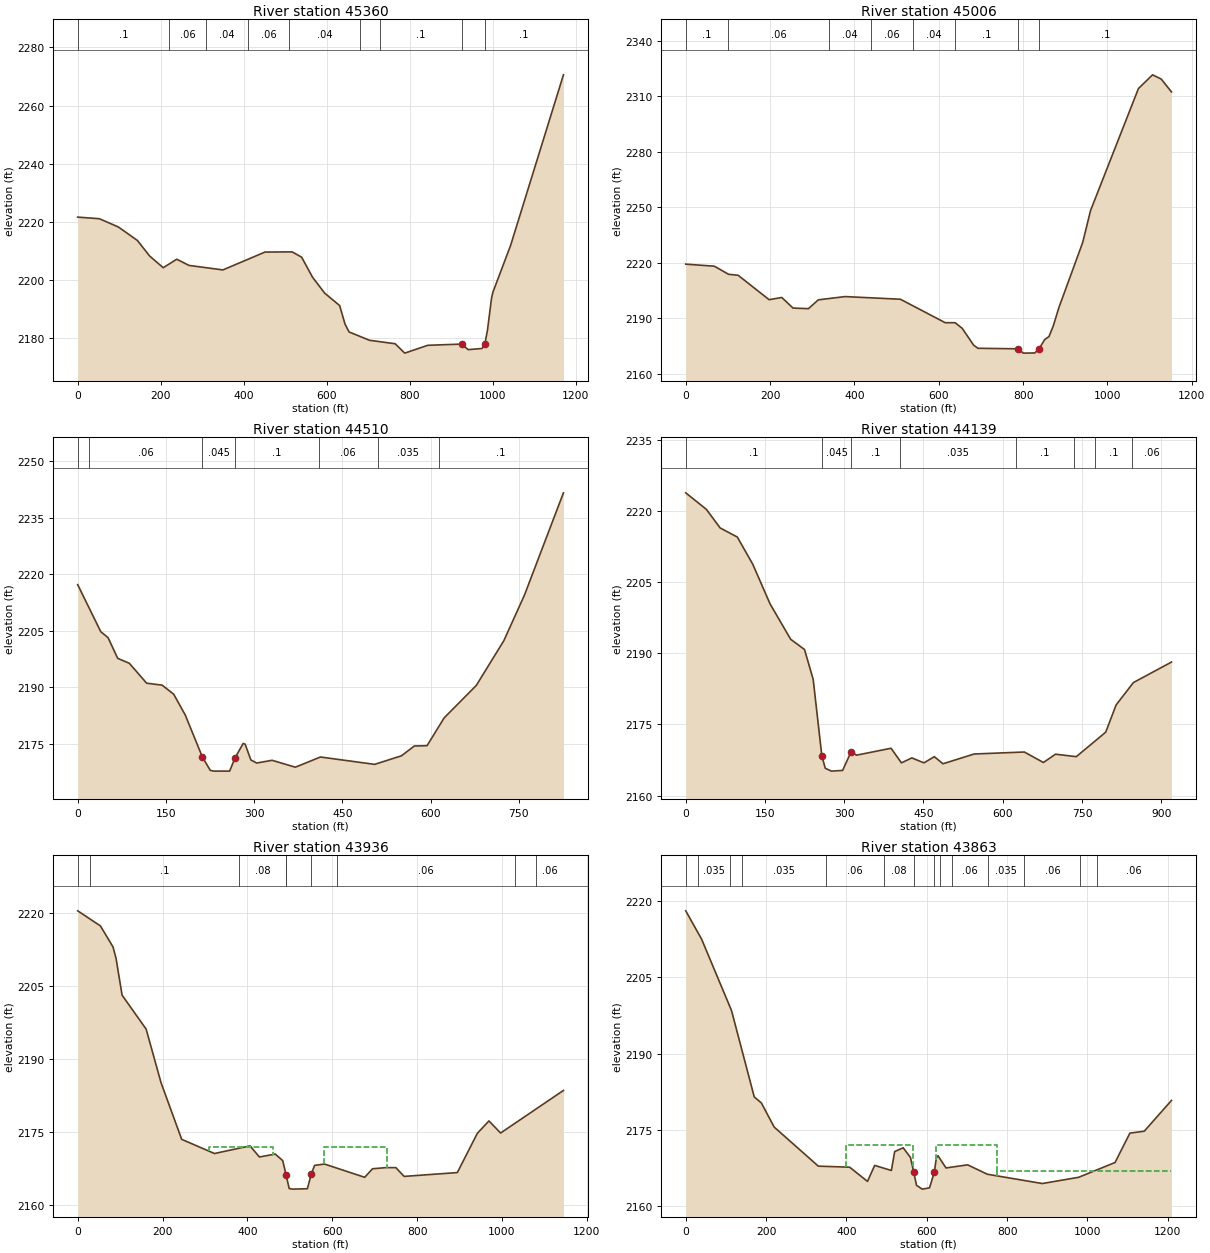
Type RM Length L Ch R = 1 ,45360   ,325.9,353.7,380.4
XS GIS Cut Line= 3
     2130188.777      223011.948     2130725.236      223071.844
     2131024.715      223627.399
#Sta/Elev= 30
       0 2221.66    52.3  2221.1    98.1 2218.26   143.9 2213.63   173.4 2208.28
   206.1 2204.26   238.8 2207.18   268.3 2205.05     350  2203.5   451.5 2209.64
   516.9  2209.7   539.8 2207.88     566 2201.01   595.4 2195.51   631.4 2191.25
   644.4 2184.87   654.2 2182.17   703.3 2179.31   765.4 2178.11   788.3 2174.89
   843.9 2177.58   925.7    2178   941.3 2176.09   974.7 2176.49   981.3 2177.87
   987.8 2182.84   997.6 2193.82  1000.9 2195.85  1043.4 2211.87  1170.9 2270.58
#Mann= 9 ,-1 , 0
       0      .1       0     220     .06       0     310     .04       0
     410     .06       0     510     .04       0  679.79     .06       0
  729.79      .1       0   925.7    .045       0   981.3      .1       0
Bank Sta=925.7,981.3
XS Rating Curve= 0 ,0
Exp/Cntr=0.3,0.1

Type RM Length L Ch R = 1 ,45006   ,506.3,496.4,488
XS GIS Cut Line= 4
     2130162.736      223019.7612130664.08745597223108.436583994
2130576.23300171223478.6795549122130608.77779998223738.998071994
#Sta/Elev= 30
       0  2219.3    67.9 2218.18   101.6 2213.82   124.3 2213.28   197.8  2200.1
   227.8  2201.3   254.5 2195.57   291.1 2195.27   314.4 2200.02   377.7 2201.78
   509.1 2200.35   615.3 2187.69   638.9 2187.67   655.8 2184.62   682.7 2175.58
   692.9 2173.87   786.9 2173.58   800.8 2171.25   827.8 2171.34   837.9 2173.54
   851.3 2178.58   861.5  2180.2   871.6 2185.91     885 2195.84   941.4 2230.97
   960.1 2248.26  1073.6  2314.1  1107.1 2321.52  1127.7 2319.23    1152 2312.29
#Mann= 8 ,-1 , 0
       0      .1       0     100     .06       0     340     .04       0
     440     .06       0  539.13     .04       0  639.13      .1       0
   786.9    .045       0   837.9      .1       0
Bank Sta=786.9,837.9
XS Rating Curve= 0 ,0
Exp/Cntr=0.3,0.1

Type RM Length L Ch R = 1 ,44510   ,387.6,371.3,354.7
XS GIS Cut Line= 3
     2130126.277      223022.365     2130139.298      223616.115
     2130334.611      223741.115
#Sta/Elev= 30
       0 2217.24    39.2 2204.74    51.6 2203.17      68 2197.65    87.7 2196.36
   117.2 2191.06   143.5 2190.54   163.2 2188.13   182.9 2182.59   212.12171.385
   225.5 2167.88   232.1 2167.69   258.3  2167.7   267.6 2171.24   281.3 2175.04
   284.6 2174.87   294.4 2170.66   304.3 2169.84   330.5 2170.57     370 2168.73
   412.6 2171.44   504.8 2169.49   550.4 2171.76   572.3 2174.37   593.9 2174.45
     623 2181.84   677.6 2190.45   724.5 2202.36   759.5 2214.46   825.8 2241.64
#Mann= 7 ,-1 , 0
       0      .1       0      20     .06       0   212.1    .045       0
   267.6      .1       0     410     .06       0     510    .035       0
  613.89      .1       0
Bank Sta=212.1,267.6
XS Rating Curve= 0 ,0
Exp/Cntr=0.3,0.1

Type RM Length L Ch R = 1 ,44139   ,205.7,202.3,197.4
XS GIS Cut Line= 3
     2129760.826      223052.747     2129750.409      223257.608
     2130069.854      223896.497
#Sta/Elev= 30
       0 2223.81    39.1 2220.32    65.1 2216.41    97.7 2214.48     127 2208.73
   159.5 2200.42   198.6 2192.94   224.8 2190.78   241.2 2184.51   257.6 2168.37
   264.1 2165.74   275.9 2165.14   296.9 2165.29   313.2 2169.27   323.1  2168.5
   388.6 2169.96   408.3 2166.88   427.9 2167.93   450.9 2166.88   470.5 2168.19
   486.9 2166.69   545.9 2168.75   640.9 2169.17     677 2166.96   699.9 2168.71
   739.2 2168.19   794.9 2173.35   814.6 2179.09   847.3 2183.81   919.4 2188.13
#Mann= 8 ,-1 , 0
       0      .1       0   257.6    .045       0   313.2      .1       0
  405.13    .035       0  625.13      .1       0  735.13     .04       0
  775.13      .1       0  845.13     .06       0
Bank Sta=257.6,313.2
XS Rating Curve= 0 ,0
Exp/Cntr=0.5,0.3

Type RM Length L Ch R = 1 ,43936   ,74.4,73.4,73
XS GIS Cut Line= 3
2129694.61301816 223017.501639192129518.82236989223285.797803702
     2129970.027       223975.49
#Sta/Elev= 30
       0 2220.49    53.5  2217.4    83.2 2213.08    90.4 2210.73   104.6 2203.18
   161.3 2196.21   196.4 2185.22   245.1 2173.58   322.4 2170.67   406.2 2172.24
   428.3 2169.96   465.7 2170.55   483.2 2169.22     491 2166.36   498.4  2163.5
   505.8 2163.36   541.3 2163.44   550.8 2166.52   558.3 2168.23   581.6 2168.51
   676.4 2165.79   694.9 2167.54   726.2 2167.77   749.9 2167.77   769.4 2165.97
   894.8 2166.76   941.9 2174.81   969.3 2177.36   996.8 2174.88  1144.9 2183.62
#Mann= 9 ,-1 , 0
       0     .06       0      30      .1       0  380.76     .08       0
  490.76     .06       0     491    .045       0   550.8     .08       0
  610.76     .06       0 1030.76     .04       0 1080.76     .06       0
#XS Ineff= 4 ,-1
       0     310    2167     310     460    2172     580     730    2172
     730  1144.9    2167
Permanent Ineff=
       F       F       F       F
Bank Sta=491,550.8
XS Rating Curve= 0 ,0
Exp/Cntr=0.5,0.3

Type RM Length L Ch R = 1 ,43863   ,274.1,263.1,247.4
XS GIS Cut Line= 3
2129090.64995005223194.651246594     2129472.631       223350.49
     2129912.736      224014.552
#Sta/Elev= 30
       0 2218.12    39.5 2212.55   113.9 2198.51   170.6 2181.49   188.3 2180.31
   220.2 2175.56   330.1 2167.87     408 2167.67   452.5 2164.87   470.3 2168.02
   511.9 2167.02   520.1 2170.74   541.3 2171.49   559.4 2169.59   567.4 2166.78
   574.5  2164.1   588.7 2163.35   606.9  2163.6   618.8  2166.7   623.9  2169.5
   627.9 2169.93   647.9 2167.52   701.9 2168.13   750.8 2166.28   887.7 2164.45
   978.2 2165.68  1068.7 2168.59  1105.7 2174.37  1141.4 2174.75  1209.2 2180.81
#Mann= 14 ,-1 , 0
       0      .1       0      30    .035       0     110      .1       0
     140    .035       0     350     .06       0  492.55     .08       0
   567.4    .045       0   618.8     .08       0  632.55      .1       0
  662.55     .06       0  752.55    .035       0  842.55     .06       0
  982.55    .035       0 1022.55     .06       0
#XS Ineff= 4 ,-1
       0     400    2167     400   566.7    2172   623.3     775    2172
     775  1209.2    2167
Permanent Ineff=
       F       F       F       F
Bank Sta=567.4,618.8
XS Rating Curve= 0 ,0
Exp/Cntr=0.5,0.3

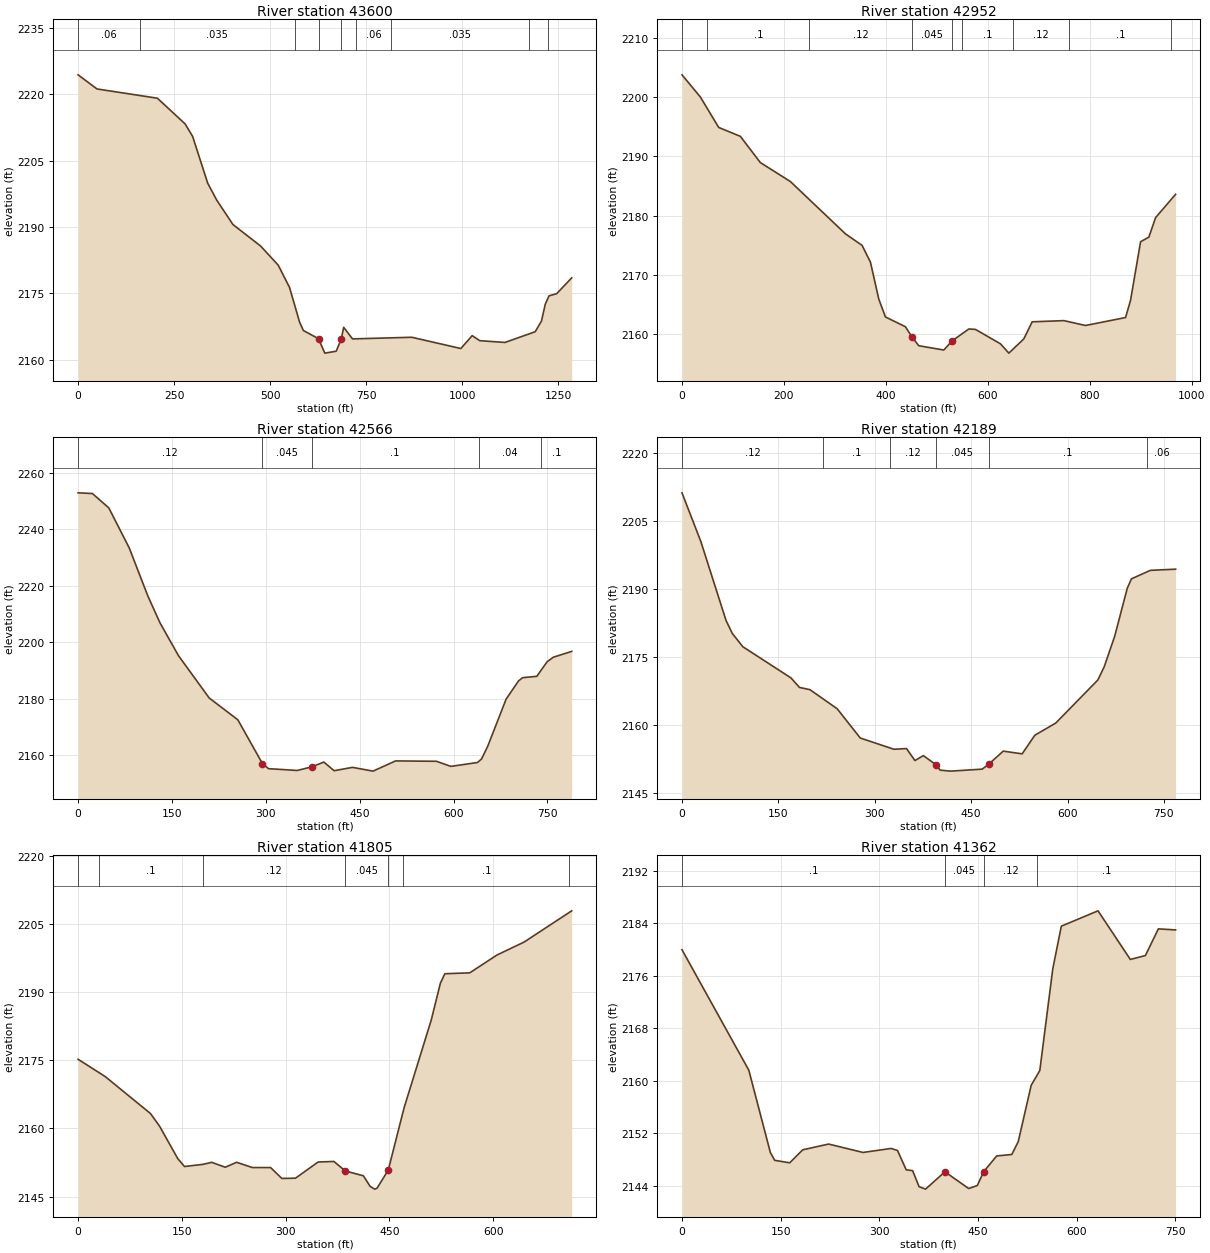
Type RM Length L Ch R = 1 ,43600   ,670.3,647.5,604.9
XS GIS Cut Line= 3
     2128764.298      223563.163      2129267.77      223597.886
     2129899.715      224056.219
#Sta/Elev= 30
       0 2224.34    49.2 2221.15   206.5 2219.06   278.6 2213.27   298.2 2210.45
   337.5 2199.88   360.5 2196.13   403.1 2190.56   475.2  2185.7   521.1 2181.38
   550.6 2176.34   576.8 2168.51   586.7 2166.62     626 2164.78   642.4 2161.52
     672 2161.95   685.1 2164.65   691.6 2167.35   714.6 2164.73   868.8  2165.1
   996.7 2162.56  1026.2 2165.47  1045.9 2164.33  1111.5 2163.93  1190.2 2166.35
  1206.6 2168.75  1216.4 2172.54  1226.3 2174.46    1246 2174.92  1285.3 2178.51
#Mann= 9 ,-1 , 0
       0     .06       0     160    .035       0  564.67     .06       0
     626    .045       0   685.1      .1       0  724.67     .06       0
  814.67    .035       0 1174.67     .06       0 1224.67     .04       0
Bank Sta=626,685.1
XS Rating Curve= 0 ,0
Exp/Cntr=0.3,0.1

Type RM Length L Ch R = 1 ,42952   ,383.1,386.1,387.4
XS GIS Cut Line= 2
     2128979.576      224396.497     2129920.548       224167.33
#Sta/Elev= 30
       0 2203.73      36    2200      72 2194.86   114.5 2193.36   153.8 2188.93
   212.7 2185.74   320.6 2176.93   353.4 2174.97   369.7 2172.17   386.1 2165.93
   399.2 2162.91   438.4 2161.26   451.5  2159.5   464.6 2158.06   513.7 2157.33
     530 2158.87   562.8 2160.88   575.8 2160.81   624.9 2158.38   641.3 2156.81
   670.7 2159.21   687.1 2162.09   749.3 2162.29   791.8 2161.47   870.3 2162.81
   880.1  2165.7   899.8 2175.59   916.1 2176.37   929.2 2179.65   968.5 2183.59
#Mann= 9 ,-1 , 0
       0     .12       0      50      .1       0     250     .12       0
   451.5    .045       0     530     .12       0     550      .1       0
     650     .12       0     760      .1       0     960     .06       0
Bank Sta=451.5,530
XS Rating Curve= 0 ,0
Exp/Cntr=0.3,0.1

Type RM Length L Ch R = 1 ,42566   ,371.6,377,402.8
XS GIS Cut Line= 2
     2129177.493      224712.469      2129955.27      224580.524
#Sta/Elev= 30
       0 2252.99    22.9 2252.74    49.1 2247.64    81.8 2233.42   111.3  2216.5
   130.9 2206.88   160.4 2195.26   209.5 2180.24   255.3  2172.5   294.6 2156.97
   304.4 2155.16   350.2 2154.52   373.2 2155.79   392.8  2157.5   409.2 2154.44
   438.6 2155.62   471.4 2154.29   507.4 2157.91   572.8 2157.78   595.8 2155.97
   638.3 2157.35   644.9 2158.62   654.7 2163.11   684.1 2179.83   703.8 2186.24
   710.3 2187.42   733.2 2187.92   749.6 2193.08   759.4 2194.67   788.9 2196.76
#Mann= 5 ,-1 , 0
       0     .12       0   294.6    .045       0   373.2      .1       0
     640     .04       0     740      .1       0
Bank Sta=294.6,373.2
XS Rating Curve= 0 ,0
Exp/Cntr=0.3,0.1

Type RM Length L Ch R = 1 ,42189   ,354.2,384.2,404.6
XS GIS Cut Line= 3
     2129226.865      224864.595     2129476.104      225000.663
      2129955.27      225070.108
#Sta/Elev= 30
       0 2211.22    29.4 2200.46    68.5  2183.1    78.3 2180.22    94.6  2177.3
   169.7 2170.41   182.8 2168.32   199.1 2167.83   241.5 2163.62   277.4 2157.17
   329.8 2154.69   349.4 2154.84   362.5  2152.2   375.6 2153.29   395.2 2151.29
   401.7 2150.08   418.1 2149.87   467.2 2150.31     477 2151.36   499.9 2154.28
   529.3 2153.68     549 2157.77   581.7 2160.48   647.1 2169.96   656.9 2172.83
   673.3 2179.59   692.9 2190.18   699.4 2192.26   728.9 2194.13   768.1 2194.39
#Mann= 6 ,-1 , 0
       0     .12       0     220      .1       0  323.96     .12       0
   395.2    .045       0     477      .1       0  723.96     .06       0
Bank Sta=395.2,477
XS Rating Curve= 0 ,0
Exp/Cntr=0.3,0.1

Type RM Length L Ch R = 1 ,41805   ,416.2,442.9,452.8
XS GIS Cut Line= 2
     2129179.884      225088.699     2129715.687      225559.691
#Sta/Elev= 30
       0 2175.24    39.3 2171.42   104.7 2163.28   117.8  2160.5     144 2153.38
   153.8 2151.63     180 2152.09   193.1 2152.55   212.7 2151.47   229.1 2152.56
     252  2151.4   278.2  2151.4   294.5    2149   314.2 2149.06   346.9 2152.62
   369.8 2152.74   386.1 2150.65   412.3 2149.59   422.1 2147.25   428.7 2146.65
     432 2146.84   448.3 2150.85   471.2 2164.58   510.5 2183.93   523.6 2191.98
   530.1 2194.07   566.1 2194.27   605.4 2198.19   644.7 2201.05   713.4 2207.92
#Mann= 7 ,-1 , 0
       0     .12       0      30      .1       0     180     .12       0
   386.1    .045       0   448.3     .12       0     470      .1       0
     710     .04       0
Bank Sta=386.1,448.3
XS Rating Curve= 0 ,0
Exp/Cntr=0.3,0.1

Type RM Length L Ch R = 1 ,41362   ,478.6,467.5,450
XS GIS Cut Line= 2
     2128962.215      225208.997     2129268.873       225893.77
#Sta/Elev= 30
       0    2180   101.6 2161.63   134.3  2149.1   140.9  2147.9   163.8 2147.52
   183.5  2149.5   222.8 2150.38   275.2  2149.1   317.8 2149.71   327.6  2149.4
   340.8 2146.46   350.6 2146.32   360.4 2143.88   370.2 2143.51   399.7 2146.15
   435.8  2143.6   448.9 2144.06   458.7 2146.19   478.4 2148.57   501.3 2148.79
   511.1 2150.74   530.8 2159.34   543.9 2161.59   563.6 2177.07   576.6 2183.59
   632.4 2185.93   681.5 2178.52   704.4 2179.11   724.1 2183.18   750.3 2183.02
#Mann= 4 ,-1 , 0
       0      .1       0   399.7    .045       0   458.7     .12       0
     540      .1       0
Bank Sta=399.7,458.7
XS Rating Curve= 0 ,0
Exp/Cntr=0.3,0.1