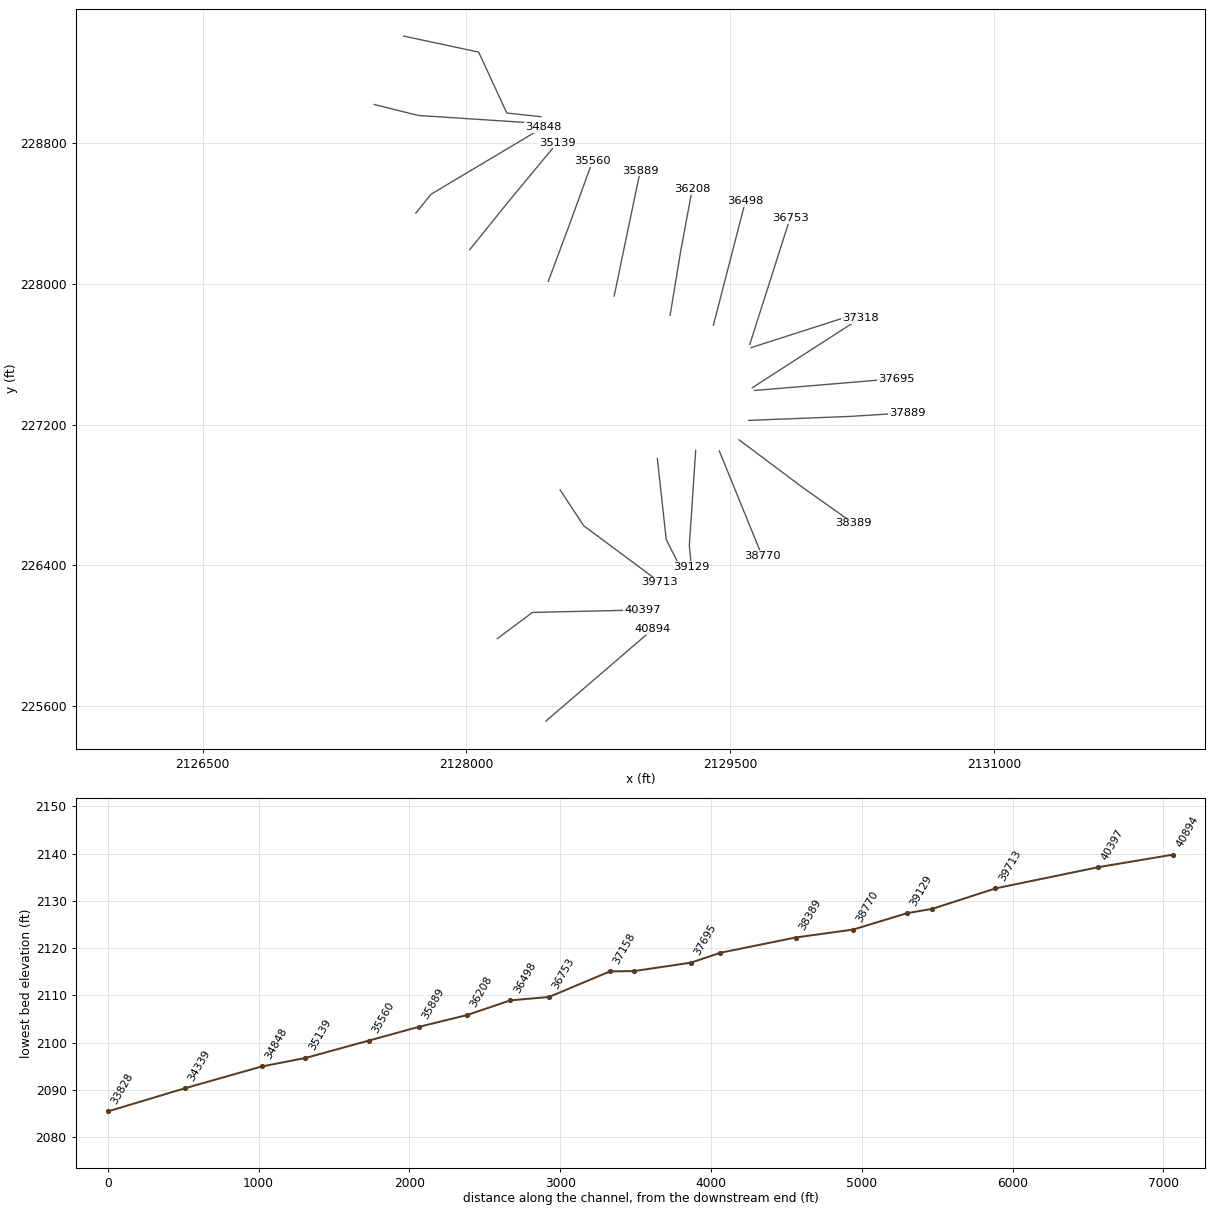
HEC-RAS study SECONDCK.prj: SECONDCK

--- SECONDCK.g01 (geometry) --- (continued)

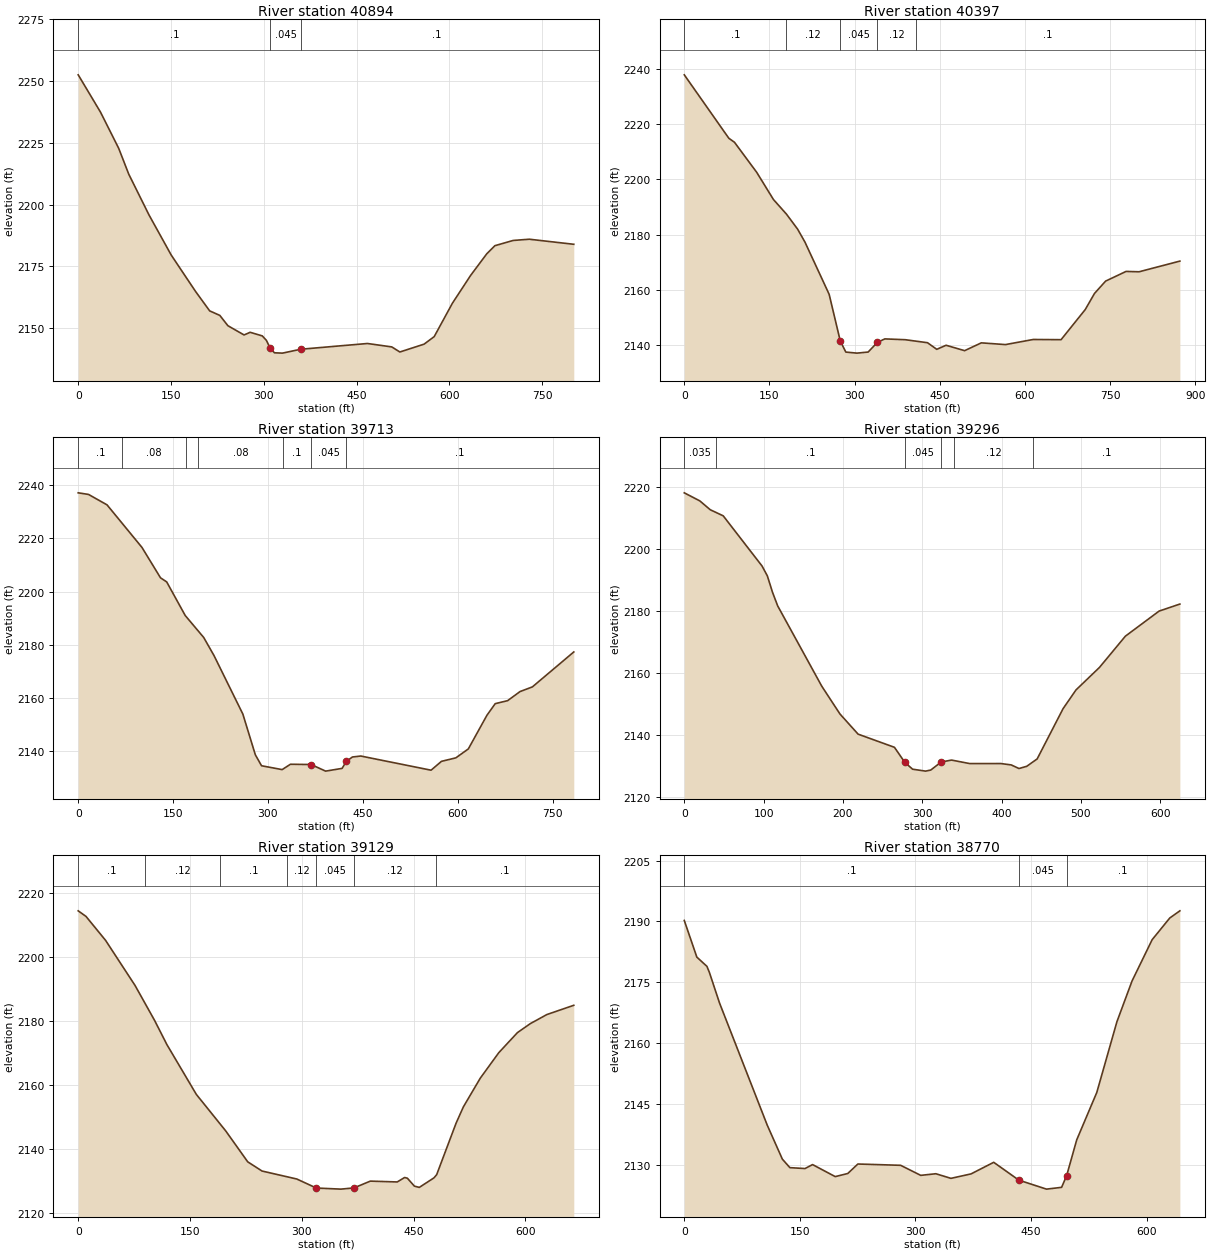
Type RM Length L Ch R = 1 ,40894   ,520.5,497.7,463.7
XS GIS Cut Line= 2
     2128451.798      225514.552     2129059.353      226036.603
#Sta/Elev= 30
       0 2252.54      36 2237.45    65.4  2222.8    81.7  2212.3   114.4 2195.79
   150.4  2179.5   189.6  2164.8   212.5  2156.9   228.9 2155.07     242 2150.88
   268.1 2147.14   277.9 2148.22   297.5 2146.76   304.1 2144.98   310.6 2141.67
   317.2 2139.91   330.2 2139.78   359.6 2141.35   467.5 2143.68   506.8  2142.3
   519.9 2140.24   559.1 2143.42   575.4 2146.47   604.9 2160.03   634.3 2171.28
   660.4 2180.04   673.5 2183.31     703 2185.43   729.1 2185.93     801 2183.88
#Mann= 3 ,-1 , 0
       0      .1       0   310.6    .045       0   359.6      .1       0
Bank Sta=310.6,359.6
XS Rating Curve= 0 ,0
Exp/Cntr=0.3,0.1

Type RM Length L Ch R = 1 ,40397   ,697.9,684,638.2
XS GIS Cut Line= 3
     2128175.975      225984.061     2128375.409      226132.608
     2128999.648      226146.771
#Sta/Elev= 30
       0 2237.88    78.5 2214.91    88.4 2213.47   127.6 2202.58   157.1 2192.73
     180 2187.45   199.6 2182.03   212.7 2177.28   255.2 2158.43   274.8 2141.52
   284.6  2137.5   304.2 2137.12   323.9 2137.51   340.2 2141.01   353.3 2142.27
   389.2 2141.98   428.5 2140.89   444.8  2138.5   461.2 2139.97   493.9 2138.01
   523.3 2140.84   565.8 2140.21   614.8 2142.06   663.8 2141.99   706.4  2152.9
   722.7 2158.73   742.3  2163.2   778.3  2166.7   801.2 2166.57   873.1 2170.44
#Mann= 5 ,-1 , 0
       0      .1       0     180     .12       0   274.8    .045       0
   340.2     .12       0  408.68      .1       0
Bank Sta=274.8,340.2
XS Rating Curve= 0 ,0
Exp/Cntr=0.3,0.1

Type RM Length L Ch R = 1 ,39713   ,442.9,416.6,385
XS GIS Cut Line= 3
     2128532.808      226829.388     2128667.076      226625.663
       2129100.1      226304.052
#Sta/Elev= 30
       0 2237.12    16.3 2236.52    45.6  2232.6   100.8 2216.62   130.1 2205.21
   139.9 2203.67   169.2 2191.04   198.4  2182.8   214.7    2176   260.3 2154.03
     280 2138.76   289.8 2134.63   322.4 2133.18   335.5 2135.19   368.2 2135.09
   391.1 2132.61   417.2 2133.64   423.8 2136.28   433.6 2137.92   446.7 2138.28
   557.8 2132.96   574.2 2136.28     597  2137.6   616.7 2140.95   646.1 2153.58
   659.2 2157.95   678.8 2159.07   698.4 2162.48     718 2164.25   783.4 2177.36
#Mann= 7 ,-1 , 0
       0      .1       0      70     .08       0     170     .05       0
     190     .08       0  323.99      .1       0   368.2    .045       0
   423.8      .1       0
Bank Sta=368.2,423.8
XS Rating Curve= 0 ,0
Exp/Cntr=0.3,0.1

Type RM Length L Ch R = 1 ,39296   ,170.5,167.7,157.2
XS GIS Cut Line= 3
2129085.87294527227007.6442739782129136.41766916226546.540401275
     2129222.631226377.481616451
#Sta/Elev= 30
       0 2218.25    19.6 2215.64    32.7 2212.79    49.1 2210.81    98.1 2194.57
   104.7 2191.41   111.2 2186.12   117.7 2181.73   173.3 2155.76   196.2 2146.79
   219.1 2140.26   264.9 2136.01     278 2131.14   287.8 2128.93   304.2 2128.31
   310.7 2128.66   323.8 2131.25   336.9 2131.88   359.8 2130.75     399 2130.76
   412.1 2130.32   421.9 2129.15   431.7 2129.87   444.8 2132.25   477.5 2148.51
   493.8 2154.56   523.3 2161.81     556 2171.92   598.5 2180.03   624.7  2182.3
#Mann= 6 ,-1 , 0
       0    .035       0      40      .1       0     278    .045       0
   323.8      .1       0     340     .12       0     440      .1       0
Bank Sta=278,323.8
XS Rating Curve= 0 ,0
Exp/Cntr=0.3,0.1

Type RM Length L Ch R = 1 ,39129   ,330.6,358,370.8
XS GIS Cut Line= 3
2129303.93002518227054.2582638682129267.66446357226512.001771166
2129279.75298411226391.116565787
#Sta/Elev= 30
       0  2214.3    10.5 2212.55    36.8 2205.06    76.3 2190.99   102.6 2180.04
     119 2172.54   158.5 2156.98     198 2145.56   227.5 2135.91   246.7 2133.04
   293.3 2130.55   319.6 2127.73   352.5 2127.39     370 2127.77     392 2129.89
   428.1 2129.63     438 2131.02   441.7  2130.8   451.1 2128.33   457.7 2127.93
   477.4 2130.91     481  2131.9     507 2147.95   516.9  2153.1   539.5 2162.03
   564.4 2170.01   589.4 2176.27   606.8 2179.09   628.9 2181.91     665  2184.8
#Mann= 7 ,-1 , 0
       0      .1       0      90     .12       0     190      .1       0
     280     .12       0   319.6    .045       0     370     .12       0
     480      .1       0
Bank Sta=319.6,370
XS Rating Curve= 0 ,0
Exp/Cntr(USF)=0,0
Exp/Cntr=0.3,0.1

Type RM Length L Ch R = 1 ,38770   ,356.2,381.8,400.8
XS GIS Cut Line= 2
     2129438.097      227051.071     2129680.965      226455.524
#Sta/Elev= 30
       0 2190.25    16.3  2181.2    29.4 2178.92    32.6 2177.42    45.7  2169.9
   107.7  2139.7   127.3 2131.32   137.1 2129.22   156.7    2129   166.5 2129.98
   195.9 2127.01   212.2 2127.78   225.3 2130.12   280.8  2129.8   306.9 2127.32
   326.5 2127.72   346.1 2126.58   372.2 2127.68   401.6 2130.54   434.2 2126.14
   470.1 2123.92   489.7 2124.36   496.2 2127.22   509.3 2136.07   535.4  2147.8
   561.5 2165.26   581.1  2175.3   607.2  2185.5   630.1 2190.86   643.2 2192.63
#Mann= 3 ,-1 , 0
       0      .1       0   434.2    .045       0   496.2      .1       0
Bank Sta=434.2,496.2
XS Rating Curve= 0 ,0
Exp/Cntr=0.3,0.1

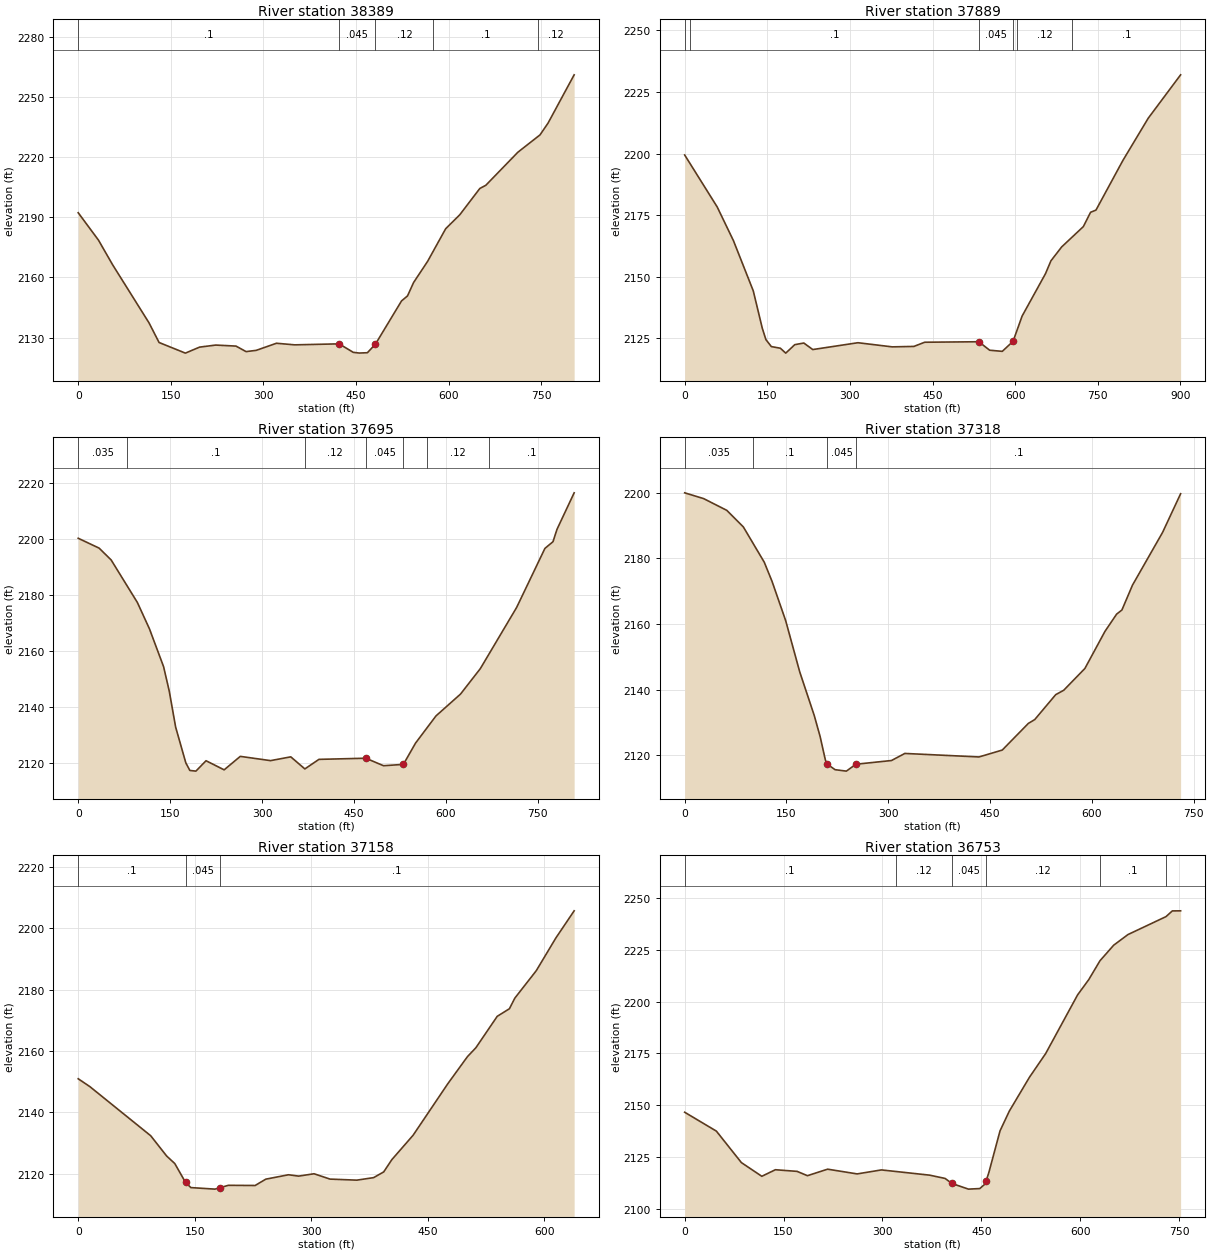
Type RM Length L Ch R = 1 ,38389   ,465.2,500,521.5
XS GIS Cut Line= 3
     2129550.755      227114.142     2129915.329      226841.216
     2130199.195      226640.136
#Sta/Elev= 30
       0 2192.32    32.8 2178.66    55.7 2166.37   114.7 2137.35     131 2127.54
   173.6 2122.24   196.6 2125.24   222.8 2126.26   255.6 2125.75   271.9    2123
   288.3 2123.62   321.1 2127.17   350.6 2126.37   422.6 2126.87   445.6 2122.62
   455.4 2122.28   468.4 2122.44   481.4  2126.7   523.7  2148.3   533.4  2150.8
   543.2 2157.47     566 2168.08   595.2 2184.34     618 2191.29   650.5 2204.43
   660.2 2206.02   712.2 2222.55     748 2231.18     761 2237.06   803.3 2261.17
#Mann= 5 ,-1 , 0
       0      .1       0   422.6    .045       0   481.4     .12       0
  575.41      .1       0  745.41     .12       0
Bank Sta=422.6,481.4
XS Rating Curve= 0 ,0
Exp/Cntr=0.3,0.1

Type RM Length L Ch R = 1 ,37889   ,192.3,194.1,194.4
XS GIS Cut Line= 3
     2129605.771      227224.841     2130178.777      227247.251
     2130505.179      227267.652
#Sta/Elev= 30
       0 2199.42      59 2178.35    88.5 2164.67   124.5  2144.3   140.9 2129.13
   147.5 2124.49   157.3 2121.66   173.7 2120.99   183.5    2119   199.9 2122.43
   216.3  2123.1   232.6 2120.45   314.6 2123.22   376.8 2121.54   416.2 2121.72
   435.8 2123.42   534.1 2123.62   553.8 2120.18   576.7 2119.72   596.3  2123.8
   612.7 2134.04   655.2 2151.27     665 2156.46   684.6 2162.12   723.9 2170.36
     737 2176.16   746.8 2177.05   795.8 2197.25   841.6 2214.31   900.5 2231.95
#Mann= 6 ,-1 , 0
       0     .05       0      10      .1       0   534.1    .045       0
   596.3      .1       0  603.44     .12       0  703.44      .1       0
Bank Sta=534.1,596.3
XS Rating Curve= 0 ,0
Exp/Cntr=0.3,0.1

Type RM Length L Ch R = 1 ,37695   ,337.6,376.3,392.6
XS GIS Cut Line= 2
 2129637.8913601 227394.796848162130444.48614654227462.325714002
#Sta/Elev= 30
       0  2200.1    34.1 2196.58    53.8 2192.34    96.6 2177.15   116.4 2167.68
   139.4 2154.19   148.6 2145.48     159 2132.67   175.6 2119.89   182.2 2117.16
   192.1 2116.92   208.6 2120.63   238.2 2117.38   264.5 2122.19   313.9 2120.67
   346.9 2122.02   369.9 2117.71   392.9 2121.12   469.42121.528   498.3 2118.85
   530.72119.328   550.6 2126.95   583.9 2136.64   623.9 2144.43   656.3 2153.54
   715.6 2175.41   761.7 2196.48   774.9 2198.88   781.4 2203.29   809.4 2216.33
#Mann= 7 ,-1 , 0
       0    .035       0      80      .1       0     370     .12       0
   469.4    .045       0   530.7      .1       0     570     .12       0
     670      .1       0
Bank Sta=469.4,530.7
XS Rating Curve= 0 ,0
Exp/Cntr(USF)=0,0
Exp/Cntr=0.3,0.1

Type RM Length L Ch R = 1 ,37318   ,169.6,160.7,153.7
XS GIS Cut Line= 2
     2129625.409      227410.386     2130239.993      227806.219
#Sta/Elev= 30
       0 2199.97    27.9 2198.21    62.1 2194.63    86.5 2189.57   117.3 2178.82
   128.8 2172.97   148.9 2160.99   169.5 2145.45   190.9 2132.15   199.6 2125.72
   207.4 2118.53   209.8 2117.32   221.7 2115.58   238.3 2115.14   252.42117.242
   304.8 2118.37   324.5 2120.53   433.8 2119.46   468.1 2121.56   506.6 2129.69
     516 2130.86   546.9 2138.45   558.7 2139.79   589.9 2146.43   619.5 2157.74
   636.7    2163   644.5 2164.26   660.1 2171.85   704.4  2187.9     731 2199.69
#Mann= 4 ,-1 , 0
       0    .035       0     100      .1       0   209.8    .045       0
   252.4      .1       0
Bank Sta=209.8,252.4
XS Rating Curve= 0 ,0
Exp/Cntr=0.3,0.1

Type RM Length L Ch R = 1 ,37158   ,364.8,404,432
XS GIS Cut Line= 2
2129619.13334181227638.6510859222130226.89313438227833.734476131
#Sta/Elev= 30
       0 2150.97      15 2148.42    93.3 2132.44   113.9 2125.82   124.3 2123.39
   138.1 2117.27     145 2115.57     176 2115.07   182.62115.537   193.2 2116.31
   227.7 2116.25   241.4 2118.31   270.6 2119.74   283.7  2119.3   303.5 2120.07
   324.1 2118.33   358.6 2117.99   380.2 2118.81   393.2 2120.67   403.6 2124.64
     431 2132.59   475.7 2149.36     501 2158.18   511.8 2161.06   539.3 2171.29
     555 2173.76   561.9 2177.19   589.5 2186.12   614.9 2196.83   638.3 2205.61
#Mann= 3 ,-1 , 0
       0      .1       0   138.1    .045       0   182.6      .1       0
Bank Sta=138.1,182.6
XS Rating Curve= 0 ,0
Exp/Cntr(USF)=0,0
Exp/Cntr=0.3,0.1

Type RM Length L Ch R = 1 ,36753   ,252.7,255.7,256.8
XS GIS Cut Line= 2
2129611.63013449227657.4091042112129840.47795762228373.965402863
#Sta/Elev= 30
       0 2146.69    48.1 2137.59      86 2122.44     117 2115.84   137.6    2119
   170.5 2118.21   186.2 2116.13   216.8 2119.27   261.6 2116.99   298.4 2118.91
   371.5 2116.39     395 2114.81   405.2  2112.4   430.4 2109.66   447.6 2109.93
   454.5 2111.82   457.32113.637   461.4 2117.72   478.3 2137.71   492.4 2147.24
   522.9 2163.52   547.5 2174.94     596 2203.23   612.9 2210.57   629.9 2219.65
   650.7 2227.14   672.4 2232.27     730 2240.89   739.6 2243.65   752.2 2243.69
#Mann= 6 ,-1 , 0
       0      .1       0     320     .12       0   405.2    .045       0
   457.3     .12       0     630      .1       0     730     .05       0
Bank Sta=405.2,457.3
XS Rating Curve= 0 ,0
Exp/Cntr(USF)=0,0
Exp/Cntr=0.3,0.1

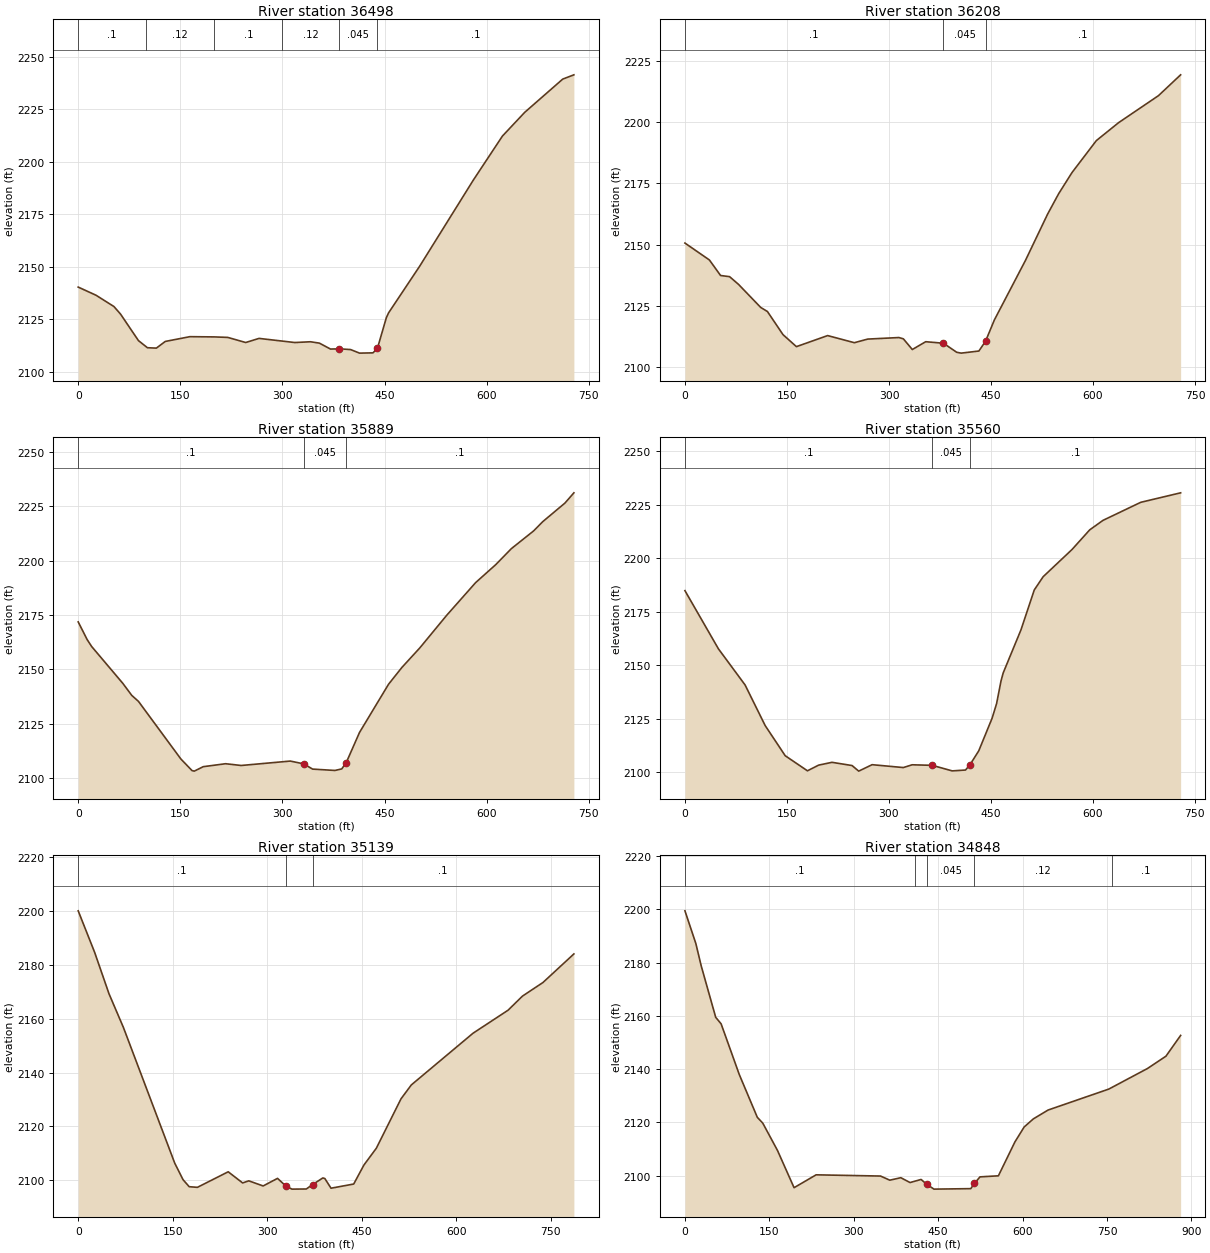
Type RM Length L Ch R = 1 ,36498   ,285.9,289.5,291.5
XS GIS Cut Line= 2
     2129404.468      227765.902      2129586.72      228470.748
#Sta/Elev= 30
       0 2140.38    26.2  2136.5    52.5 2131.12    62.3 2127.48    88.5  2114.9
   101.7 2111.52   114.8 2111.33   127.9 2114.51     164 2116.78     200 2116.67
   219.7 2116.43     246    2114   265.6 2115.96   318.1 2113.99   341.1 2114.36
   354.2 2113.71   370.6 2110.88   383.7    2111   400.1 2110.64   413.2 2108.95
   432.9 2109.08   439.4 2111.17   452.6 2125.85   455.8 2128.09   501.8 2150.47
   580.4 2191.35   623.1 2212.27   655.9 2223.58   711.6 2239.36     728  2241.4
#Mann= 6 ,-1 , 0
       0      .1       0     100     .12       0     200      .1       0
     300     .12       0   383.7    .045       0   439.4      .1       0
Bank Sta=383.7,439.4
XS Rating Curve= 0 ,0
Exp/Cntr=0.3,0.1

Type RM Length L Ch R = 1 ,36208   ,319.5,319.6,317.9
XS GIS Cut Line= 3
     2129158.437      227822.597     2129217.695      228181.518
     2129284.241      228540.403
#Sta/Elev= 30
       0 2150.67      36 2143.77    52.4 2137.45    65.6 2136.98    78.7 2133.86
   111.4 2124.44   121.3 2122.77   144.2 2113.35   163.9 2108.46   209.8 2112.97
   249.1 2110.07   268.7 2111.54   314.6 2112.17   321.2 2111.63   334.3 2107.29
     354 2110.47   380.1 2109.85   399.6 2106.16   406.2 2105.82   432.2 2106.68
     442 2110.68     455 2119.37   500.7 2143.62   533.2 2162.45   549.5 2170.79
   569.1  2179.4   604.9 2192.42   637.5 2199.71   696.2 2210.73   728.8 2219.22
#Mann= 3 ,-1 , 0
       0      .1       0   380.1    .045       0     442      .1       0
Bank Sta=380.1,442
XS Rating Curve= 0 ,0
Exp/Cntr=0.3,0.1

Type RM Length L Ch R = 1 ,35889   ,333.5,328.6,322.1
XS GIS Cut Line= 3
     2128840.197      227932.049     2128914.437      228288.398
     2128988.676      228644.747
#Sta/Elev= 30
       0 2171.84    13.1 2163.76    19.7 2160.57    65.6  2143.6    78.7 2138.09
    88.5 2135.36   150.8  2108.9   167.2 2103.57   170.5 2103.33   183.6 2105.37
   216.4 2106.73   239.4 2105.92   311.5 2107.95   331.2 2106.66   344.3 2104.26
   377.1 2103.64     387 2104.34   393.5 2107.13   413.2 2121.11   455.8 2143.22
   475.5 2150.96   501.7  2159.9   541.1 2174.84   583.7 2189.88   613.2 2198.12
   636.2 2205.48     669 2213.65   682.1 2217.82   714.9 2226.41     728  2231.1
#Mann= 3 ,-1 , 0
       0      .1       0   331.2    .045       0   393.5      .1       0
Bank Sta=331.2,393.5
XS Rating Curve= 0 ,0
Exp/Cntr=0.3,0.1

Type RM Length L Ch R = 1 ,35560   ,420.4,421.4,405.3
XS GIS Cut Line= 3
     2128465.316      228014.737     2128592.349      228355.581
     2128717.168      228698.962
#Sta/Elev= 30
       0 2184.84    49.2 2157.66    88.5 2140.73     118 2121.76   147.5 2107.65
   180.2  2100.6   196.6 2103.25   216.3 2104.57   245.8 2103.06   255.6 2100.45
   275.3 2103.46   321.2 2102.12   334.2 2103.41   363.8 2103.16   393.1 2100.56
   412.7 2100.96   419.2 2103.41   432.2 2109.96   451.8  2125.2   458.4 2132.02
   464.9 2142.59   468.1 2146.36   494.2 2166.46   513.8 2185.15   526.9 2191.36
   569.3 2204.06   595.4 2213.27   614.9  2217.7   670.4 2226.14   729.1 2230.58
#Mann= 3 ,-1 , 0
       0      .1       0   363.8    .045       0   419.2      .1       0
Bank Sta=363.8,419.2
XS Rating Curve= 0 ,0
Exp/Cntr=0.3,0.1

Type RM Length L Ch R = 1 ,35139   ,298.3,290.6,275.2
XS GIS Cut Line= 3
     2128018.696      228195.368     2128239.712      228469.745
     2128517.077      228804.232
#Sta/Elev= 30
       0 2200.02    26.1 2184.61    48.9 2169.24    71.8 2156.73   153.3 2106.36
   166.4 2100.27   176.2 2097.66   189.2 2097.42   238.1 2103.19     261 2099.06
   270.8 2099.83   293.6 2097.94   316.4 2100.75   329.5 2097.92   339.3 2096.76
   362.1 2096.81   371.9 2098.43   388.3 2100.91   391.5 2100.69   401.3  2097.1
   437.3 2098.65   453.6 2105.73   473.2 2111.92   512.4 2130.27   528.8 2135.43
   626.8 2154.62   682.3 2163.14   705.2 2168.38   737.8 2173.44   786.8 2184.03
#Mann= 3 ,-1 , 0
       0      .1       0   329.5    .045       0   371.9      .1       0
Bank Sta=329.5,371.9
XS Rating Curve= 0 ,0
Exp/Cntr=0.3,0.1

Type RM Length L Ch R = 1 ,34848   ,511.8,509.1,462.4
XS GIS Cut Line= 3
     2127712.215      228403.441      2127799.02       228511.08
      2128436.77      228891.409
#Sta/Elev= 30
       0 2199.47    19.3 2187.25    28.9 2178.81    54.7 2159.47    64.3 2157.03
    96.5 2138.03   128.6 2121.93   138.3 2119.75   164.4 2109.51   193.9  2095.5
   233.1 2100.33   347.6 2099.87     364 2098.32   383.6 2099.25     400 2097.43
   419.6 2098.59   429.4 2096.83   442.5 2094.96   507.9 2095.14   514.5 2097.13
   524.3 2099.56     557 2099.96   586.4 2112.71   602.8  2118.3   619.1 2121.34
   645.3 2124.66   753.2 2132.53     822 2140.27   854.7 2144.88   880.8 2152.68
#Mann= 5 ,-1 , 0
       0      .1       0  408.28     .12       0   429.4    .045       0
   514.5     .12       0  758.28      .1       0
Bank Sta=429.4,514.5
XS Rating Curve= 0 ,0
Exp/Cntr=0.3,0.1

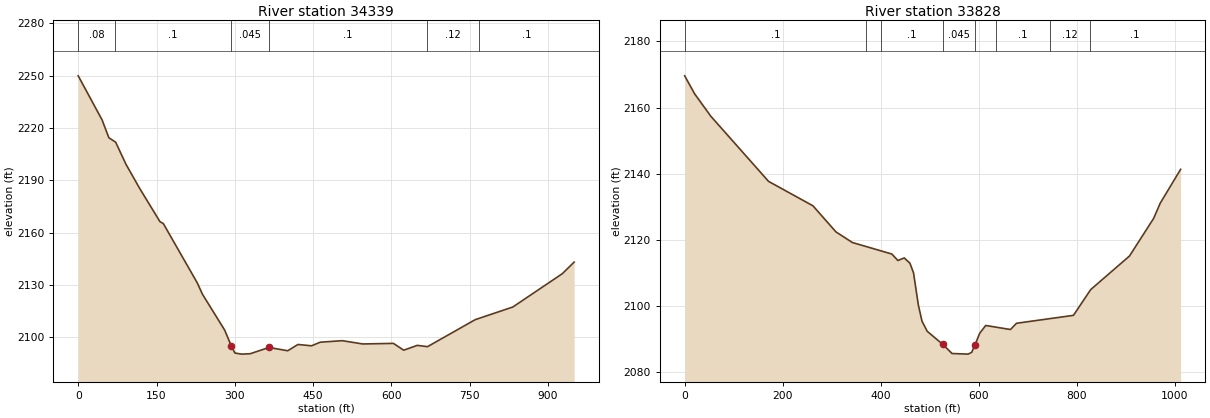
Type RM Length L Ch R = 1 ,34339   ,545.5,511.4,442.9
XS GIS Cut Line= 3
     2127476.104      229021.497     2127726.104      228958.997
     2128417.076      228913.858
#Sta/Elev= 30
       0  2249.9    45.7 2224.65    58.7 2214.42    71.8 2211.84    91.3 2199.31
   117.4 2185.53   156.6 2166.31   163.1 2165.18   228.3 2131.09   238.1 2124.65
   280.6 2104.12   293.6 2094.82   300.2 2090.98   313.2 2090.35   329.6 2090.58
   365.5 2094.18   401.4 2092.28     421 2095.88   447.1 2095.12   463.5 2097.18
   505.9 2098.06   545.1 2096.18   603.9 2096.51   623.5 2092.61   649.6 2095.37
   669.2 2094.63   760.7 2110.13   832.6 2117.36   927.3 2136.44   950.1 2143.11
#Mann= 6 ,-1 , 0
       0     .08       0      70      .1       0   293.6    .045       0
   365.5      .1       0  667.69     .12       0  767.69      .1       0
Bank Sta=293.6,365.5
XS Rating Curve= 0 ,0
Exp/Cntr=0.3,0.1

Type RM Length L Ch R = 1 ,33828   ,331.6,364.2,407.7
XS GIS Cut Line= 4
2127644.20128661229410.2157012382128069.72103111229319.369524645
     2128229.576      228972.886      2128424.02      228952.052
#Sta/Elev= 30
       0 2169.58    20.2 2164.16    53.4 2157.36   171.2 2137.67   261.8 2130.29
   308.7 2122.41   342.3 2119.19   422.8 2115.71   435.1 2113.76   448.1 2114.53
   459.7 2112.95   467.1 2110.01     477 2100.22   484.4  2095.4   495.1 2092.34
   526.42088.455   545.7 2085.64   578.4 2085.45   585.8 2085.99   592.6 2088.28
   602.2 2091.77   614.4 2094.11   664.9 2092.89   677.3 2094.78   793.5 2097.17
   828.6 2104.95   907.8  2115.1   957.3 2126.52   970.5 2131.06  1012.2 2141.31
#Mann= 8 ,-1 , 0
       0      .1       0     370     .12       0     400      .1       0
   526.4    .045       0   592.6     .12       0  635.11      .1       0
  745.11     .12       0  826.69      .1       0
Bank Sta=526.4,592.6
XS Rating Curve= 0 ,0
Exp/Cntr=0.3,0.1