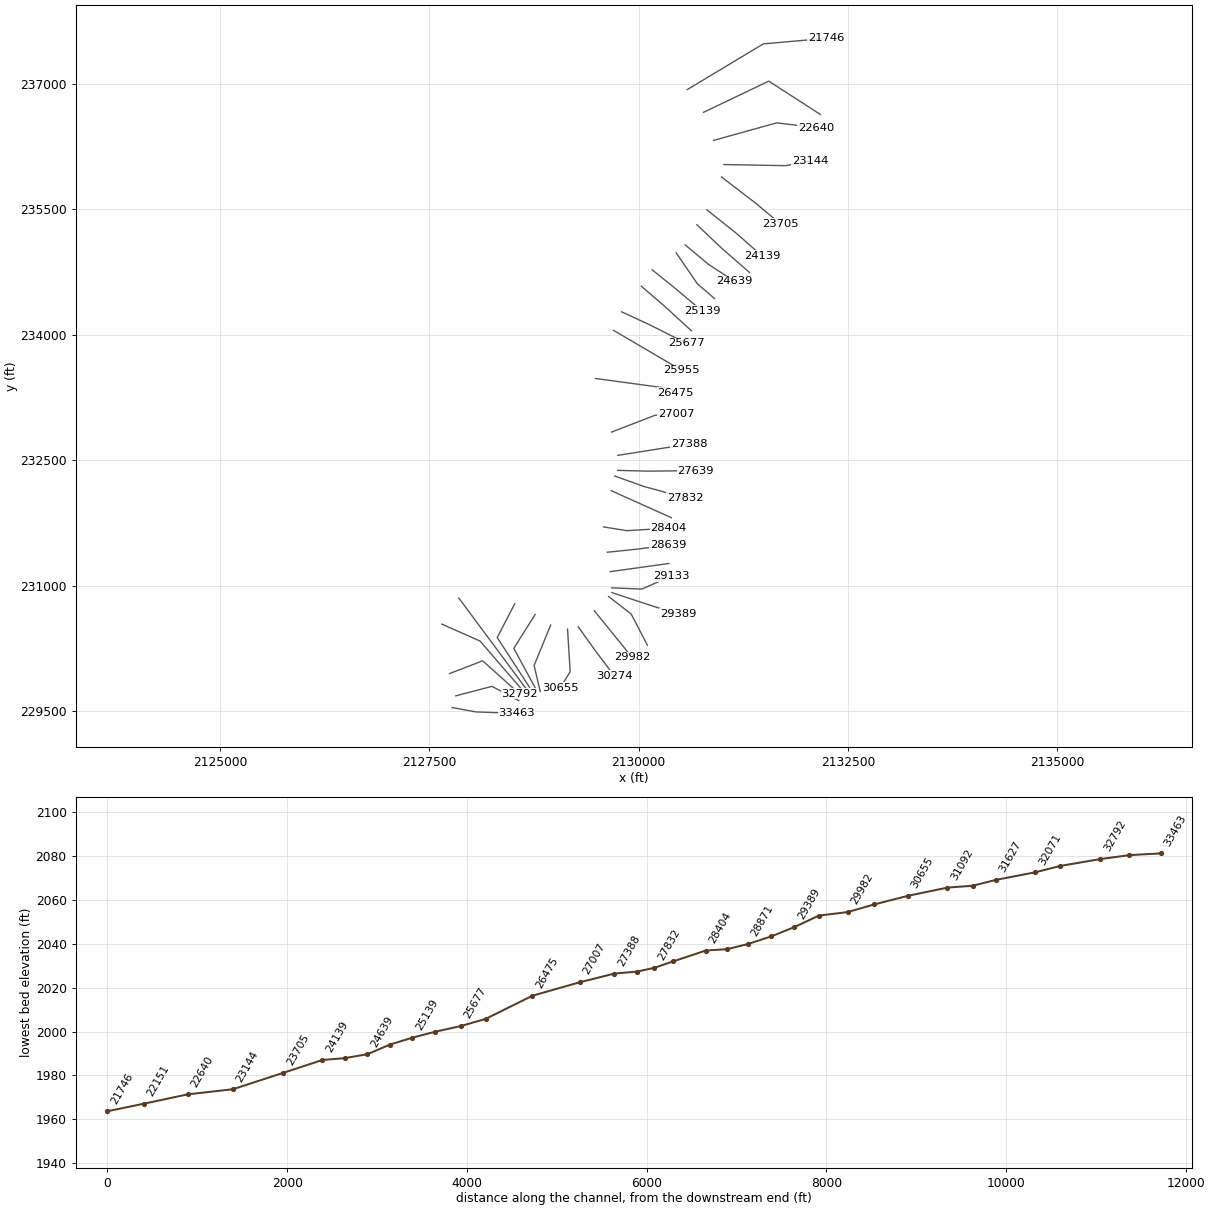
HEC-RAS study SECONDCK.prj: SECONDCK

--- SECONDCK.g01 (geometry) --- (continued)

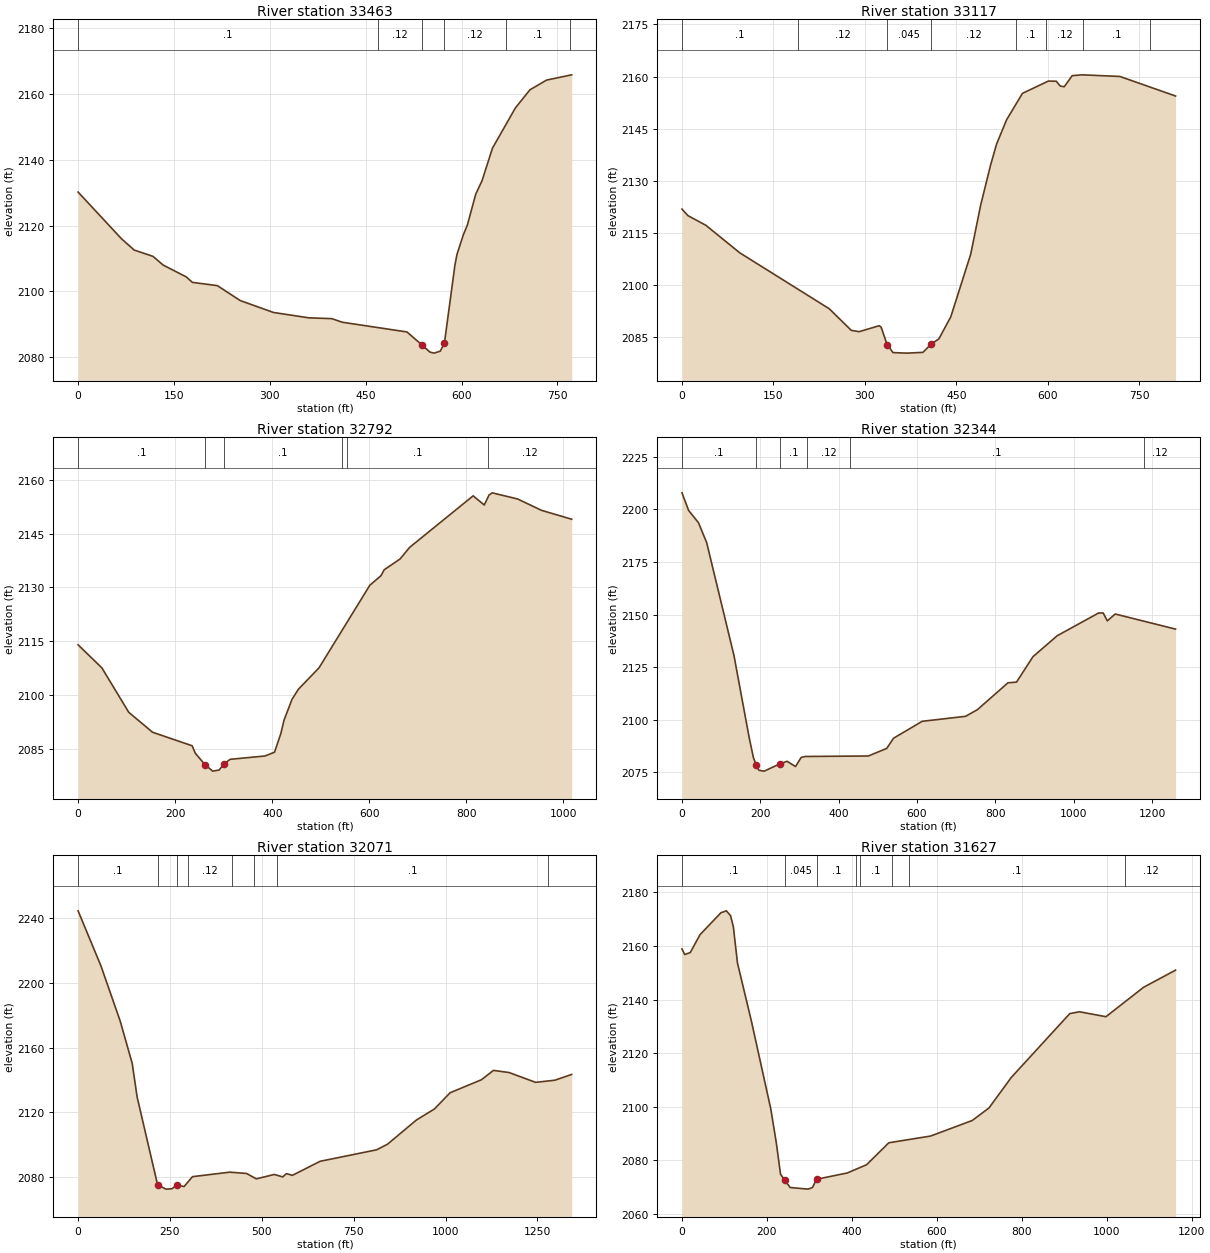
Type RM Length L Ch R = 1 ,33463   ,340.9,346.5,346.8
XS GIS Cut Line= 3
     2127771.243       229542.33     2128055.965      229490.247
     2128538.604      229472.886
#Sta/Elev= 30
       0 2130.17    68.3 2115.92    87.8 2112.57   117.1 2110.66   133.3 2107.99
   169.1 2104.44   178.9 2102.76   217.9 2101.77   253.7 2097.24   305.8 2093.62
   361.2 2091.99   397.1 2091.75   413.4 2090.66   514.6 2087.71   537.4 2083.89
   550.5 2081.61     557 2081.28   566.8 2081.88   573.3 2084.39   589.7 2108.01
   592.9 2111.26   602.7 2117.11   609.2  2120.2   622.3 2129.57   632.1  2133.6
   648.4 2143.49   684.3 2155.71   707.1 2161.22   733.2 2164.17   772.4 2165.76
#Mann= 6 ,-1 , 0
       0      .1       0  469.45     .12       0   537.4    .045       0
   573.3     .12       0  669.45      .1       0  769.45     .12       0
Bank Sta=537.4,573.3
XS Rating Curve= 0 ,0
Exp/Cntr=0.3,0.1

Type RM Length L Ch R = 1 ,33117   ,316.9,325.3,333.2
XS GIS Cut Line= 3
     2127814.188      229682.364     2128246.937      229795.802
     2128566.381      229625.663
#Sta/Elev= 30
       0  2121.9     9.8 2120.02    39.2 2117.24    94.7 2109.34   241.6 2093.24
   277.6 2087.04   290.6 2086.67   323.3 2088.38   326.6 2087.96   336.3 2082.96
   346.1 2080.65     369  2080.5   395.1 2080.72   408.2 2083.05   421.2 2084.59
   440.8 2090.96   473.5 2108.99   489.8 2123.09   506.1 2134.62   515.8 2140.57
   532.2 2147.55   558.2 2155.16   600.6 2158.69   613.7 2158.65   620.2 2157.27
   626.7 2157.06   639.8 2160.25     656 2160.49     718 2160.02   809.3  2154.4
#Mann= 8 ,-1 , 0
       0      .1       0     190     .12       0   336.3    .045       0
   408.2     .12       0  547.37      .1       0  597.37     .12       0
  657.37      .1       0  767.37     .12       0
Bank Sta=336.3,408.2
XS Rating Curve= 0 ,0
Exp/Cntr=0.3,0.1

Type RM Length L Ch R = 1 ,32792   ,464.6,448.1,400.6
XS GIS Cut Line= 3
     2127739.993       229948.58     2128135.826      230101.358
     2128576.798      229705.524
#Sta/Elev= 30
       0 2113.97      49 2107.53   104.4 2095.12   153.4 2089.55     235 2085.77
   241.5 2083.69   261.1 2080.54   277.4 2078.69   290.5 2078.99   300.3 2080.69
   313.3 2081.99   385.1 2082.92   404.7 2083.98   417.8 2089.23   424.3 2092.93
   440.7 2098.74   453.8 2101.55   496.3 2107.53   601.1 2130.62     624 2133.27
   630.6 2134.93   663.3 2137.94   682.9 2141.17   813.9 2155.58   836.8 2153.02
   846.6  2155.8   853.2 2156.42   905.6  2154.7   954.7 2151.53  1016.9 2149.05
#Mann= 6 ,-1 , 0
       0      .1       0   261.1    .045       0   300.3      .1       0
  544.29     .12       0  554.29      .1       0  844.29     .12       0
Bank Sta=261.1,300.3
XS Rating Curve= 0 ,0
Exp/Cntr=0.3,0.1

Type RM Length L Ch R = 1 ,32344   ,285,272.5,246.1
XS GIS Cut Line= 3
2127648.47782926230539.855658526     2128104.576      230337.469
     2128601.104       229761.08
#Sta/Elev= 30
       0 2207.92      17 2199.53    42.1 2193.71      63 2184.25   132.6 2130.62
   171.3  2091.7   182.3 2081.97   189.8 2078.21   196.4 2075.92   209.7 2075.53
   249.5 2078.95   268.2 2080.21   289.8 2077.72   304.1 2082.03   314.9  2082.5
   475.7 2082.73   522.6 2086.34     540 2091.18   613.1 2099.23   723.7  2101.6
   753.9 2104.75   832.1 2117.56   853.8 2117.87   895.9 2129.99   957.7 2139.94
  1063.4 2150.76  1075.1 2150.75  1085.6    2147  1105.8 2150.27  1259.8 2143.09
#Mann= 6 ,-1 , 0
       0      .1       0   189.8    .045       0   249.5      .1       0
     320     .12       0     430      .1       0 1178.98     .12       0
Bank Sta=189.8,249.5
XS Rating Curve= 0 ,0
Exp/Cntr=0.3,0.1

Type RM Length L Ch R = 1 ,32071   ,480,443.6,397.8
XS GIS Cut Line= 2
     2127851.104      230851.358     2128651.081       229772.05
#Sta/Elev= 30
       0 2244.32    62.3 2210.29   114.7 2176.26   147.4 2150.12   160.6 2129.58
   216.3 2075.41   239.2 2072.68   255.6 2072.91   268.7 2075.26   288.4 2074.27
   311.3 2080.36   412.9 2083.15   458.7 2082.34     485 2079.01   534.1 2081.73
     557 2080.22   566.9 2082.24   583.3 2081.18   658.6 2089.84   812.6 2096.93
   842.1 2100.38   920.8 2115.31   969.9 2122.13  1012.5 2132.12  1097.7 2140.14
  1130.5 2145.91  1173.1 2144.58  1245.2 2138.53  1297.6 2139.85  1343.4 2143.41
#Mann= 8 ,-1 , 0
       0      .1       0   216.3    .045       0   268.7      .1       0
     300     .12       0     420      .1       0     480     .12       0
     540      .1       0    1280     .12       0
Bank Sta=216.3,268.7
XS Rating Curve= 0 ,0
Exp/Cntr=0.3,0.1

Type RM Length L Ch R = 1 ,31627   ,255.8,251.6,247
XS GIS Cut Line= 3
     2128518.711      230782.149     2128309.437      230379.136
     2128694.854      229785.386
#Sta/Elev= 30
       0 2158.88     6.5  2156.8    19.6 2157.55    42.5 2164.22    91.5 2172.38
   104.5 2173.12   114.3 2171.34   120.9 2167.21   130.7  2153.6   163.4 2131.96
   209.1 2099.13   222.2 2086.35     232 2074.76   241.8 2072.59   254.8 2069.77
   297.3 2069.18   307.1 2069.78   316.9 2072.87   388.8  2075.2   434.5 2078.28
   486.9 2086.49   585.2    2089   683.5 2094.83   722.8 2099.51   775.3  2110.9
   912.9 2134.73   935.9 2135.42   998.1 2133.58  1086.6 2144.55    1162 2150.97
#Mann= 8 ,-1 , 0
       0      .1       0   241.8    .045       0   316.9      .1       0
     410     .12       0     420      .1       0  494.11     .12       0
  534.11      .1       0 1044.11     .12       0
Bank Sta=241.8,316.9
XS Rating Curve= 0 ,0
Exp/Cntr=0.3,0.1

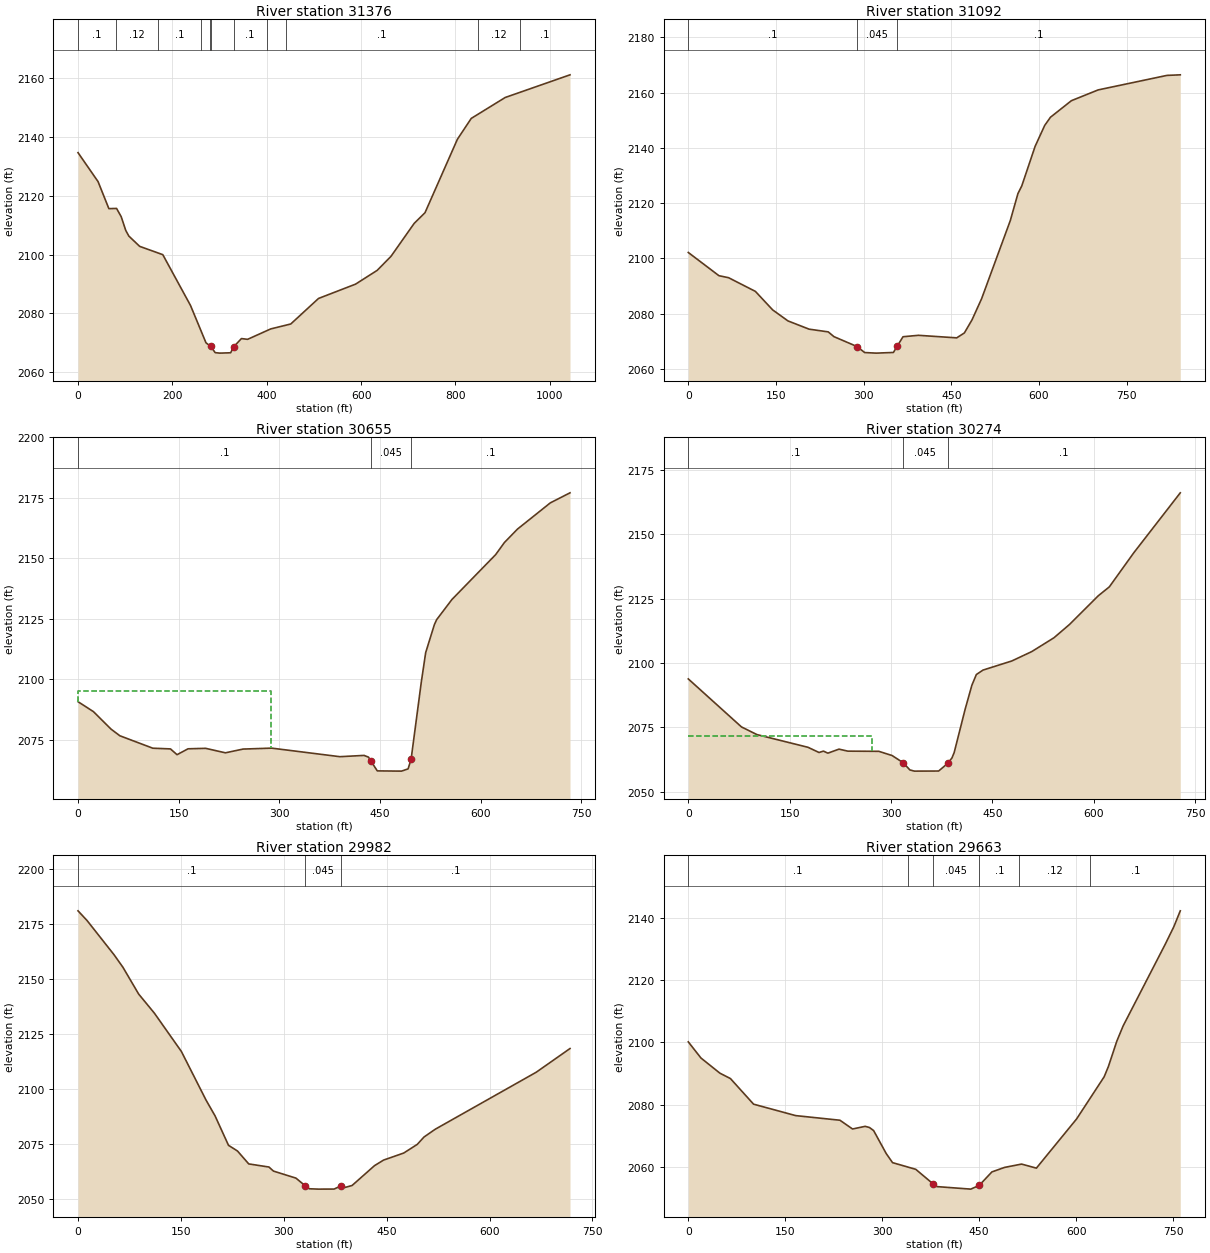
Type RM Length L Ch R = 1 ,31376   ,273.2,283.7,290.1
XS GIS Cut Line= 3
     2128761.997      230654.056     2128507.354      230250.663
     2128776.706      229753.253
#Sta/Elev= 30
       0 2134.58    42.5 2124.75    65.4 2115.58    81.7 2115.65    91.5 2112.86
   101.3 2108.14   107.8 2106.26   130.7 2102.78   179.7 2099.96   238.5  2082.7
   271.2 2070.06     281 2068.86   290.8 2066.71   300.6 2066.55   323.5 2066.67
     330 2068.72   346.4 2071.49   359.4 2071.23   408.4 2074.76   450.9 2076.44
   509.7  2085.1   588.2 2089.96     634 2094.63   663.4 2099.41   712.5 2110.59
   735.4  2114.2     804 2139.11   833.4  2146.2   905.4  2153.3  1042.7 2160.99
#Mann= 11 ,-1 , 0
       0      .1       0      80     .12       0     170      .1       0
     260     .12       0     280      .1       0     281    .045       0
     330      .1       0     400     .12       0     440      .1       0
  847.04     .12       0  937.04      .1       0
Bank Sta=281,330
XS Rating Curve= 0 ,0
Exp/Cntr=0.3,0.1

Type RM Length L Ch R = 1 ,31092   ,413.1,437,449.3
XS GIS Cut Line= 3
     2128948.326      230528.441     2128750.409      230045.802
     2128823.322       229733.95
#Sta/Elev= 30
       0 2102.12    52.5 2093.71    68.9 2092.99   114.8 2088.04   144.4 2081.33
   170.6 2077.34   206.7 2074.36   239.5 2073.37   249.3 2071.64   288.7 2068.07
   301.8 2065.89   321.5 2065.68     351 2065.92   357.6 2068.22   367.4 2071.61
   393.7 2072.13   459.3 2071.21   472.4 2072.98   485.6 2077.76     502 2085.42
     551 2113.65   564.1 2123.45   570.7 2126.24   593.5 2140.55   609.9 2148.12
   619.7 2151.07   655.6 2157.08   701.4 2160.98     819 2166.23   841.9 2166.44
#Mann= 3 ,-1 , 0
       0      .1       0   288.7    .045       0   357.6      .1       0
Bank Sta=288.7,357.6
XS Rating Curve= 0 ,0
Exp/Cntr=0.3,0.1

Type RM Length L Ch R = 1 ,30655   ,353.9,381,398.9
XS GIS Cut Line= 3
     2129149.715       230479.83     2129180.965      229969.413
     2129062.909      229781.913
#Sta/Elev= 30
       0 2090.68      23 2086.56    49.2 2079.33    62.3 2076.59   111.4 2071.44
   137.7 2071.15   147.5 2068.76   163.9 2071.19   190.1 2071.39   219.6 2069.53
   245.8 2071.08   288.5 2071.47   390.1 2067.93   426.1 2068.46   432.7 2067.75
     436 2066.29   445.8 2062.06   481.9 2061.96   491.7 2062.89  496.16 2066.81
   511.4 2098.82   517.9 2110.97   530.9 2122.59   534.2 2124.58     557 2132.94
   622.2 2151.52   635.2 2156.51   654.7 2162.07   703.6 2172.91   732.9 2177.06
#Mann= 3 ,-1 , 0
       0      .1       0     436    .045       0  496.16      .1       0
#XS Ineff= 2 , 0
          287.52  2094.9
Permanent Ineff=
       F       F
Bank Sta=436,496.16
XS Rating Curve= 0 ,0
Exp/Cntr=0.3,0.1

Type RM Length L Ch R = 1 ,30274   ,289.6,292.1,295.1
XS GIS Cut Line= 3
     2129276.509      230509.252     2129488.066      230213.075
      2129707.35      229922.354
#Sta/Elev= 30
       0  2093.8    78.7 2075.15   101.6 2072.17   177.1 2067.24   193.5 2065.22
     200 2065.75   206.6 2064.96     223 2066.52   236.1 2065.74     282 2065.67
   301.7 2064.03   318.1 2061.22   327.9 2058.45   334.5 2057.98   370.5 2058.02
   383.7 2060.95   390.2 2063.09   393.5 2065.21   409.9  2082.2   419.7 2091.35
   426.3  2095.5   436.2 2097.23   478.8 2100.77   508.3 2104.41   541.1 2109.77
   564.1 2114.93   606.7 2126.08   623.1 2129.55   659.2 2142.76   728.1 2166.08
#Mann= 3 ,-1 , 0
       0      .1       0   318.1    .045       0   383.7      .1       0
#XS Ineff= 2 , 0
          271.58 2071.61
Permanent Ineff=
       F       F
Bank Sta=318.1,383.7
XS Rating Curve= 0 ,0
Exp/Cntr=0.3,0.1

Type RM Length L Ch R = 1 ,29982   ,322.7,319.3,304.8
XS GIS Cut Line= 2
     2129468.849      230700.182     2129920.548      230143.024
#Sta/Elev= 30
       0 2181.11    13.1 2176.73    52.4 2161.19    65.5 2155.43    88.4 2143.26
   111.4 2134.54   150.7 2117.14   186.7    2095   199.8 2087.85   219.4 2074.45
   232.5 2071.86   248.9 2065.99   278.4 2064.57   284.9 2062.73   317.7 2059.53
   330.8 2056.16   337.3 2054.68   350.4 2054.52   373.4 2054.55   383.2 2055.98
   389.7 2055.32   399.6 2056.18   432.3  2065.2   445.4 2067.72   474.9 2070.94
   494.6 2074.87   504.4 2078.21   520.8 2081.76   668.1  2107.7   717.3 2118.47
#Mann= 3 ,-1 , 0
       0      .1       0   330.8    .045       0   383.2      .1       0
Bank Sta=330.8,383.2
XS Rating Curve= 0 ,0
Exp/Cntr=0.3,0.1

Type RM Length L Ch R = 1 ,29663   ,241.2,273.9,307
XS GIS Cut Line= 3
     2129640.005      230870.214     2129910.131      230660.386
     2130102.689      230288.154
#Sta/Elev= 30
       0 2100.14    19.6 2094.96    48.9  2090.1    65.2 2088.37     101 2080.16
   166.1 2076.49   234.6 2075.01   254.1  2072.2   273.6 2073.05   280.2 2072.68
   286.7  2071.7   306.2 2064.32     316 2061.41   351.9 2059.27   378.1 2054.71
   384.6 2053.73     437 2052.92   450.1 2054.13   469.7 2058.44   489.4 2059.89
   515.6 2060.95   538.5 2059.65   600.7 2075.42   643.3 2088.92   649.8 2092.17
   662.9 2100.35   672.7 2105.25   738.2 2131.59   751.3 2137.14   761.1 2142.15
#Mann= 6 ,-1 , 0
       0      .1       0     340     .12       0   378.1    .045       0
   450.1      .1       0  512.05     .12       0  622.05      .1       0
Bank Sta=378.1,450.1
XS Rating Curve= 0 ,0
Exp/Cntr=0.3,0.1

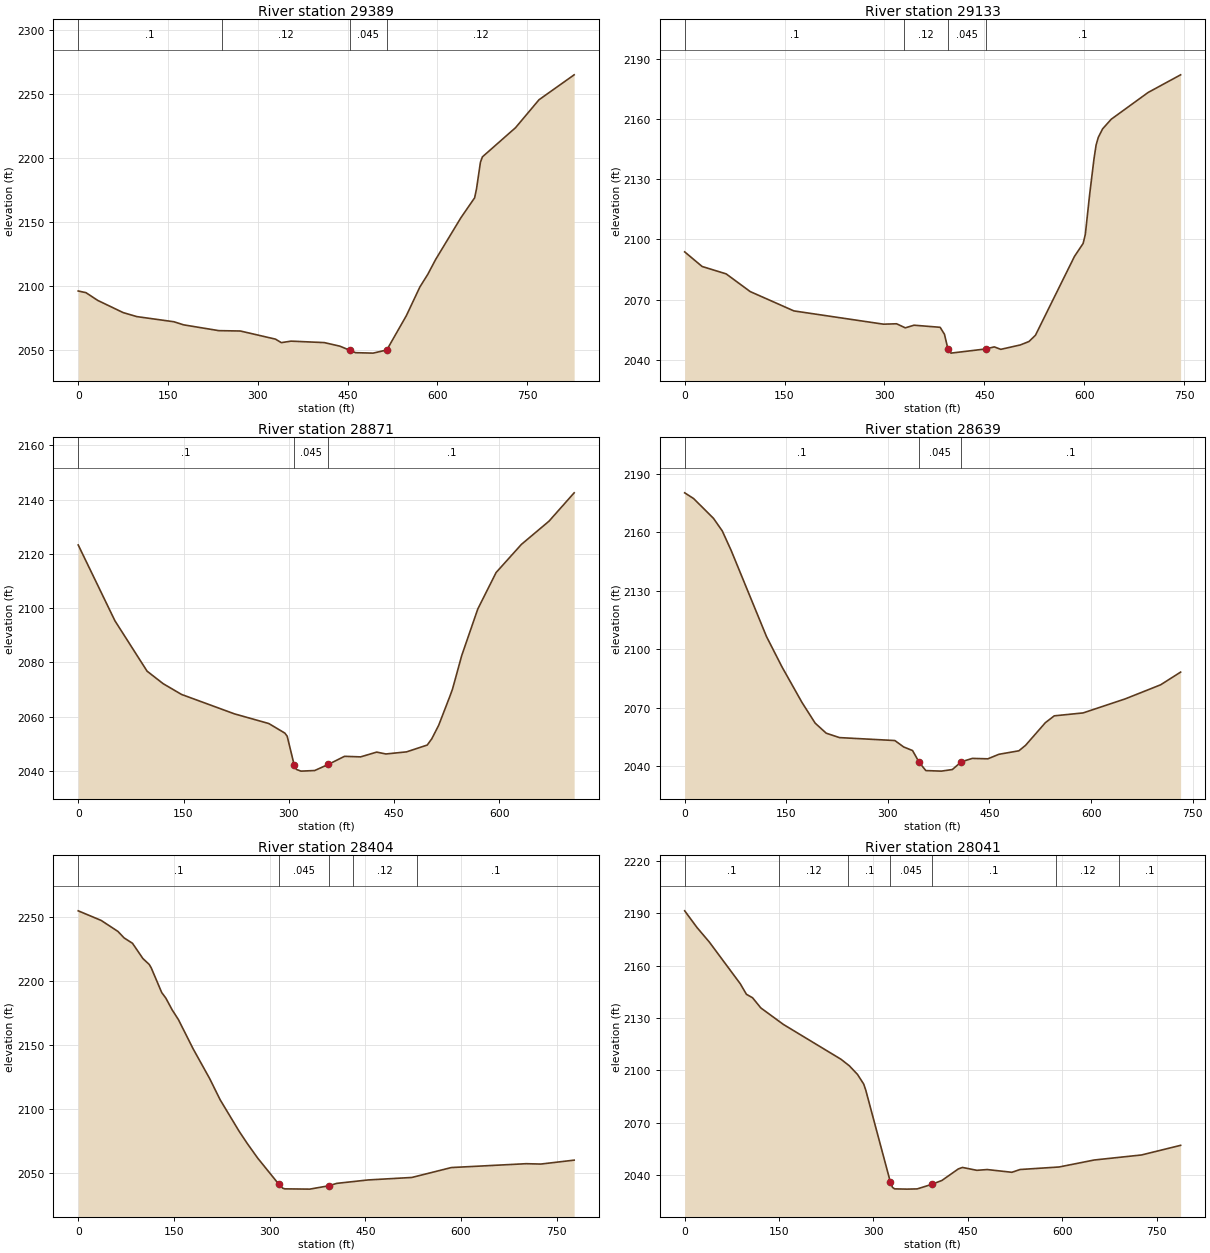
Type RM Length L Ch R = 1 ,29389   ,227.6,255.4,279.9
XS GIS Cut Line= 3
     2129680.077      230916.509     2130141.581      230763.388
     2130468.114      230660.272
#Sta/Elev= 30
       0 2096.26      13 2094.94    32.6  2088.9    75.1 2079.37    97.9 2076.24
   159.9 2072.21   176.2 2069.79     235 2065.26   270.9 2064.98   329.6 2058.63
   339.4 2055.89   355.7 2057.06   411.2 2055.92   437.3 2053.12   453.6 2049.94
   463.4 2048.04   492.8 2047.69   515.6 2050.15   548.2 2076.86     571 2099.46
   584.1 2109.25   597.1 2120.76   639.5 2153.54   662.4 2169.08   665.6 2176.22
   672.1 2196.86   675.4 2201.09   730.8 2223.91     770 2245.73   828.7 2265.21
#Mann= 4 ,-1 , 0
       0      .1       0     240     .12       0   453.6    .045       0
   515.6     .12       0
Bank Sta=453.6,515.6
XS Rating Curve= 0 ,0
Exp/Cntr=0.3,0.1

Type RM Length L Ch R = 1 ,29133   ,266.3,262,246.9
XS GIS Cut Line= 3
     2129678.062       230972.72     2130038.604      230958.997
     2130389.298      231115.247
#Sta/Elev= 30
       0 2093.81    26.2 2086.54    62.3 2082.86    98.4 2074.06     164 2064.44
   298.5 2057.84   318.2 2058.04   331.3 2056.02   344.4 2057.33   383.6 2056.29
   390.1 2052.81  395.34 2045.48   399.8 2043.44   451.9 2045.51   464.9 2046.54
   474.7 2045.32     504 2047.51     517 2049.22   526.7 2052.32   585.3 2091.55
   598.3    2098   601.6 2102.48   608.1 2122.36   614.6 2140.02   617.8 2146.99
   621.1 2150.79   627.6 2155.03   640.6 2159.82   695.9 2173.11   744.7 2181.89
#Mann= 4 ,-1 , 0
       0      .1       0     330     .12       0  395.34    .045       0
   451.9      .1       0
Bank Sta=395.34,451.9
XS Rating Curve= 0 ,0
Exp/Cntr=0.3,0.1

Type RM Length L Ch R = 1 ,28871   ,229.9,232.7,229.9
XS GIS Cut Line= 2
     2129660.131       231167.33     2130359.923      231264.721
#Sta/Elev= 30
       0 2123.29    52.3 2095.35    98.1 2076.78     121 2072.17   147.2  2068.2
   222.4 2061.06   271.5 2057.48   294.4 2053.95   297.7  2052.8   307.5 2042.38
   310.8 2040.57   317.3 2039.94   336.9 2040.16   356.5 2042.44   379.4  2045.4
   402.3 2045.19   425.2 2046.95   438.3 2046.26   467.8 2047.04   497.2 2049.55
   503.7 2051.86   513.6 2056.88   529.9 2067.81   533.2 2070.16   546.3  2082.5
   569.2 2099.67   595.3 2113.12   631.3 2123.48   670.6 2132.03   706.5  2142.5
#Mann= 3 ,-1 , 0
       0      .1       0   307.5    .045       0   356.5      .1       0
Bank Sta=307.5,356.5
XS Rating Curve= 0 ,0
Exp/Cntr=0.3,0.1

Type RM Length L Ch R = 1 ,28639   ,238.3,234.9,229.1
XS GIS Cut Line= 3
     2129624.276      231398.949     2129991.318      231437.432
     2130351.343       231484.65
#Sta/Elev= 30
       0 2180.28    13.1 2177.37    42.5 2167.21    55.5 2160.74    68.6 2150.76
   120.8 2106.59   143.7 2091.01   173.1 2072.86   192.7 2062.17     209 2057.03
   228.6 2054.78   310.3 2053.27   323.3 2049.99   336.4 2048.14   346.2 2042.13
     356 2037.87   378.9 2037.59   395.2 2038.41   408.3 2042.34   424.7 2044.12
   447.6  2043.9   463.9 2046.22   493.4 2048.01   503.2 2050.79   532.6 2062.46
   545.7 2065.94   588.2 2067.43   650.4 2074.63   702.7 2081.85   732.2 2088.36
#Mann= 3 ,-1 , 0
       0      .1       0   346.2    .045       0   408.3      .1       0
Bank Sta=346.2,408.3
XS Rating Curve= 0 ,0
Exp/Cntr=0.3,0.1

Type RM Length L Ch R = 1 ,28404   ,375.3,362.4,330.7
XS GIS Cut Line= 3
      2129580.27      231702.052     2129858.048      231656.913
     2130353.059      231687.186
#Sta/Elev= 30
       0 2255.15      36 2247.62    62.2 2239.03      72 2233.89    85.1  2229.7
   101.4 2217.75   111.3 2213.12   114.5 2210.41   130.9 2191.09   137.4  2186.7
   147.3 2177.49   157.1 2169.87     180  2147.1   206.2 2123.51   222.5 2107.03
     252 2082.54   265.1  2072.7   281.4 2061.27     314 2041.12   320.6 2037.76
   323.8  2037.2     363 2036.99   392.4 2039.58   405.4 2041.51   454.4 2044.19
   522.9 2046.13   584.9  2053.9   702.3 2056.92   725.2 2056.64   777.4 2059.71
#Mann= 5 ,-1 , 0
       0      .1       0     314    .045       0   392.4      .1       0
  431.42     .12       0  531.42      .1       0
Bank Sta=314,392.4
XS Rating Curve= 0 ,0
Exp/Cntr=0.3,0.1

Type RM Length L Ch R = 1 ,28041   ,206.2,209.9,216.6
XS GIS Cut Line= 2
     2129670.767      232135.103     2130389.517      231812.186
#Sta/Elev= 30
       0 2191.29    19.6 2181.74    39.2 2173.41    88.3 2149.58    98.1 2143.54
   107.9 2141.53     121 2135.72   156.9 2126.27   248.5 2106.32   261.6 2102.62
   274.6 2097.68   284.4  2092.2   287.7 2088.73     327 2035.88   330.2 2033.04
   333.5 2032.19   353.1 2032.04   369.5 2032.17   392.3 2034.74   408.7 2036.99
   434.8  2043.6   441.4 2044.45   464.3  2042.8   480.6 2043.24   519.9 2041.68
   532.9 2043.26     595 2044.71   650.6  2048.7   725.8 2051.58     788  2057.1
#Mann= 7 ,-1 , 0
       0      .1       0     150     .12       0     260      .1       0
     327    .045       0   392.3      .1       0     590     .12       0
     690      .1       0
Bank Sta=327,392.3
XS Rating Curve= 0 ,0
Exp/Cntr=0.3,0.1

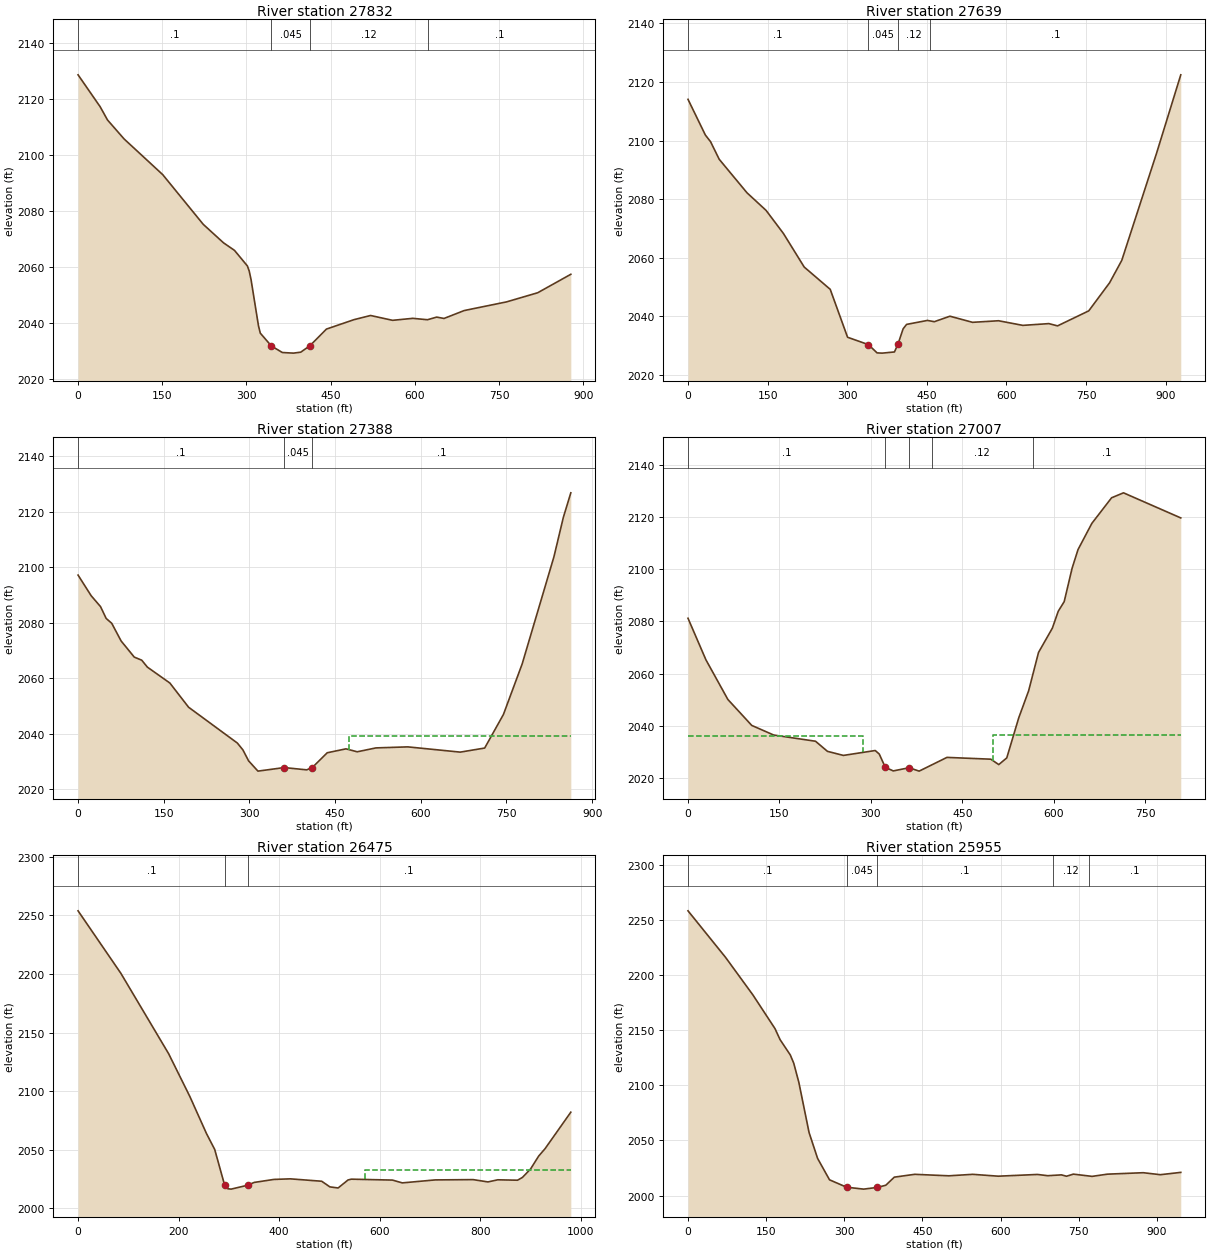
Type RM Length L Ch R = 1 ,27832   ,181.3,192.9,203.6
XS GIS Cut Line= 3
     2129712.742      232310.731     2130055.313      232187.542
     2130550.975       232051.77
#Sta/Elev= 30
       0 2128.63    39.4 2117.21    52.5 2112.48      82 2105.71   150.9 2092.93
     223 2075.18   259.1 2068.57   278.8 2065.84   301.7 2060.29     305 2058.46
   308.3 2055.34   321.4 2038.97   324.7 2036.26   344.4 2031.68     364 2029.33
   383.7 2029.11   396.8 2029.45   413.2 2031.77   442.6 2037.71   491.7 2041.08
   521.2 2042.57   560.4 2040.84   596.5 2041.55   622.6 2041.05     639 2041.99
   652.1 2041.51   688.1 2044.34   763.4 2047.43     819  2050.7     878  2057.3
#Mann= 4 ,-1 , 0
       0      .1       0   344.4    .045       0   413.2     .12       0
  624.05      .1       0
Bank Sta=344.4,413.2
XS Rating Curve= 0 ,0
Exp/Cntr=0.3,0.1

Type RM Length L Ch R = 1 ,27639   ,245.2,250.9,255.6
XS GIS Cut Line= 3
     2129747.568      232377.681     2130113.577      232368.546
     2130675.975      232374.686
#Sta/Elev= 30
       0 2114.07    32.7 2101.88    42.5  2099.6    58.8 2093.59   111.1 2082.16
   147.1 2076.14   179.8 2068.25     219 2056.78     268 2049.17   300.7  2032.8
     340 2030.28   356.3 2027.46   366.1 2027.38     389 2027.78   395.6 2030.42
   405.4 2035.69   411.9 2037.19   451.1 2038.55   464.2 2038.12   493.6 2039.99
   536.2  2037.9   585.2 2038.44     631 2036.86     680 2037.46   696.4 2036.69
   755.2 2041.82   794.5 2051.42   817.4 2059.06   882.8 2095.56   928.6 2122.44
#Mann= 4 ,-1 , 0
       0      .1       0     340    .045       0   395.6     .12       0
  456.12      .1       0
Bank Sta=340,395.6
XS Rating Curve= 0 ,0
Exp/Cntr=0.3,0.1

Type RM Length L Ch R = 1 ,27388   ,372.5,380.9,388.8
XS GIS Cut Line= 2
     2129751.039      232557.539     2130603.059      232692.395
#Sta/Elev= 30
       0 2097.15      23  2089.7    39.4 2085.77    49.2 2081.53      59 2079.76
    75.4  2073.4    98.4 2067.59   111.5 2066.47   121.4 2063.97   160.7 2058.25
   193.5 2049.52   278.8 2036.62   288.6 2034.14   298.5 2030.21   314.9 2026.49
   360.8 2027.77   400.2 2026.95     410 2027.78   436.2 2033.11     469 2034.52
   488.7 2033.46   521.5 2034.86   577.3 2035.23   669.1 2033.34   711.8 2034.81
   744.6  2046.9   777.4  2065.1   833.1 2103.79   849.5 2117.95   862.6  2126.8
#Mann= 3 ,-1 , 0
       0      .1       0   360.8    .045       0     410      .1       0
#XS Ineff= 2 , 0
                             475         2039.11
Permanent Ineff=
       F       F
Bank Sta=360.8,410
XS Rating Curve= 0 ,0
Exp/Cntr=0.3,0.1

Type RM Length L Ch R = 1 ,27007   ,540.8,531.9,506
XS GIS Cut Line= 3
     2129675.756      232835.733     2130193.986      233036.254
      2130446.59       233046.67
#Sta/Elev= 30
       0 2081.23    29.4 2065.29    65.4 2050.07   104.6 2040.11   140.6 2036.42
   209.2 2034.04   228.8 2030.16     255  2028.6   307.2 2030.48   313.8 2029.12
   323.6 2024.07   336.7 2022.65   362.8 2023.87   379.2 2022.57   424.9 2027.84
   496.8 2027.15   509.9 2025.08     523 2027.65   542.6 2042.99   558.9 2053.41
   575.1 2068.11   597.8 2077.44   607.5 2083.94   617.2  2087.6   630.2 2100.43
   639.9 2107.58   662.6 2117.65     695 2127.47   714.5 2129.37   808.5 2119.74
#Mann= 5 ,-1 , 0
       0      .1       0   323.6    .045       0   362.8      .1       0
     400     .12       0  565.67      .1       0
#XS Ineff= 2 , 0
          286.96 2035.96  500.01         2036.26
Permanent Ineff=
       F       F
Bank Sta=323.6,362.8
XS Rating Curve= 0 ,0
Exp/Cntr=0.3,0.1

Type RM Length L Ch R = 1 ,26475   ,529,519.7,499.3
XS GIS Cut Line= 3
     2129483.048      233476.358     2130365.861      233356.566
     2130438.777      233304.483
#Sta/Elev= 30
       0 2253.96    85.2 2200.61   180.2 2132.01   222.7 2095.23   255.5 2063.86
   271.9 2050.26   291.5 2020.03   298.1 2016.66   304.6 2016.37   337.4  2019.7
   350.5 2022.09   389.8 2024.66   422.5 2025.14   484.8  2023.1   501.1 2018.28
   517.5 2017.36   537.2 2024.19   543.7 2024.87   625.6 2024.09   645.2  2021.7
   710.8 2024.24   786.1 2024.49   815.6 2022.52   835.2 2024.33   874.5 2023.98
   884.4 2026.42   900.5 2033.64   916.5 2044.55   929.3 2050.93   980.5 2082.06
#Mann= 3 ,-1 , 0
       0      .1       0   291.5    .045       0   337.4      .1       0
#XS Ineff= 2 , 0
                          571.82         2032.42
Permanent Ineff=
       F       F
Bank Sta=291.5,337.4
XS Rating Curve= 0 ,0
Exp/Cntr=0.3,0.1

Type RM Length L Ch R = 1 ,25955   ,276.5,278,281.3
XS GIS Cut Line= 2
     2129699.194      234051.879     2130514.517      233572.603
#Sta/Elev= 30
       0 2258.07      72 2215.92   124.4 2181.95   166.9 2151.35   176.7 2141.32
   196.4 2127.36   202.9 2120.01   212.7 2102.65   232.4 2057.04   248.7 2033.69
   271.6 2014.26   304.3 2007.56   337.1 2005.81   363.2 2007.36   379.6 2009.32
     396 2016.67   435.2 2019.23   500.7 2017.88   546.5 2019.22   595.6 2017.54
   670.9 2019.11   690.5 2017.97   716.7 2018.74   726.5 2017.49   739.6  2019.4
   775.6 2017.37     805 2019.38   873.8 2020.69   906.5 2018.89   945.8 2020.98
#Mann= 5 ,-1 , 0
       0      .1       0   304.3    .045       0   363.2      .1       0
     700     .12       0     770      .1       0
Bank Sta=304.3,363.2
XS Rating Curve= 0 ,0
Exp/Cntr=0.3,0.1

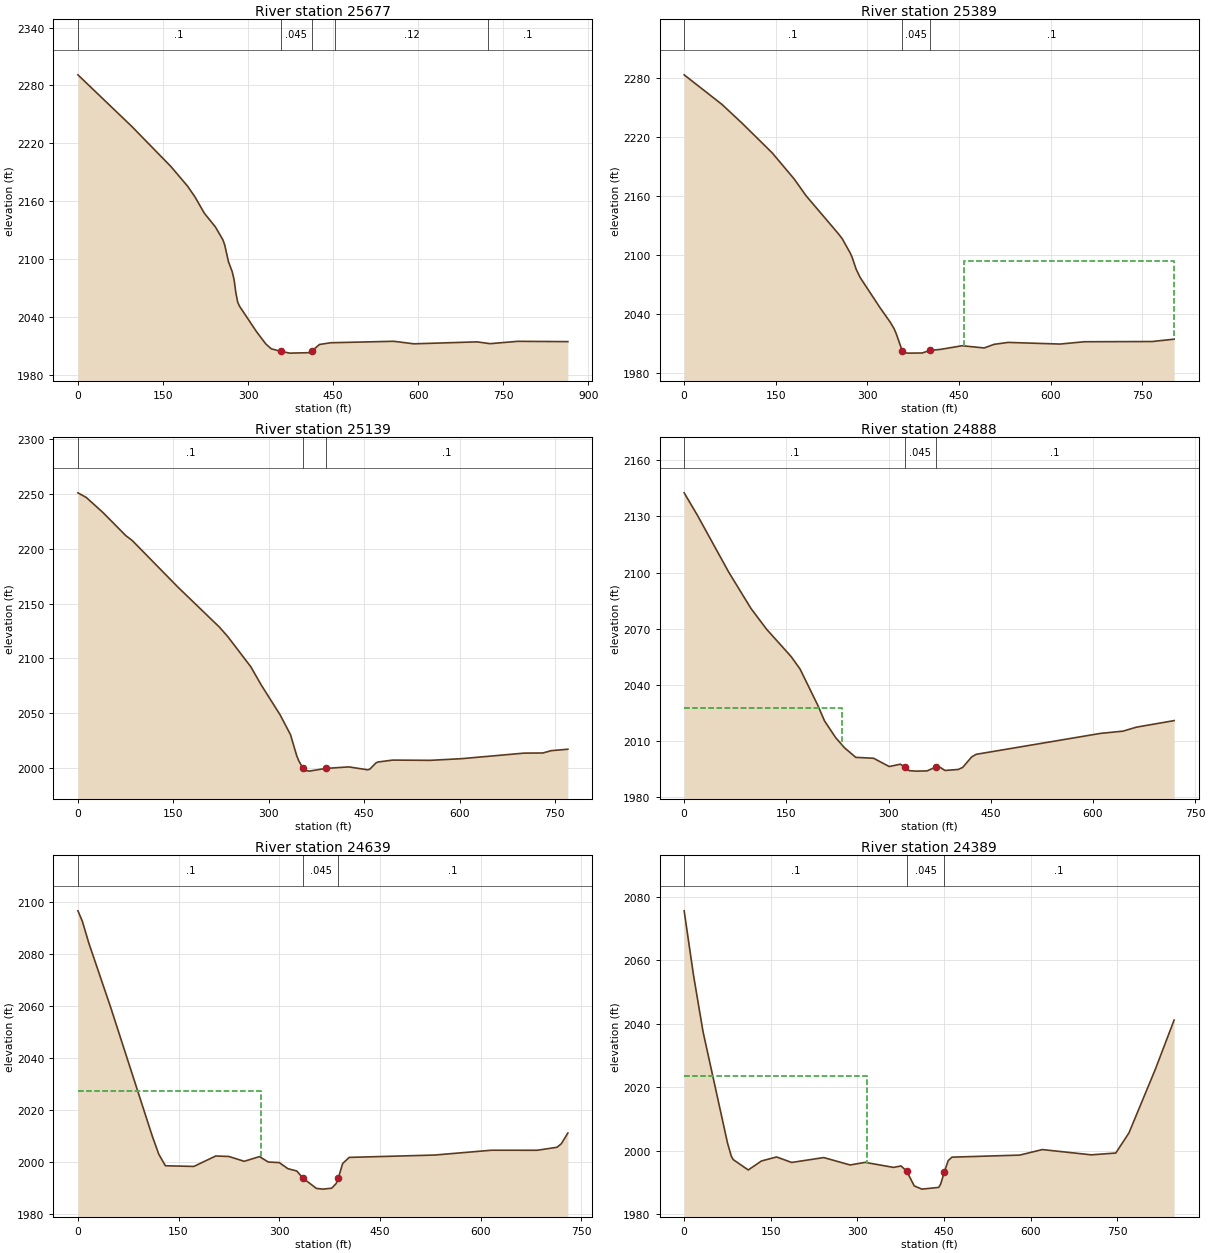
Type RM Length L Ch R = 1 ,25677   ,295,288.6,274.8
XS GIS Cut Line= 3
     2129795.199      234273.264     2130125.484      234120.827
     2130571.809       233895.52
#Sta/Elev= 30
       0 2290.97      95 2237.48   163.9 2195.96   193.4 2175.53   206.5  2164.3
   222.8 2147.61   242.5 2133.22   255.6 2119.96   258.9 2114.41   265.4 2097.24
     272 2086.98   275.3 2078.65   278.6 2064.54   281.8 2055.01   285.1 2050.99
   314.6 2024.97     331  2012.2   340.8 2007.04   357.2  2004.4   373.6 2002.53
   406.2 2002.96   412.8 2004.95   425.8  2011.5   445.5 2013.28   556.6  2014.8
   592.5 2012.18   703.6  2014.2   726.5 2012.34   775.5 2014.77   863.7 2014.44
#Mann= 5 ,-1 , 0
       0      .1       0   357.2    .045       0   412.8      .1       0
  453.77     .12       0  723.77      .1       0
Bank Sta=357.2,412.8
XS Rating Curve= 0 ,0
Exp/Cntr=0.3,0.1

Type RM Length L Ch R = 1 ,25389   ,248.5,250,252.4
XS GIS Cut Line= 3
     2130029.974      234580.092     2130310.587      234338.748
       2130629.1      234046.561
#Sta/Elev= 30
       0  2283.2    62.2 2252.94      95 2233.88   144.1 2203.82   180.2 2177.16
   199.8 2160.01   252.2 2121.72   258.8 2116.45   271.9 2101.91   275.1 2097.48
   281.7 2085.31   288.2 2076.94     321 2045.94   337.4  2031.5   343.9 2024.69
   347.2  2019.9     357 2002.56   360.3 2000.28   366.8 1999.91   389.8 2000.05
   402.9 2002.82   419.2 2003.65   455.3 2007.44   491.3 2005.18   507.6 2008.85
   530.6 2010.82   615.7 2009.14     655 2011.49   766.3 2011.72   802.4 2014.11
#Mann= 3 ,-1 , 0
       0      .1       0     357    .045       0   402.9      .1       0
#XS Ineff= 2 , 0
                          457.76         2093.75
Permanent Ineff=
       F       F
Bank Sta=357,402.9
XS Rating Curve= 0 ,0
Exp/Cntr=0.3,0.1

Type RM Length L Ch R = 1 ,25139   ,257.1,251.1,241
XS GIS Cut Line= 3
     2130159.565      234775.917     2130442.753      234547.793
       2130754.1      234286.145
#Sta/Elev= 30
       0 2250.86    13.1 2246.66    39.3 2232.96    75.4 2211.79    85.2 2207.54
   157.2 2164.95   222.8  2128.3   235.9 2119.63   271.9 2092.28   288.3 2075.66
   317.8 2048.64   334.2 2030.49     344 2011.31   347.3 2006.57   353.8 1999.95
   357.1 1997.96   363.6 1997.24   389.9 1999.72     426 2001.09   455.5 1998.45
   458.8 1998.96   468.6 2004.76   471.9 2005.56   494.8 2007.29   553.9 2007.08
   603.1 2008.58   701.5 2013.65     731 2013.76   744.1 2015.89   770.3  2017.2
#Mann= 3 ,-1 , 0
       0      .1       0   353.8    .045       0   389.9      .1       0
Bank Sta=353.8,389.9
XS Rating Curve= 0 ,0
Exp/Cntr=0.3,0.1

Type RM Length L Ch R = 1 ,24888   ,238.2,248.9,261.1
XS GIS Cut Line= 3
      2130446.59      234978.962     2130701.798      234606.566
     2130904.923      234432.087
#Sta/Elev= 30
       0 2142.51    19.6 2130.45    65.4 2100.22    98.1 2080.82     121 2069.75
     157 2055.17   170.1 2048.55   196.3 2029.07   206.1  2020.8   222.5 2011.87
   235.5 2006.47   251.9  2001.4   278.1 2000.91     301  1996.5   317.3 1997.74
   323.9 1996.37   330.4 1994.31   340.2 1994.05   356.6 1994.18   369.7 1996.29
   376.2 1995.98   382.8 1994.41   402.4 1994.94   408.9 1996.04     422 2001.61
   428.6 2003.01   611.5  2014.2   644.1 2015.37   663.7 2017.49   719.2    2021
#Mann= 3 ,-1 , 0
       0      .1       0   323.9    .045       0   369.7      .1       0
#XS Ineff= 2 , 0
          231.58 2027.54
Permanent Ineff=
       F       F
Bank Sta=323.9,369.7
XS Rating Curve= 0 ,0
Exp/Cntr=0.3,0.1

Type RM Length L Ch R = 1 ,24639   ,251.5,250,244.9
XS GIS Cut Line= 3
     2130554.766      235073.077     2130835.061      234838.973
     2131140.933      234639.883
#Sta/Elev= 30
       0 2096.61     6.5  2092.7    16.3 2084.19    48.9 2059.47   110.9 2010.01
   120.6 2003.06   130.4 1998.67   172.8 1998.41   205.4 2002.42     225 2002.24
   247.8 2000.38   270.6 2002.19   283.7  2000.1     300 1999.89     313 1997.54
   326.1 1996.67   335.8 1993.82   355.4 1989.97   365.2 1989.69   378.2 1990.05
   384.8 1991.82     388 1993.84   394.5 1999.51   404.3 2001.88   531.4 2002.78
   616.1 2004.63   684.5 2004.62   713.9 2005.76   720.4 2007.12   730.2 2011.24
#Mann= 3 ,-1 , 0
       0      .1       0   335.8    .045       0     388      .1       0
#XS Ineff= 2 , 0
          272.38  2027.3
Permanent Ineff=
       F       F
Bank Sta=335.8,388
XS Rating Curve= 0 ,0
Exp/Cntr=0.3,0.1

Type RM Length L Ch R = 1 ,24389   ,246.9,250,251.2
XS GIS Cut Line= 3
     2130693.986      235314.899     2130990.029      235033.807
     2131321.809      234744.478
#Sta/Elev= 30
       0 2075.66    16.3 2055.25    32.7 2037.55    75.1 2002.45    81.6 1998.33
    84.9 1997.24     111 1993.96   133.9  1996.8     160 1998.06   186.2 1996.33
   241.7 1997.87   287.4 1995.54   313.5 1996.36   362.5 1994.77   375.6 1995.23
   385.4 1993.58   398.4 1988.94   411.5 1987.92   440.8 1988.46   444.1 1989.47
   450.6 1993.42   457.2 1996.92   463.7    1998   581.1 1998.65   620.2 2000.39
     705 1998.73   747.4  1999.3   770.2 2005.64   815.8 2025.67   848.4 2041.21
#Mann= 3 ,-1 , 0
       0      .1       0   385.4    .045       0   450.6      .1       0
#XS Ineff= 2 , 0
          316.52 2023.49
Permanent Ineff=
       F       F
Bank Sta=385.4,450.6
XS Rating Curve= 0 ,0
Exp/Cntr=0.3,0.1

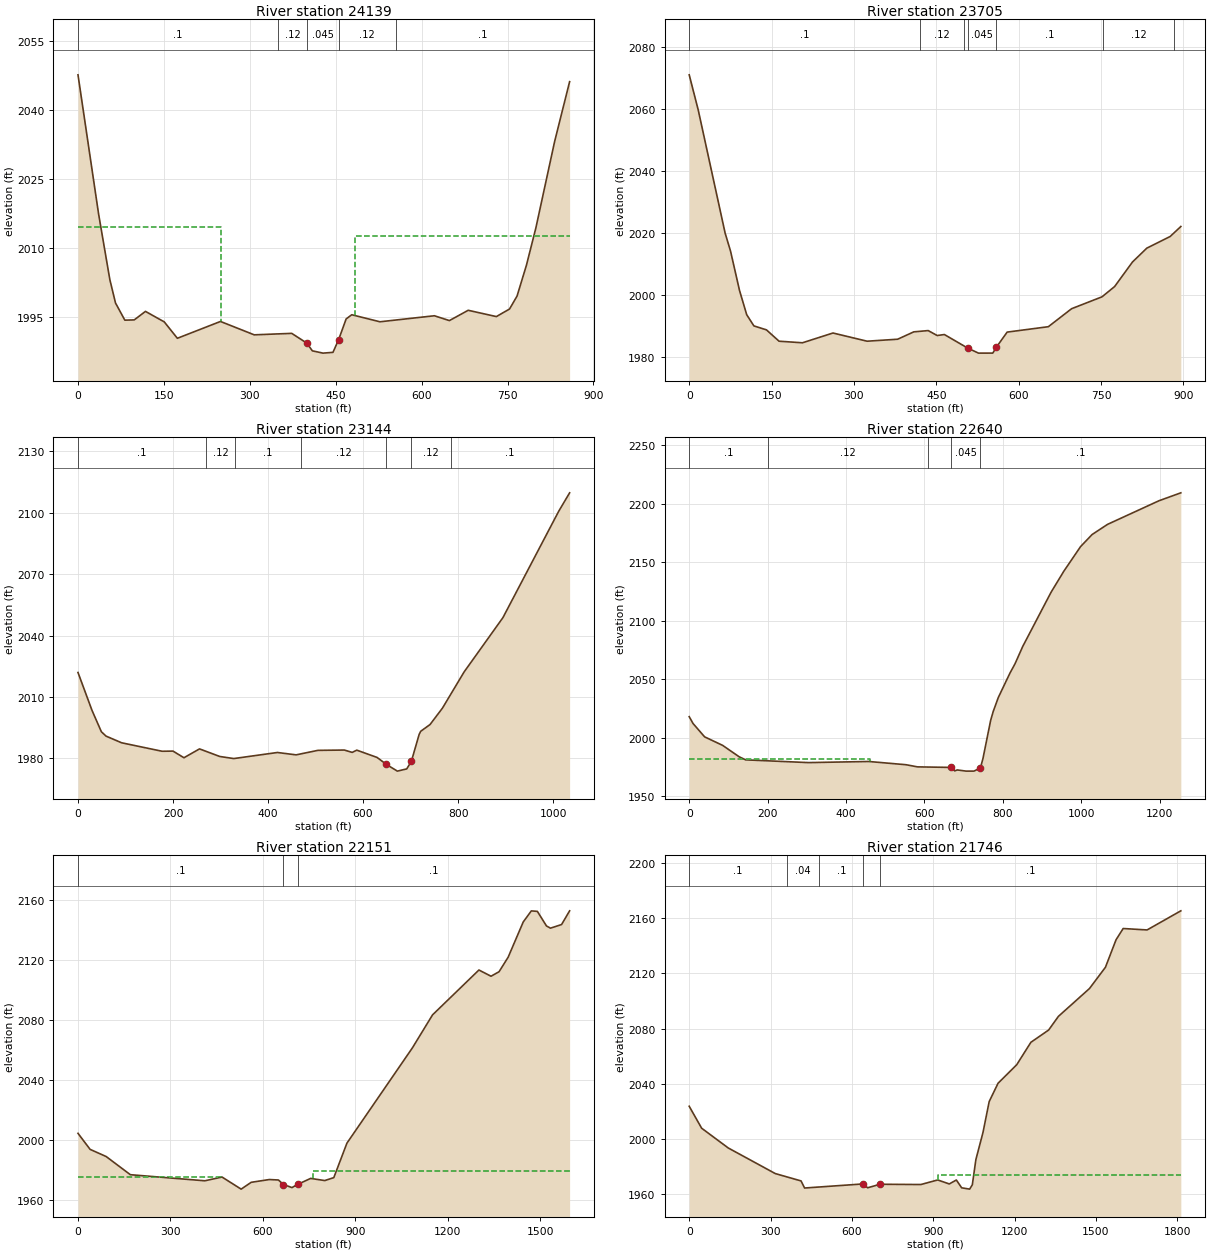
Type RM Length L Ch R = 1 ,24139   ,430.6,433.5,431.8
XS GIS Cut Line= 3
     2130813.777      235491.983      2131154.63      235221.087
      2131472.85      234942.395
#Sta/Elev= 30
       0 2047.61      36 2017.31    55.6 2003.06    65.5 1997.97    81.8 1994.23
    98.2 1994.29   117.8 1996.14   150.6 1993.86   173.5 1990.29   248.8 1993.95
   307.7 1991.04   373.2 1991.36   399.4 1989.25   409.2 1987.56   427.9 1987.06
   445.2 1987.23   455.1    1990   468.2  1994.5     478 1995.41   527.2 1993.88
   622.3 1995.19   648.5 1994.14   681.3 1996.38   730.5 1995.01   753.5 1996.66
   766.6 1999.47     783 2006.19   799.4 2014.26   832.2 2033.09   858.4 2046.12
#Mann= 5 ,-1 , 0
       0      .1       0     350     .12       0   399.4    .045       0
   455.1     .12       0  555.39      .1       0
#XS Ineff= 2 , 0
          249.68 2014.55  483.84         2012.52
Permanent Ineff=
       F       F
Bank Sta=399.4,455.1
XS Rating Curve= 0 ,0
Exp/Cntr=0.3,0.1

Type RM Length L Ch R = 1 ,23705   ,535.9,561.3,582.5
XS GIS Cut Line= 3
     2130988.256      235885.212     2131403.371      235566.126
     2131688.777       235327.92
#Sta/Elev= 30
       0 2070.88    16.4 2059.58    65.4 2019.91    75.3 2014.08    91.6 2001.44
   104.7 1993.62   117.8 1990.01   140.7 1988.73   163.6 1985.08   206.2 1984.57
   261.8 1987.72     324 1985.08   379.6 1985.72     409 1988.09   435.2  1988.5
   451.6 1986.91   464.7 1987.23   507.2 1982.86   526.8 1981.24   552.9 1981.25
   559.4 1983.15     579 1988.01     654 1989.75   696.4 1995.55   751.8 1999.38
   774.7 2002.68   807.3  2010.6   833.4 2015.06   875.8  2018.8   895.3 2022.02
#Mann= 7 ,-1 , 0
       0      .1       0     420     .12       0     500      .1       0
   507.2    .045       0   559.4      .1       0  753.58     .12       0
  883.58      .1       0
Bank Sta=507.2,559.4
XS Rating Curve= 0 ,0
Exp/Cntr=0.3,0.1

Type RM Length L Ch R = 1 ,23144   ,494.4,504.4,515.7
XS GIS Cut Line= 3
     2131016.902      236033.649     2131751.277      236020.629
     2132046.839      236073.622
#Sta/Elev= 30
       0 2021.95    29.5 2003.43    49.2 1992.99      59 1990.86    91.8 1987.59
   177.1 1983.45     200 1983.53     223 1980.28   255.8 1984.61   298.4  1980.9
   327.9 1979.88   419.7 1982.85   459.1 1981.69     505 1983.89   560.7 1984.04
   577.1  1982.9   586.9 1983.99   629.6 1980.42   649.2 1977.01   672.2 1973.74
   691.9 1974.83   701.7 1978.52   718.1  1991.7   721.4 1993.22     741 1996.51
   767.1 2004.52   812.8 2022.25   894.4 2048.75  1011.9 2100.78  1034.8 2109.76
#Mann= 7 ,-1 , 0
       0      .1       0     270     .12       0     330      .1       0
     470     .12       0   649.2    .045       0   701.7     .12       0
  784.49      .1       0
Bank Sta=649.2,701.7
XS Rating Curve= 0 ,0
Exp/Cntr=0.3,0.1

Type RM Length L Ch R = 1 ,22640   ,477.4,488.1,491.8
XS GIS Cut Line= 3
     2130894.506      236322.712     2131647.763      236532.238
     2132116.513      236476.683
#Sta/Elev= 30
       0 2017.96     9.8  2012.1    39.3 2000.69    85.1 1993.44   127.6 1983.62
   143.9 1981.02   304.2 1978.67     458 1979.62   552.9 1976.86   582.3 1975.02
   667.4 1974.55   677.2 1971.59   683.7 1972.38   706.6 1971.38   726.2  1971.4
   742.6 1974.02   749.1 1981.95   768.8 2014.74   775.3 2022.31   788.4 2034.38
   817.9  2055.1     831 2063.19   850.7 2078.03   922.8 2124.29   955.6 2142.41
   998.2 2163.41  1027.7 2173.75    1067 2182.42  1198.2 2202.62  1253.9 2209.39
#Mann= 5 ,-1 , 0
       0      .1       0     200     .12       0     610      .1       0
   667.4    .045       0   742.6      .1       0
#XS Ineff= 2 , 0
          460.77 1982.04
Permanent Ineff=
       F       F
Bank Sta=667.4,742.6
XS Rating Curve= 0 ,0
Exp/Cntr=0.3,0.1

Type RM Length L Ch R = 1 ,22151   ,402.4,405,406.1
XS GIS Cut Line= 3
     2130774.715      236658.649     2131553.361      237031.045
     2132168.597      236632.933
#Sta/Elev= 30
       0  2004.3    39.2 1993.63    91.5 1988.83     170 1976.73   411.9 1972.67
   467.5 1975.18   529.6 1967.12   562.3 1971.66   621.2 1973.51   650.6  1973.2
     667  1970.2   694.5 1968.15   712.7 1970.23   755.2 1974.27     801 1972.82
   830.4 1974.78   872.9 1997.72  1085.6 2061.26    1151 2083.24  1301.5 2113.11
  1340.8 2108.97  1366.9 2111.97  1396.4 2121.65  1445.4 2145.14  1471.6  2152.5
  1491.2 2152.18  1520.7 2142.48  1533.8 2140.99  1569.8 2143.41  1595.9 2152.54
#Mann= 3 ,-1 , 0
       0      .1       0     667    .045       0   712.7      .1       0
#XS Ineff= 2 , 0
          466.78 1975.28  764.01         1978.91
Permanent Ineff=
       F       F
Bank Sta=667,712.7
XS Rating Curve= 0 ,0
Exp/Cntr=0.3,0.1

Type RM Length L Ch R = 1 ,21746   ,436.1,424.7,400.9
XS GIS Cut Line= 3
     2130579.402      236929.483     2131488.256      237476.358
     2132238.041      237542.655
#Sta/Elev= 30
       0 2023.73    45.8 2007.84     144 1993.51   317.6 1974.95   412.5 1969.64
   425.6 1964.49   641.7 1967.46     658 1964.65   703.9 1967.22   854.4 1967.02
   916.7 1970.34   959.2 1967.45   985.4 1970.29    1005 1964.64  1034.5 1963.69
  1044.3 1966.83  1057.4 1985.09  1083.6 2004.72  1106.5 2027.12  1139.2 2040.41
    1208 2053.81  1260.3 2070.07  1325.8 2078.96  1361.8 2088.85  1476.3 2109.01
  1535.2  2124.4  1574.5 2144.39  1600.7 2152.51    1689 2151.48  1813.4 2165.33
#Mann= 5 ,-1 , 0
       0      .1       0     360     .04       0     480      .1       0
   641.7    .045       0   703.9      .1       0
#XS Ineff= 2 , 0
                          917.33         1974.06
Permanent Ineff=
       F       F
Bank Sta=641.7,703.9
XS Rating Curve= 0 ,0
Exp/Cntr=0.3,0.1