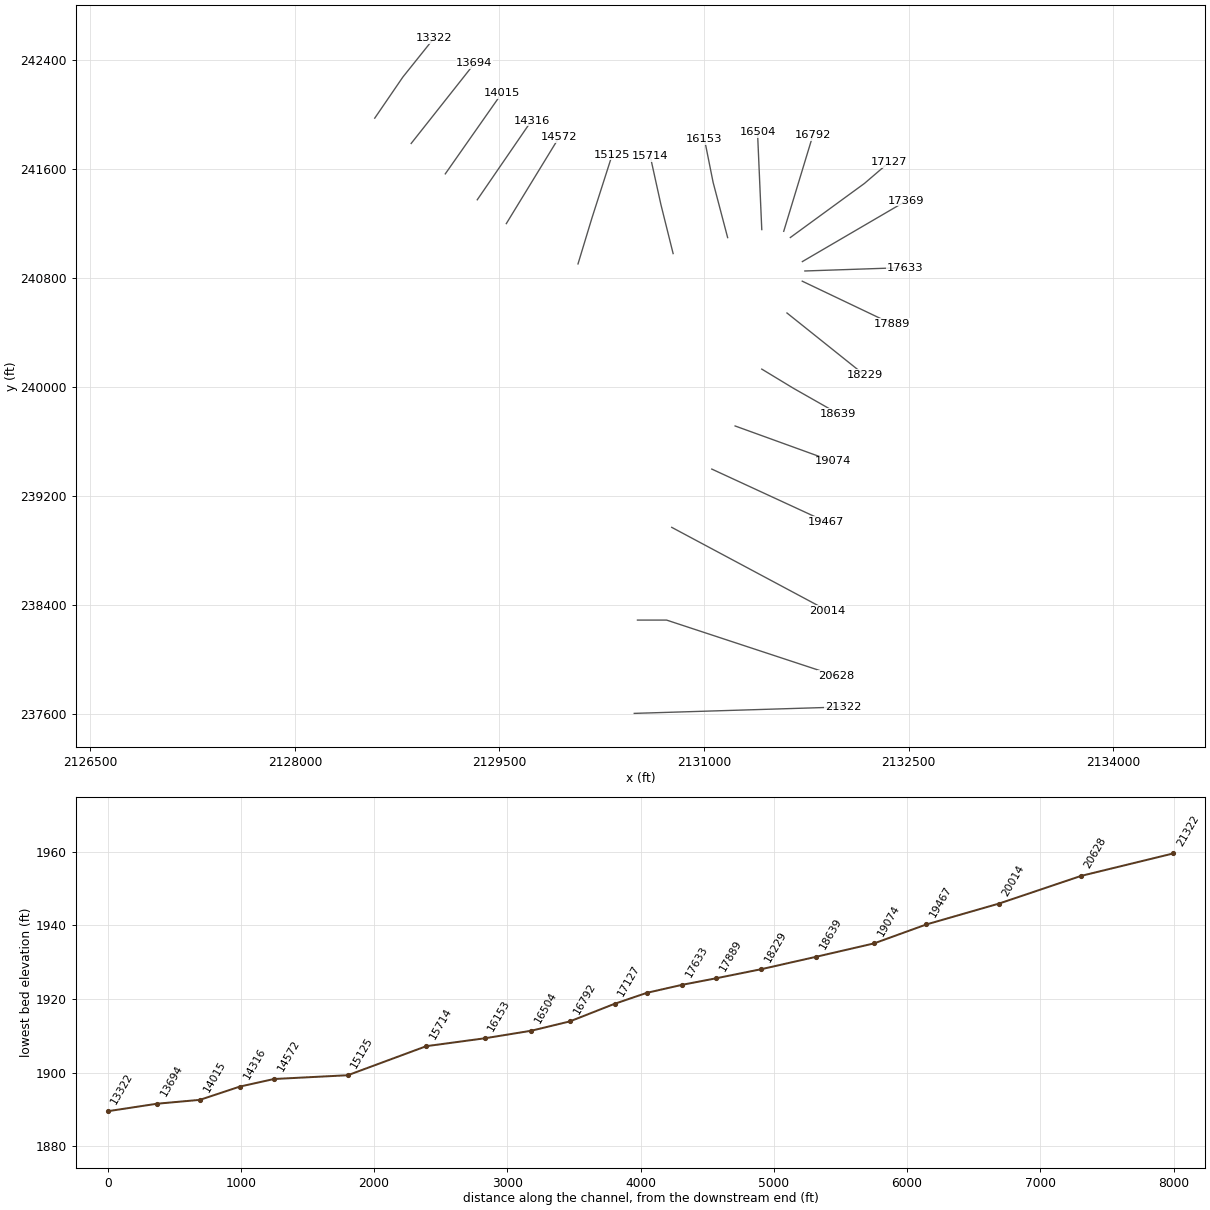
HEC-RAS study SECONDCK.prj: SECONDCK

--- SECONDCK.g01 (geometry) --- (continued)

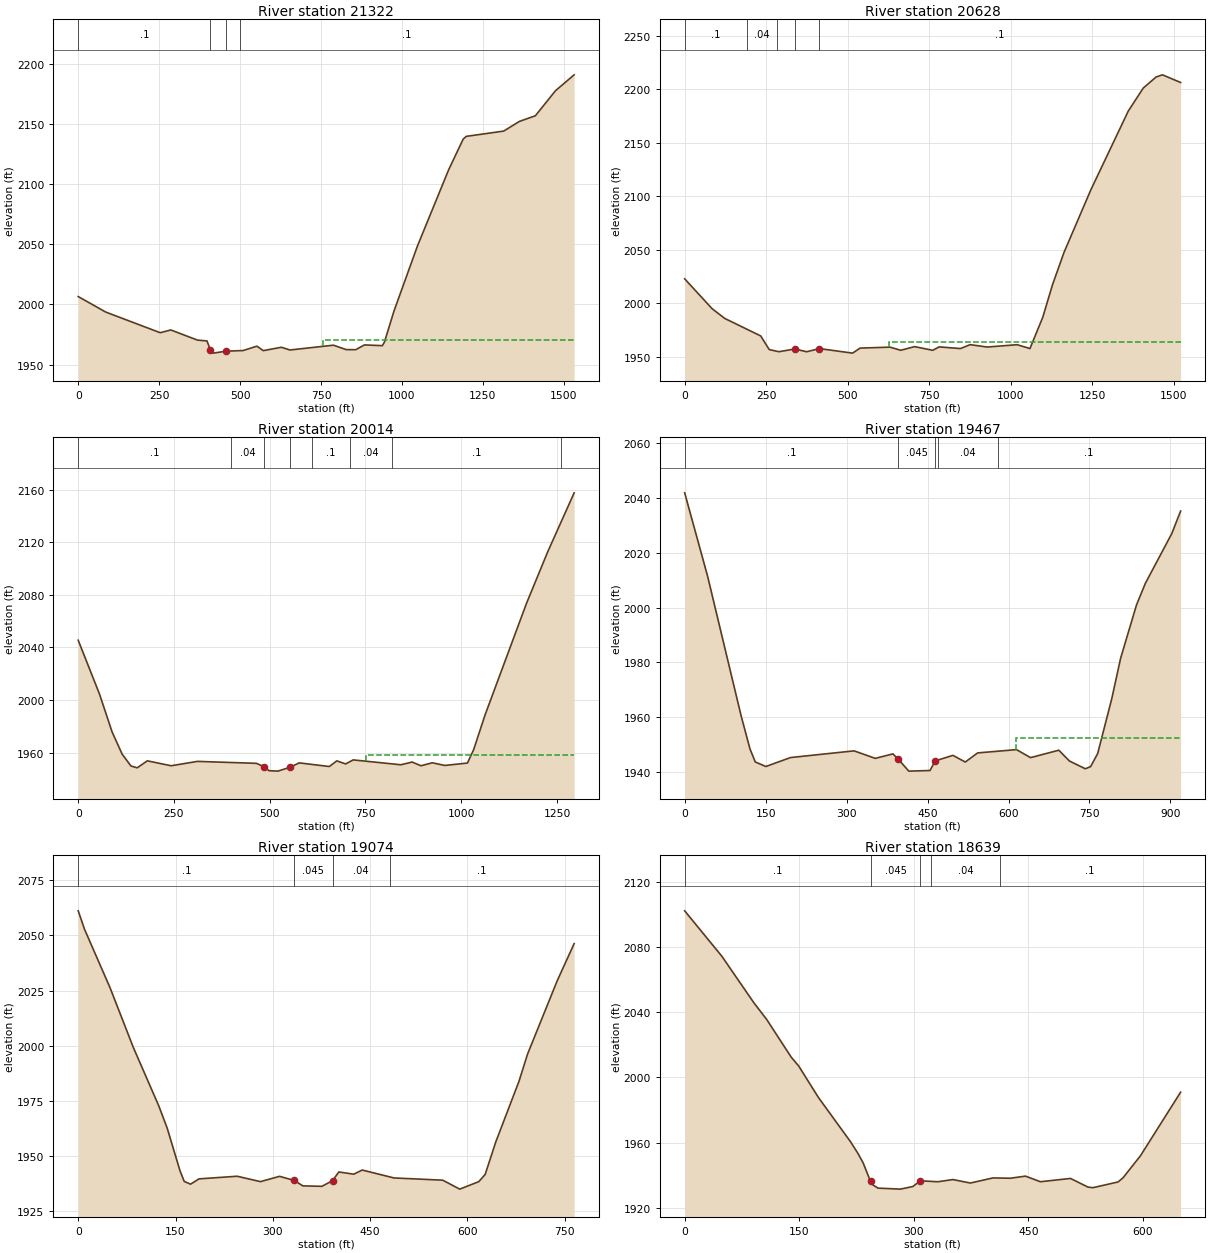
Type RM Length L Ch R = 1 ,21322   ,708.6,693.7,669.5
XS GIS Cut Line= 2
     2130488.256237604.450926843     2132019.291237651.650926843
#Sta/Elev= 30
       0 2006.57    84.9  1993.7   253.3 1976.51   286.1 1978.81   368.2 1970.38
   397.7 1969.67   408.4 1962.13   417.4 1959.55   456.8 1961.17   509.3  1961.7
     552 1965.32   571.7 1961.62   627.5 1964.43   653.7 1962.15   788.3 1966.14
   827.7 1962.47   857.2 1962.41   884.2 1966.38   939.3 1965.76   945.9 1968.75
   975.6 1994.73  1047.6 2048.45  1143.9 2111.78    1189 2137.41  1198.6 2139.72
  1314.3 2144.11  1362.7 2152.16    1412 2156.83  1474.3  2177.7  1531.8 2190.87
#Mann= 4 ,-1 , 0
       0      .1       0   408.4    .045       0   456.8     .04       0
     500      .1       0
#XS Ineff= 2 , 0
                          755.35          1970.6
Permanent Ineff=
       F       F
Bank Sta=408.4,456.8
XS Rating Curve= 0 ,0
Exp/Cntr=0.3,0.1

Type RM Length L Ch R = 1 ,20628   ,613.4,614,593.8
XS GIS Cut Line= 3
     2130511.694      238288.858     2130725.236      238288.858
     2131967.208       237879.46
#Sta/Elev= 30
       0 2022.81    84.1 1994.94     123 1985.82   233.2  1969.5   259.4 1956.74
   288.9 1954.77   338.1 1957.29   374.1 1954.73   413.5 1957.66   515.1 1953.44
     538 1958.14   629.8 1959.03   662.6  1956.1   705.2 1959.51   760.9 1956.07
   780.5 1959.27   846.1 1957.71   875.6 1961.35     928 1959.13  1019.8  1961.3
  1059.1 1957.72  1098.5    1987    1128 2017.09    1164 2047.84  1245.9 2105.96
  1360.6 2179.42  1406.5 2200.89  1445.9 2211.25  1465.5  2213.3  1521.2 2206.15
#Mann= 5 ,-1 , 0
       0      .1       0     190     .04       0  283.54      .1       0
   338.1    .045       0   413.5      .1       0
#XS Ineff= 2 , 0
                          626.24         1963.87
Permanent Ineff=
       F       F
Bank Sta=338.1,413.5
XS Rating Curve= 0 ,0
Exp/Cntr=0.3,0.1

Type RM Length L Ch R = 1 ,20014   ,543.6,547.3,548.4
XS GIS Cut Line= 2
     2130762.914      238969.141     2131904.708      238358.627
#Sta/Elev= 30
       0  2045.5    55.7 2004.47    88.5 1975.73   114.7 1958.89   137.7 1949.86
   154.1 1948.46   180.3 1953.78   242.6 1950.04   311.4 1953.36   465.5 1951.87
   485.1  1949.3   498.2  1946.3   521.2 1945.95     554 1948.96   576.9 1952.23
   655.6 1949.46   675.2 1953.75   698.2 1951.42   717.9 1954.49   842.4 1950.78
   871.9 1952.86   894.9 1950.02   924.4  1952.3   957.1 1950.27  1016.2  1952.1
  1032.5 1962.36    1062 1988.51  1170.2 2073.41  1225.9 2112.83  1294.8 2157.62
#Mann= 8 ,-1 , 0
       0      .1       0     400     .04       0   485.1    .045       0
     554     .04       0     610      .1       0     710     .04       0
     820      .1       0    1260     .12       0
#XS Ineff= 2 , 0
                          750.11            1958
Permanent Ineff=
       F       F
Bank Sta=485.1,554
XS Rating Curve= 0 ,0
Exp/Cntr=0.3,0.1

Type RM Length L Ch R = 1 ,19467   ,389.3,392.3,397.3
XS GIS Cut Line= 2
     2131056.606      239396.667     2131890.819      239011.405
#Sta/Elev= 30
       0 2041.89    42.5 2011.42   104.6 1960.44     121 1948.37   130.8 1943.61
   150.4 1941.95   196.2 1945.22   313.9 1947.66   353.2 1944.92   385.9 1946.56
   395.7 1944.61   415.3 1940.26   454.5 1940.48   464.3    1944     497 1946.02
   519.9 1943.58   542.8 1946.91   614.8 1948.11   640.9 1945.19   693.2  1947.9
   712.9 1943.96   742.3 1941.12   752.1  1941.9   765.2 1946.67   791.4 1966.76
   807.7 1981.46   837.1 2000.91   853.5 2008.81   902.5    2027   918.9 2035.23
#Mann= 5 ,-1 , 0
       0      .1       0   395.7    .045       0   464.3      .1       0
     470     .04       0     580      .1       0
#XS Ineff= 2 , 0
                          614.47         1952.31
Permanent Ineff=
       F       F
Bank Sta=395.7,464.3
XS Rating Curve= 0 ,0
Exp/Cntr=0.3,0.1

Type RM Length L Ch R = 1 ,19074   ,437.2,435.7,424
XS GIS Cut Line= 2
     2131227.624      239712.794     2131946.374      239452.377
#Sta/Elev= 30
       0 2061.06     9.8 2052.67      49 2026.32    84.9 1999.28   124.2  1972.8
   137.2  1962.7   156.8 1943.53   163.4 1938.61   173.2 1937.36   186.2 1939.76
     245 1940.95     281 1938.51   310.4 1940.91   333.2 1939.03   346.3 1936.59
   375.7 1936.39     392 1938.95   401.8 1942.88   424.7 1941.88   437.8 1943.76
   486.8 1940.18   561.9 1939.17   588.1 1935.12   617.5  1938.5   627.3 1941.75
   643.6  1956.4   679.5 1983.94   692.6 1996.17   738.3 2029.35   764.5 2046.22
#Mann= 4 ,-1 , 0
       0      .1       0   333.2    .045       0     392     .04       0
     480      .1       0
Bank Sta=333.2,392
XS Rating Curve= 0 ,0
Exp/Cntr=0.3,0.1

Type RM Length L Ch R = 1 ,18639   ,413.3,409.7,400.5
XS GIS Cut Line= 3
     2131423.152      240130.004     2131656.184      239988.698
     2131983.763      239802.587
#Sta/Elev= 30
       0 2102.28    48.7 2074.39    90.8  2045.7   107.1  2035.8   139.5 2012.47
   149.2 2007.09   175.2 1987.67   217.4 1960.39   227.1 1953.19   233.6 1947.65
   243.3 1936.24   246.6 1934.02   253.1  1932.1   282.4 1931.48   298.7 1933.08
   308.6 1936.58   331.5 1936.01   351.2 1937.35   374.1 1935.22   403.6 1938.36
   426.5 1938.17   446.2 1939.46   465.8 1936.02   505.1 1938.04   528.1 1932.71
   534.6 1932.37   567.4 1935.88   573.9 1938.42   596.9 1952.08   649.3 1990.98
#Mann= 5 ,-1 , 0
       0      .1       0   243.3    .045       0   308.6      .1       0
  322.53     .04       0  412.53      .1       0
Bank Sta=243.3,308.6
XS Rating Curve= 0 ,0
Exp/Cntr=0.3,0.1

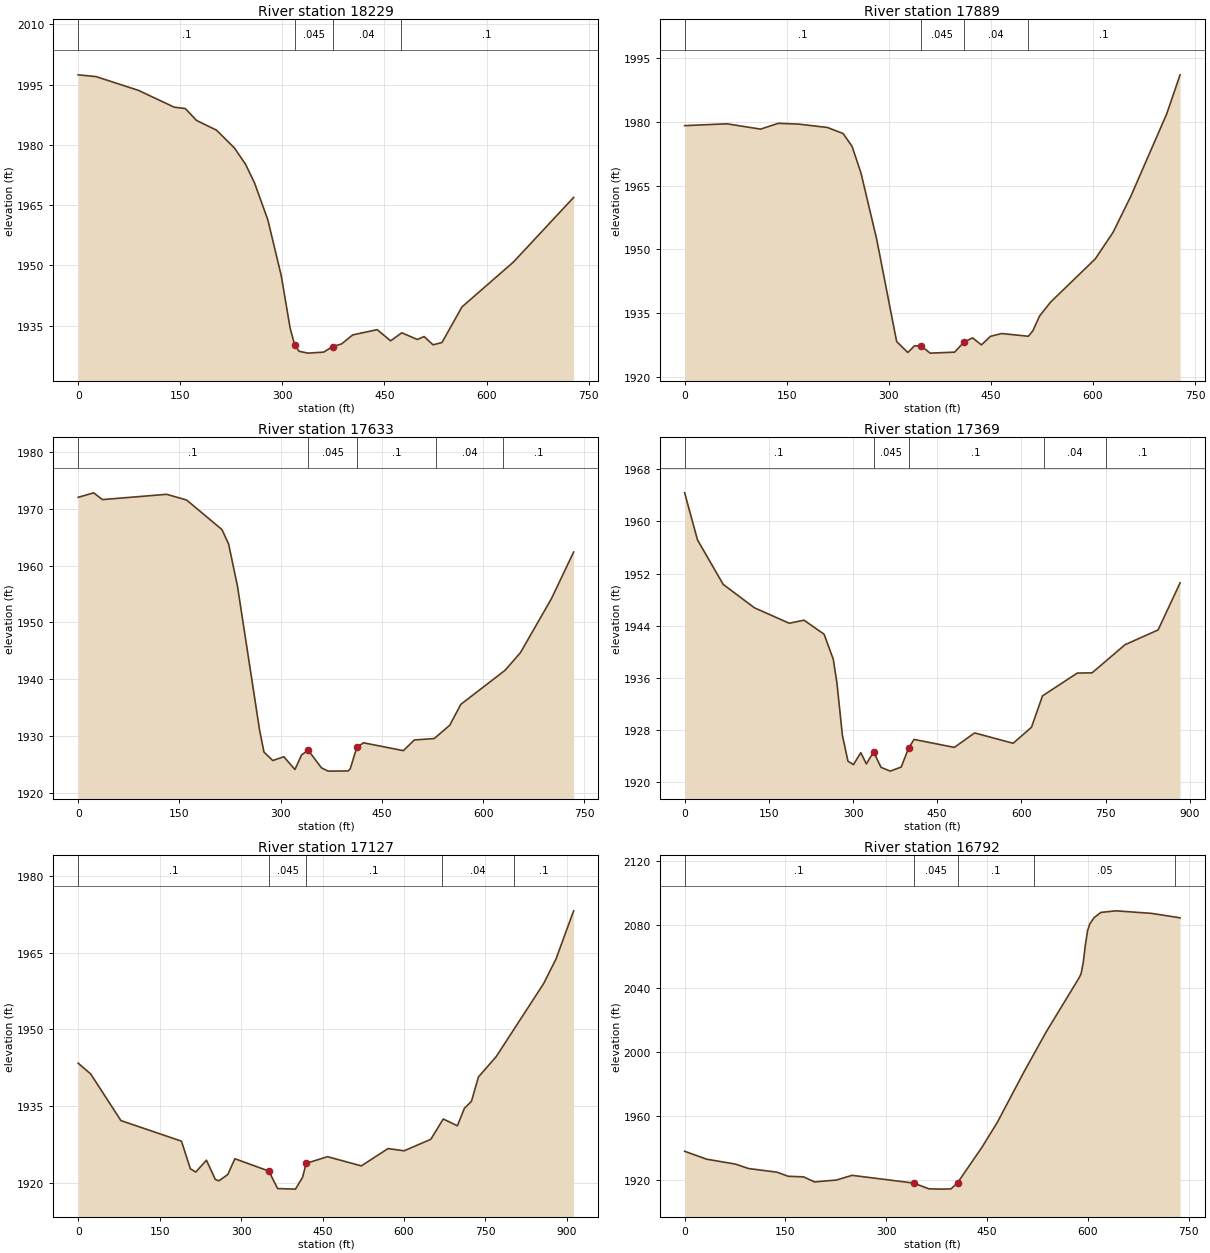
Type RM Length L Ch R = 1 ,18229   ,333.7,340.3,351.6
XS GIS Cut Line= 3
     2131607.897      240541.652     2131892.134      240314.264
      2132176.37      240086.875
#Sta/Elev= 30
       0 1997.45    26.2 1997.01    88.5 1993.58     141  1989.4   157.4 1989.05
   173.8  1986.1   203.3 1983.66   229.6 1979.23     246 1975.15   259.1 1970.55
   278.7 1961.31   298.4 1947.41   311.5 1934.31   318.1 1930.17   324.6 1928.58
   337.8 1928.13   360.7 1928.38   373.8 1929.76     387 1930.42   403.4 1932.67
   439.4 1933.98   459.1 1931.19   475.5  1933.2   498.4 1931.53   508.3 1932.26
   521.4  1930.2   534.5 1930.77     564 1939.65   639.5 1950.81     728 1966.91
#Mann= 4 ,-1 , 0
       0      .1       0   318.1    .045       0   373.8     .04       0
     474      .1       0
Bank Sta=318.1,373.8
XS Rating Curve= 0 ,0
Exp/Cntr=0.3,0.1

Type RM Length L Ch R = 1 ,17889   ,238.4,256.1,279.8
XS GIS Cut Line= 3
     2131719.919      240774.988     2132048.467      240618.296
     2132377.015      240461.605
#Sta/Elev= 30
       0 1979.06    62.3 1979.49   111.5 1978.24   137.7 1979.61   167.2 1979.42
   209.9 1978.62   232.8 1977.21     246  1974.2   259.1 1967.93     282 1952.53
   311.5 1928.37   327.9  1925.8   337.8 1927.37   347.6 1927.31   360.7 1925.65
   396.8 1925.88   409.9 1928.18     423 1929.23   436.1 1927.59   449.3 1929.59
   465.7 1930.25     505 1929.61   511.6 1930.88   521.4 1934.34   537.8 1937.64
   603.4 1947.78   629.6 1954.03   655.9 1962.58   708.3  1981.8     728 1990.99
#Mann= 4 ,-1 , 0
       0      .1       0   347.6    .045       0   409.9     .04       0
     504      .1       0
Bank Sta=347.6,409.9
XS Rating Curve= 0 ,0
Exp/Cntr=0.3,0.1

Type RM Length L Ch R = 1 ,17633   ,242.8,263.9,285.8
XS GIS Cut Line= 2
     2131739.096      240849.821     2132472.631      240874.795
#Sta/Elev= 30
       0    1972    22.9 1972.79      36  1971.6   131.1 1972.53   160.6 1971.53
     213 1966.33   222.8 1963.82   235.9 1956.45   268.7 1931.12   275.2 1927.23
   288.3 1925.73   304.7  1926.4   321.1 1924.15   330.9 1926.71   340.8 1927.54
   360.4 1924.45   370.3 1923.87   399.8  1923.9     403 1924.27   412.8 1928.05
   422.7 1928.85   481.7 1927.47     498 1929.35   527.5  1929.6   550.5 1931.94
   566.8  1935.6   632.4 1941.59   655.3 1944.71   701.2  1954.2     734 1962.38
#Mann= 5 ,-1 , 0
       0      .1       0   340.8    .045       0   412.8      .1       0
     530     .04       0     630      .1       0
Bank Sta=340.8,412.8
XS Rating Curve= 0 ,0
Exp/Cntr=0.3,0.1

Type RM Length L Ch R = 1 ,17369   ,234.4,241.9,244.5
XS GIS Cut Line= 2
     2131720.793      240918.784     2132483.048      241364.379
#Sta/Elev= 30
       0 1964.38    22.9 1957.16    68.7 1950.34   124.3 1946.75   186.4 1944.38
   212.6 1944.85   248.5  1942.7   264.9 1938.85   271.4  1935.2   281.2 1927.16
     291 1923.23   300.8  1922.7   313.9 1924.53   323.8 1922.81   336.8 1924.66
   349.9 1922.28   366.3  1921.7   385.9 1922.33     399 1925.21   408.8 1926.56
   480.7 1925.34   516.7 1927.56   585.4 1925.97   618.1 1928.43   637.7 1933.24
   699.8 1936.74     726 1936.77   784.8 1941.09   843.7 1943.35   882.9 1950.57
#Mann= 5 ,-1 , 0
       0      .1       0   336.8    .045       0     399      .1       0
     640     .04       0     750      .1       0
Bank Sta=336.8,399
XS Rating Curve= 0 ,0
Exp/Cntr=0.3,0.1

Type RM Length L Ch R = 1 ,17127   ,302.6,334.8,357.2
XS GIS Cut Line= 3
     2131632.683      241095.463     2132175.756      241491.983
     2132358.048      241648.233
#Sta/Elev= 30
       0 1943.37      23 1941.27    78.7 1932.14   190.2 1928.11   206.6 1922.71
   216.5 1922.06   236.2 1924.38   252.6 1920.61   259.1 1920.34   275.5 1921.58
   288.6 1924.67     351 1922.26   367.4 1918.83   400.2 1918.72   413.3 1921.05
   419.9 1923.76   459.2 1925.07   521.5 1923.27   570.7 1926.66   600.3 1926.22
   649.5 1928.48   672.4 1932.45   698.4 1931.12   711.4 1934.55   724.3 1935.91
   737.3  1940.7   769.8 1944.64   857.4 1958.98   880.1 1963.79   912.5  1973.2
#Mann= 5 ,-1 , 0
       0      .1       0     351    .045       0   419.9      .1       0
     670     .04       0  802.43      .1       0
Bank Sta=351,419.9
XS Rating Curve= 0 ,0
Exp/Cntr=0.3,0.1

Type RM Length L Ch R = 1 ,16792   ,271.8,288.5,302.3
XS GIS Cut Line= 2
     2131584.092      241140.812     2131798.152      241846.149
#Sta/Elev= 30
       0 1937.72    32.8 1932.75    75.4 1929.69      95  1926.9   137.6 1924.57
     154 1922.02   176.9 1921.66   193.3 1918.49     226 1919.68     249 1922.61
   340.7 1917.77   363.6 1914.12   383.2 1913.96   396.4 1914.14   406.2 1918.05
   442.3  1940.2   465.2 1955.89   504.5 1987.29   537.3 2012.23   586.4 2046.29
   589.7    2049     593  2056.1   596.2 2067.38   599.5 2076.25   602.8 2080.47
   609.3 2084.43   619.2 2087.67   642.1 2088.66   694.5 2087.06   737.1 2084.27
#Mann= 5 ,-1 , 0
       0      .1       0   340.7    .045       0   406.2      .1       0
     520     .05       0     730    .035       0
Bank Sta=340.7,406.2
XS Rating Curve= 0 ,0
Exp/Cntr=0.3,0.1

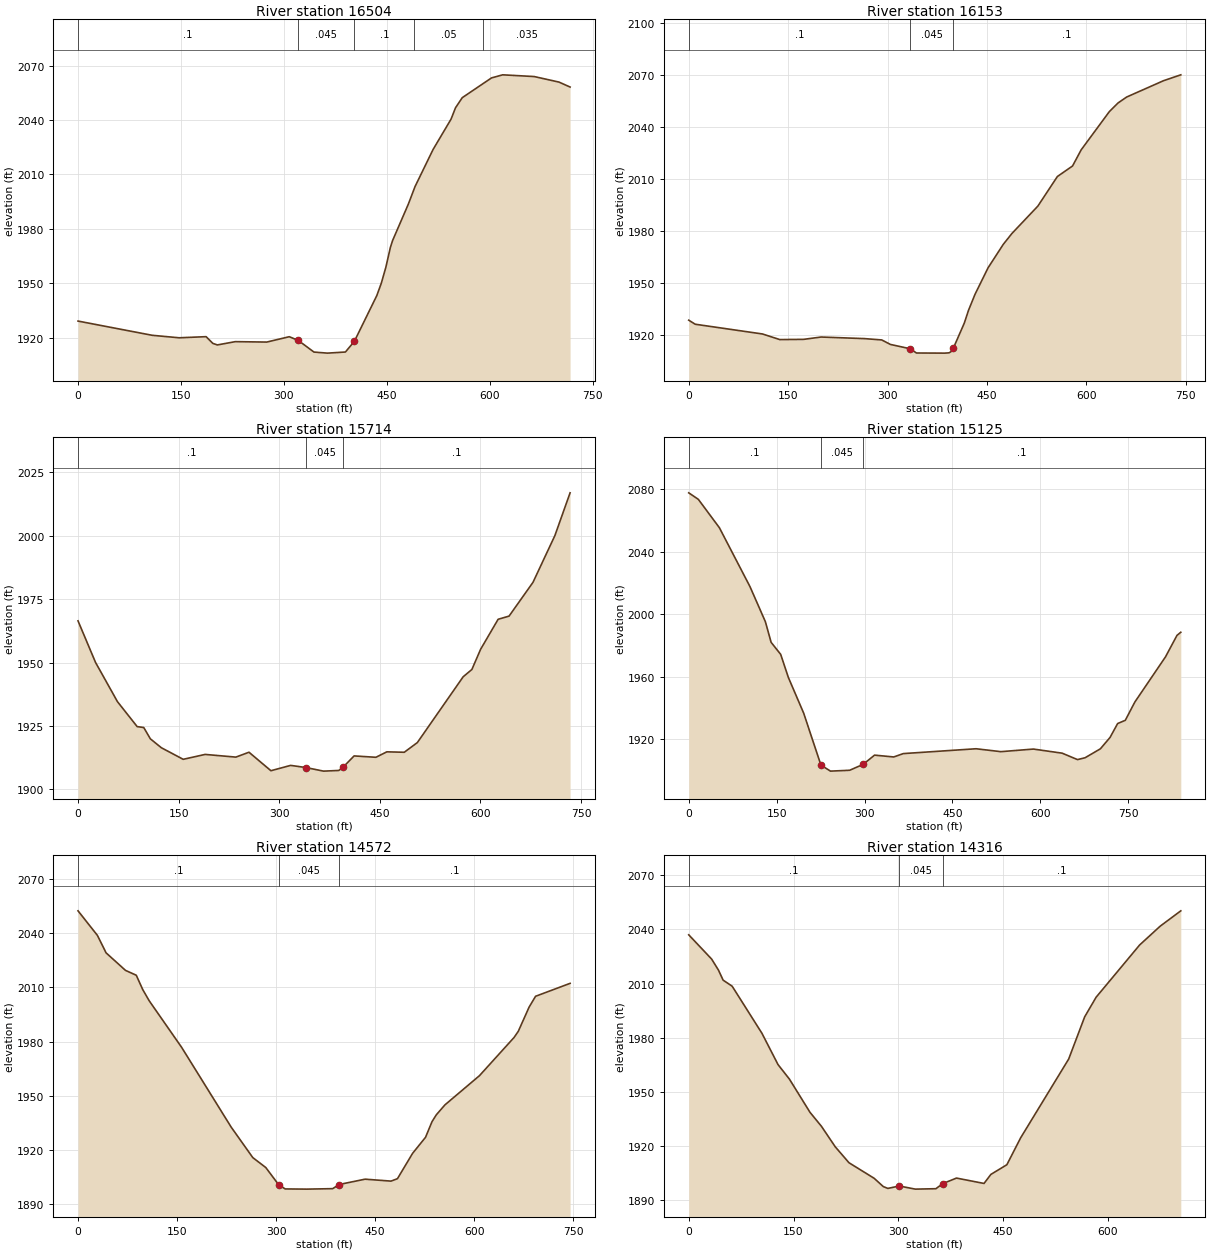
Type RM Length L Ch R = 1 ,16504   ,331.6,350.3,356.9
XS GIS Cut Line= 2
     2131423.152      241153.441     2131391.902      241869.587
#Sta/Elev= 30
       0 1929.11     108 1921.27   147.3 1919.89   186.6 1920.51   196.4  1916.8
   202.9 1915.95   229.1 1917.76     275 1917.53   307.7 1920.48   320.8 1918.45
   343.7 1912.01   363.3 1911.43   389.5 1912.04   402.6 1917.96   435.3 1943.22
   441.9 1950.11   448.4 1958.76     455 1969.71   458.2 1973.49   481.2 1993.64
     491 2003.36   517.2 2023.75   543.4 2040.49   549.9 2046.77   559.7 2052.33
   602.3 2063.23   618.6 2064.94   664.5 2063.99   700.5 2060.95   716.8 2058.21
#Mann= 5 ,-1 , 0
       0      .1       0   320.8    .045       0   402.6      .1       0
     490     .05       0     590    .035       0
Bank Sta=320.8,402.6
XS Rating Curve= 0 ,0
Exp/Cntr=0.3,0.1

Type RM Length L Ch R = 1 ,16153   ,425.3,439.1,428.3
XS GIS Cut Line= 3
     2131172.884      241094.702     2131066.381      241499.795
     2131002.901      241816.962
#Sta/Elev= 30
       0 1928.39     9.8 1926.05   111.3 1920.42   137.4 1917.19   173.4 1917.32
   199.6 1918.66   265.1 1917.75   291.2 1916.98   304.3 1914.38   333.8 1911.92
   343.6 1909.44   386.1 1909.37   392.7 1909.54     396 1910.29   399.2 1912.27
   415.6 1926.62   422.1 1934.13   431.9 1943.35   451.5 1958.59   474.4 1972.11
   487.5 1978.42   526.7 1994.25   556.1 2011.31     579  2017.4     592 2026.71
   634.5 2048.78   647.6 2053.76   660.6 2057.19   716.2 2066.61   742.3 2070.01
#Mann= 3 ,-1 , 0
       0      .1       0   333.8    .045       0   399.2      .1       0
Bank Sta=333.8,399.2
XS Rating Curve= 0 ,0
Exp/Cntr=0.3,0.1

Type RM Length L Ch R = 1 ,15714   ,603.1,589.5,552.5
XS GIS Cut Line= 3
     2130773.198      240977.543     2130683.928      241335.848
     2130605.465      241691.685
#Sta/Elev= 30
       0 1966.41    26.1 1950.05    58.8 1934.59    88.2 1924.76      98  1924.4
   107.8 1919.97   124.2 1916.45   156.8 1911.88   189.5 1913.81   235.3 1912.75
   254.9 1914.67   287.6 1907.39     317 1909.49   339.8 1908.64     366 1907.23
   388.8 1907.49   395.3 1908.82   411.6 1913.22   444.1 1912.68   460.4 1914.83
   486.4 1914.66   505.9 1918.48   574.2 1944.39   587.2 1947.27   600.2 1955.22
   626.3 1967.03   642.6 1968.28   678.3 1981.59   710.9 1999.98   733.6 2016.84
#Mann= 3 ,-1 , 0
       0      .1       0   339.8    .045       0   395.3      .1       0
Bank Sta=339.8,395.3
XS Rating Curve= 0 ,0
Exp/Cntr=0.3,0.1

Type RM Length L Ch R = 1 ,15125   ,553.1,553,532.7
XS GIS Cut Line= 3
     2130075.802      240901.643     2130177.355      241236.418
     2130326.798       241702.92
#Sta/Elev= 30
       0 2077.75    16.4 2073.57    52.3 2055.39   104.6 2017.56   130.8 1995.12
   140.6  1981.9   156.9 1974.21     170  1959.4   196.2 1936.45   225.6 1903.19
   241.9 1899.34   274.6 1899.89   297.5 1903.65   317.1 1909.59   349.8 1908.42
   366.2 1910.58   490.3 1913.68   532.7 1911.82   588.2 1913.48   637.2 1910.85
   663.4 1906.73   676.4 1907.92   702.5 1913.66   718.9 1920.92   731.9 1929.84
     745 1931.93   761.3 1943.66   813.6 1972.61   833.2 1986.38   839.7 1988.37
#Mann= 3 ,-1 , 0
       0      .1       0   225.6    .045       0   297.5      .1       0
Bank Sta=225.6,297.5
XS Rating Curve= 0 ,0
Exp/Cntr=0.3,0.1

Type RM Length L Ch R = 1 ,14572   ,260.2,255.8,253.8
XS GIS Cut Line= 2
     2129550.209      241197.325     2129938.777      241833.129
#Sta/Elev= 30
       0 2052.34    29.4 2038.73    42.5 2029.08    71.9 2019.38    88.2  2016.7
      98 2008.77   107.8 2002.55   156.9 1976.78     232 1932.59   264.7 1915.75
   284.3 1910.28   303.9 1900.73   313.7 1898.43   346.4 1898.32   385.6 1898.58
   395.4 1900.87   434.7 1903.83   473.9 1902.75   483.7  1904.1   506.6 1918.12
   526.2    1927     536 1935.64   542.5 1939.43   555.6 1944.95   607.9 1961.12
   660.2 1982.22   666.7 1985.68     683 1999.02   692.8 2005.04   745.1  2012.2
#Mann= 3 ,-1 , 0
       0      .1       0   303.9    .045       0   395.4      .1       0
Bank Sta=303.9,395.4
XS Rating Curve= 0 ,0
Exp/Cntr=0.3,0.1

Type RM Length L Ch R = 1 ,14316   ,302.8,301.2,302.4
XS GIS Cut Line= 2
     2129337.215      241372.191     2129735.547      241953.179
#Sta/Elev= 30
       0 2036.94    32.8 2023.51    42.6 2017.39    49.2 2011.88    62.2  2008.5
   104.8 1982.47   127.8 1965.17   144.2 1957.09   173.6 1938.75     190    1931
   209.7  1919.7   229.4 1910.86   265.4 1902.27   278.5 1897.68     285 1896.67
   301.4 1897.99   324.4 1896.27   353.8  1896.5   363.7 1899.33   383.3 1902.38
   422.7 1899.41   432.5  1904.4   455.4 1909.77   475.1 1924.62   543.9 1968.23
   566.8 1991.58   583.2 2002.44   645.4 2031.29   674.9 2041.73   704.4 2050.21
#Mann= 3 ,-1 , 0
       0      .1       0   301.4    .045       0   363.7      .1       0
Bank Sta=301.4,363.7
XS Rating Curve= 0 ,0
Exp/Cntr=0.3,0.1

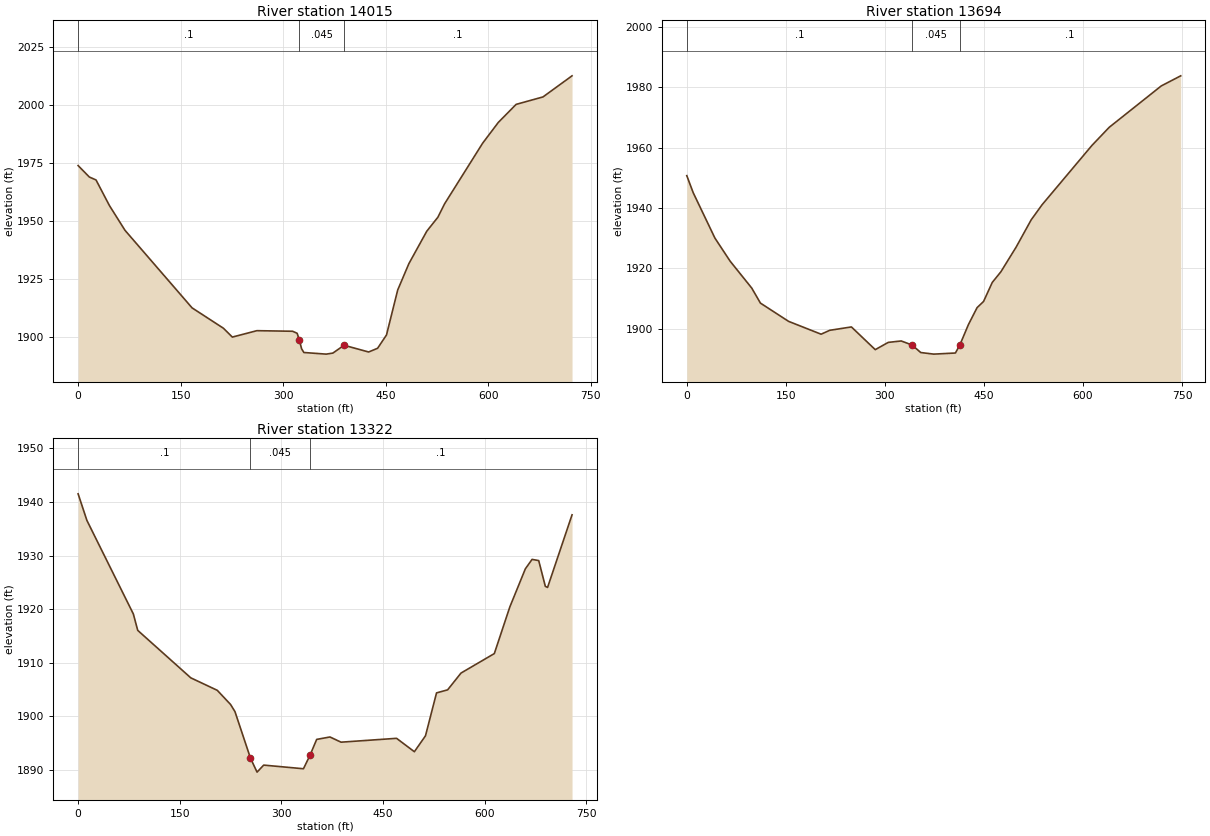
Type RM Length L Ch R = 1 ,14015   ,320.2,321.1,315.7
XS GIS Cut Line= 2
      2129102.84      241562.295     2129517.287      242154.065
#Sta/Elev= 30
       0 1973.87    16.4 1968.94    26.2 1967.67    45.8 1956.65    68.6 1945.98
   166.7 1912.58   212.5 1903.82   225.6    1900   261.5 1902.76   313.8 1902.51
   320.4 1901.63   323.6 1898.75   326.9 1894.98   330.2 1893.36   362.9 1892.66
   372.7 1893.11     389 1896.48     425 1893.58   438.1 1895.18   451.1 1900.92
   467.5 1920.29   483.8  1931.6     510 1945.59   526.3 1951.64   536.1 1957.41
   591.7 1983.49   614.6 1992.43   640.7 2000.22     680 2003.43   722.5 2012.52
#Mann= 3 ,-1 , 0
       0      .1       0   323.6    .045       0     389      .1       0
Bank Sta=323.6,389
XS Rating Curve= 0 ,0
Exp/Cntr=0.3,0.1

Type RM Length L Ch R = 1 ,13694   ,363.4,371.1,365.3
XS GIS Cut Line= 2
     2128852.636      241785.318     2129316.381      242372.191
#Sta/Elev= 30
       0 1950.73     9.8 1945.04    42.6 1930.05    65.6 1922.42    98.4 1913.48
   111.5 1908.52   154.2 1902.46   203.4 1898.21   216.5  1899.5   249.3 1900.62
   285.4 1893.09   305.1  1895.5   324.8 1895.97   341.2 1894.62   354.3 1892.14
     374 1891.61   406.8 1891.98   413.4 1894.58   426.5 1901.39   439.6    1907
   449.4 1909.05   462.6 1915.35   475.7  1918.9   498.7 1927.04   521.6 1936.11
     538 1941.08   613.5 1960.73   639.7 1966.74   718.5 1980.45     748  1983.8
#Mann= 3 ,-1 , 0
       0      .1       0   341.2    .045       0   413.4      .1       0
Bank Sta=341.2,413.4
XS Rating Curve= 0 ,0
Exp/Cntr=0.3,0.1

Type RM Length L Ch R = 1 ,13322   ,309.3,321.4,337.1
XS GIS Cut Line= 3
     2128585.558      241970.961     2128791.664      242272.415
     2129018.923       242556.49
#Sta/Elev= 30
       0 1941.52      13 1936.55    81.5  1919.1      88 1916.03   166.3 1907.17
   205.4 1904.84     225  1902.2   231.5 1900.87   254.3 1892.21   264.1 1889.57
   273.9 1890.88   332.6  1890.2   342.4 1892.76   352.1 1895.68   371.7 1896.13
   388.1 1895.16     470 1895.88   496.3 1893.38   512.7 1896.35     529 1904.36
   545.4 1904.93   565.1 1908.06   614.3  1911.7   637.2 1920.41   660.1 1927.52
     670 1929.28   679.8 1929.06   689.6 1924.25   692.9 1924.05     729  1937.6
#Mann= 3 ,-1 , 0
       0      .1       0   254.3    .045       0   342.4      .1       0
Bank Sta=254.3,342.4
XS Rating Curve= 0 ,0
Exp/Cntr=0.3,0.1