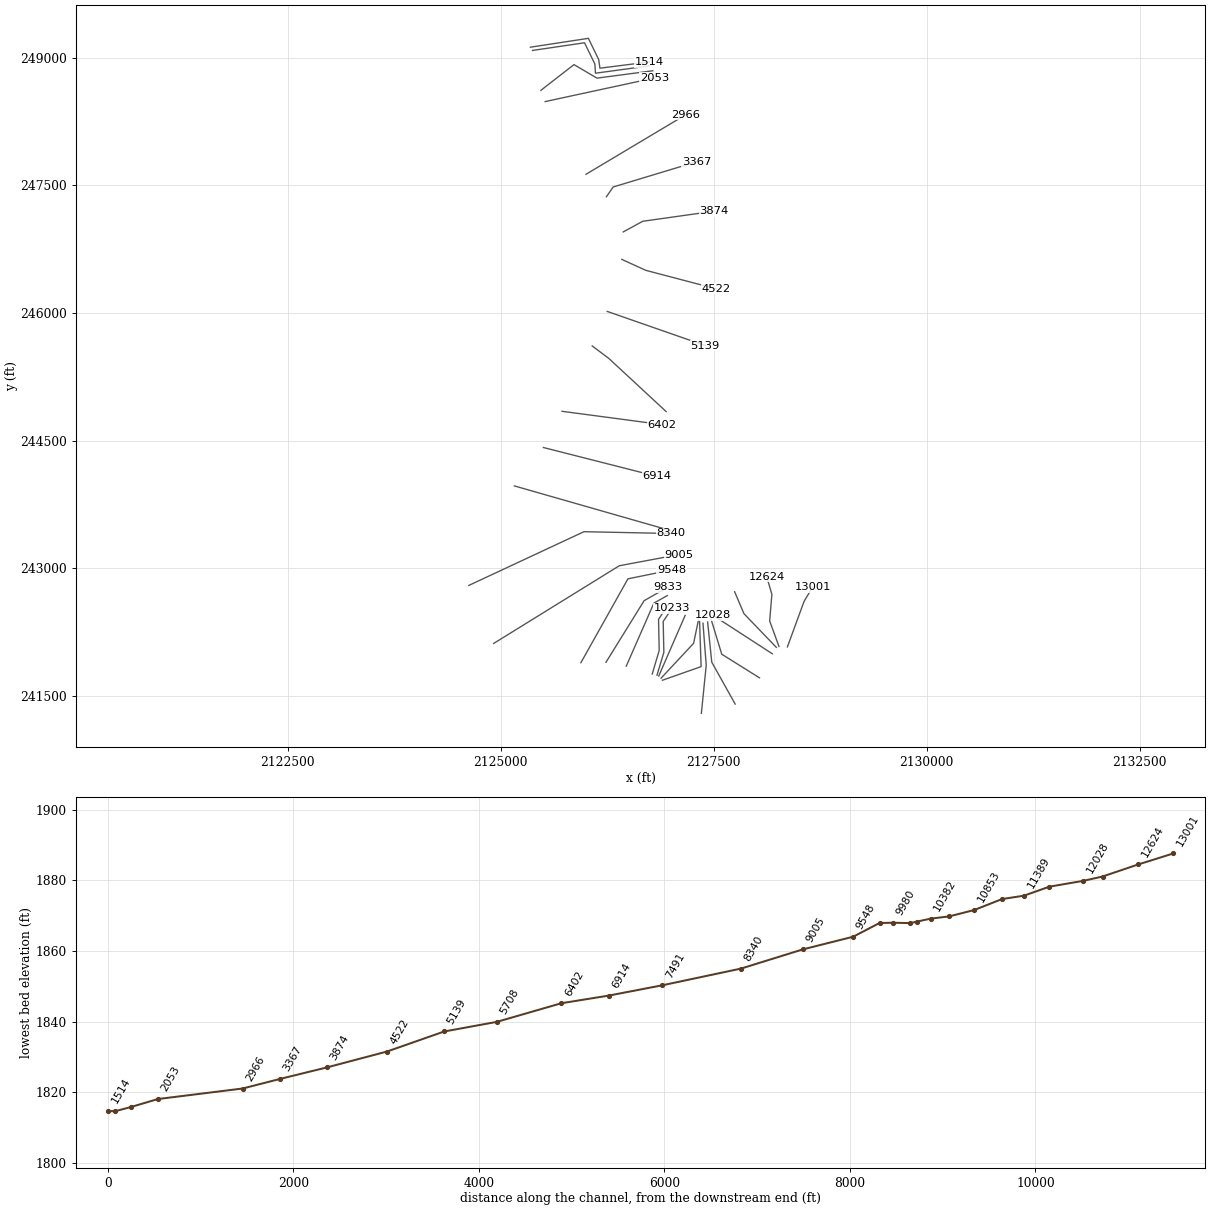
HEC-RAS study SECONDCK.prj: SECONDCK

--- SECONDCK.g01 (geometry) --- (continued)

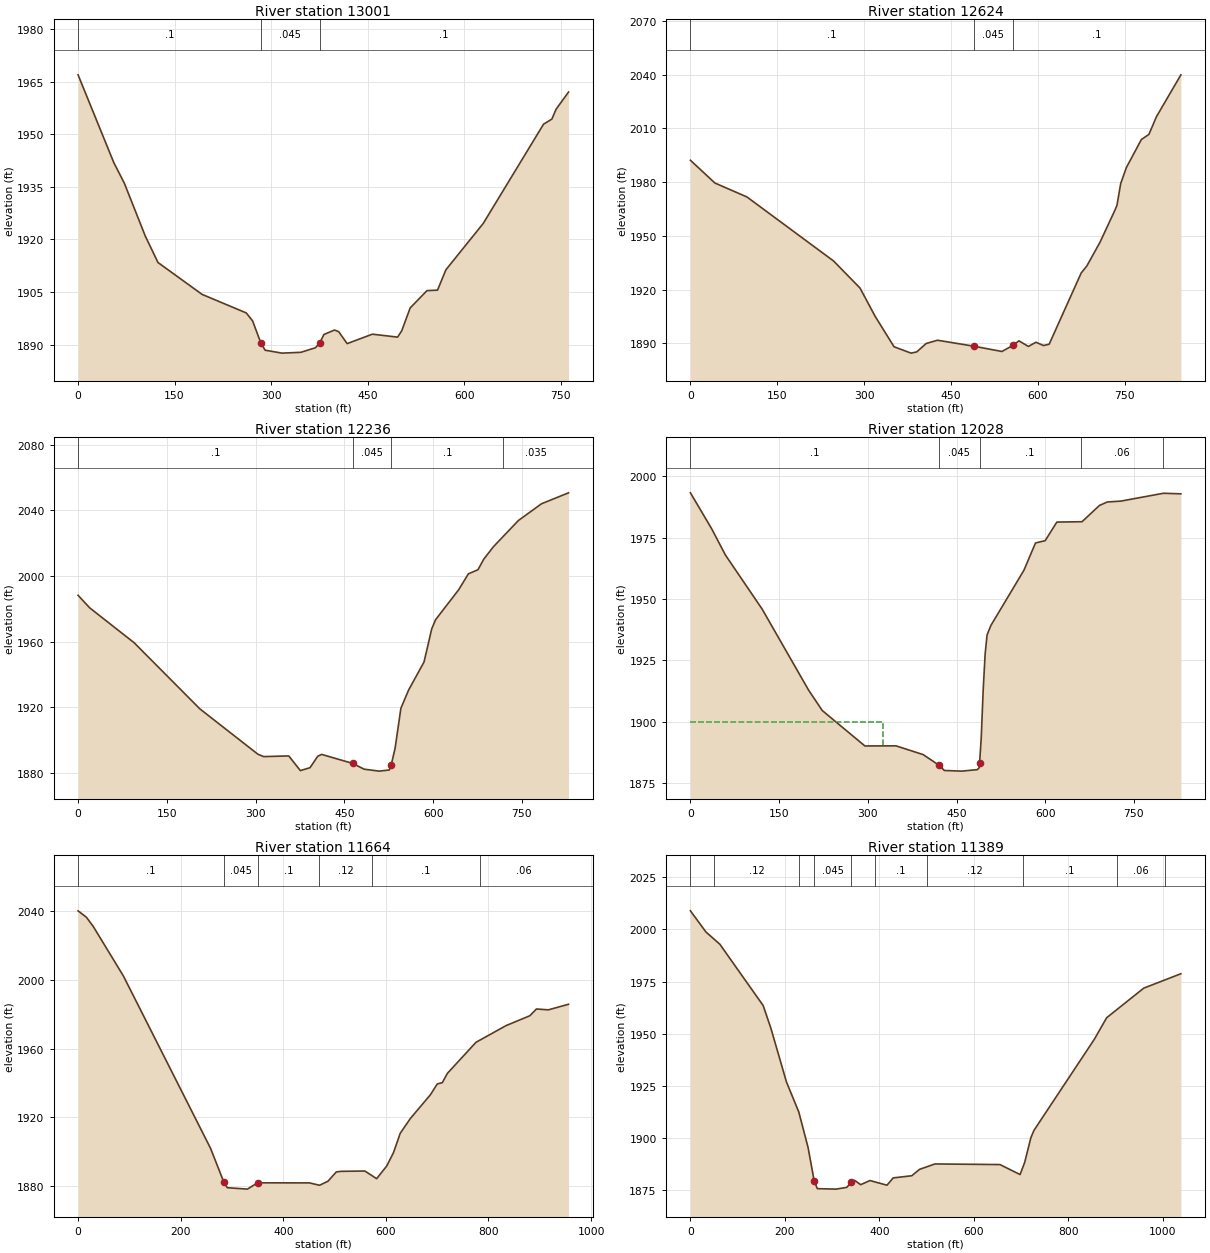
Type RM Length L Ch R = 1 ,13001   ,358.9,376.8,376.7
XS GIS Cut Line= 3
     2128365.861      242075.316     2128561.173       242609.17
     2128660.131      242775.837
#Sta/Elev= 30
       0 1966.92    55.5 1941.92    71.9 1936.04   104.5 1920.96   124.2 1913.43
   192.8 1904.34   261.4 1899.06   271.2 1896.81   284.2 1890.45   290.8 1888.43
   316.9  1887.6   346.3 1887.83   369.2 1889.15   375.7 1890.58   382.2 1892.92
   398.6 1894.18   405.1 1893.72   418.2 1890.31   457.4    1893   496.6 1892.16
   503.1 1893.97   516.2 1900.48   542.3 1905.41   558.7 1905.55   571.7 1911.35
   629.8 1924.58   723.5 1952.86   736.4  1954.3   742.9 1957.09   762.3 1962.01
#Mann= 3 ,-1 , 0
       0      .1       0   284.2    .045       0   375.7      .1       0
Bank Sta=284.2,375.7
XS Rating Curve= 0 ,0
Exp/Cntr=0.3,0.1

Type RM Length L Ch R = 1 ,12624   ,342.8,387.9,412.6
XS GIS Cut Line= 4
     2128266.902      242080.524     2128157.527      242380.004
     2128183.569      242692.504     2128123.673      242898.233
#Sta/Elev= 30
       0 1992.23    42.3 1979.51    97.6 1971.73   247.2 1935.95   292.8 1920.83
   318.8  1905.1   351.5 1888.06   380.9  1884.5   390.7 1885.19     407 1889.88
   426.6  1891.7   488.7  1888.4   537.7 1885.42   557.3 1888.93   567.1 1891.37
   583.4 1888.24   596.5 1890.58   609.5 1888.75   619.3 1889.48   674.6 1929.27
   684.4 1933.22   707.1 1946.46     733 1964.46   736.3    1967   742.8 1979.22
   752.5 1988.11   778.5 2003.83   791.5 2006.68   804.5 2016.56   846.7 2039.96
#Mann= 3 ,-1 , 0
       0      .1       0   488.7    .045       0   557.3      .1       0
Bank Sta=488.7,557.3
XS Rating Curve= 0 ,0
Exp/Cntr=0.3,0.1

Type RM Length L Ch R = 1 ,12236   ,196.1,208.4,215.2
XS GIS Cut Line= 3
     2128235.652      242070.108     2127855.444      242465.941
     2127746.069      242723.754
#Sta/Elev= 30
       0  1988.2    19.6 1980.57    94.7 1959.32   205.8 1919.02   303.8  1891.4
   313.6 1889.91   356.1 1890.32   375.7 1881.39     392 1883.14   405.1 1890.14
   411.6 1891.26   463.9 1885.79   483.5 1882.24   508.8 1881.06     526 1881.75
   529.2  1884.7   535.8 1894.99   545.6 1919.36   558.6 1930.44   584.7 1947.57
   597.7 1967.73   604.2 1973.32   643.3 1991.59   659.6 2001.26   675.9 2003.79
   685.6 2010.18   701.9 2017.77   744.2 2033.78   783.3 2043.99   828.9 2050.64
#Mann= 4 ,-1 , 0
       0      .1       0   463.9    .045       0   529.2      .1       0
  718.86    .035       0
Bank Sta=463.9,529.2
XS Rating Curve= 0 ,0
Exp/Cntr=0.3,0.1

Type RM Length L Ch R = 1 ,12028   ,367.8,364.3,367.2
XS GIS Cut Line= 2
     2128188.777      241994.587     2127492.827      242446.021
#Sta/Elev= 30
       0 1993.32    36.1 1978.59      59 1968.02   121.3  1945.9     200  1912.8
     223 1904.53   295.1 1890.09   347.6 1890.14   393.5 1886.58   419.7 1882.36
   429.5 1880.09     459 1879.83   485.3 1880.44   488.5 1881.25  489.04 1883.15
   491.8 1893.23   495.1  1912.8   498.4 1927.51   501.7 1935.36   508.2 1939.25
     564 1961.73   583.6 1972.86     600 1973.82   619.7 1981.39   662.3 1981.54
   691.8 1988.18     705 1989.58   727.9 1989.94     800 1993.14   829.5 1992.91
#Mann= 5 ,-1 , 0
       0      .1       0   419.7    .045       0  489.04      .1       0
     660     .06       0     800    .035       0
#XS Ineff= 2 , 0
          325.09    1900
Permanent Ineff=
       F       F
Bank Sta=419.7,489.04
XS Rating Curve= 0 ,0
Exp/Cntr=0.3,0.1

Type RM Length L Ch R = 1 ,11664   ,297.8,274.5,249.7
XS GIS Cut Line= 3
     2128038.306      241711.802     2127595.027      241989.379
     2127468.899       242403.53
#Sta/Elev= 30
       0 2040.35    16.3  2036.6    29.4 2031.34    88.3 2002.42   258.2    1902
   284.4 1882.09   290.9 1879.02   330.1 1878.19   349.8 1881.86   451.1 1881.82
   470.7 1880.44   487.1 1882.78   503.4 1888.22   513.2 1888.56   559.1 1888.74
     582 1884.28   601.7 1891.68   614.8 1899.45     628 1910.75   647.6 1919.29
     687 1933.26   700.1 1939.46     710 1940.24   719.8 1945.61   775.6 1963.74
   834.6 1973.52   880.5  1979.2   893.6 1983.16   916.6 1982.65     956  1985.9
#Mann= 6 ,-1 , 0
       0      .1       0   284.4    .045       0   349.8      .1       0
     470     .12       0  573.02      .1       0  783.02     .06       0
Bank Sta=284.4,349.8
XS Rating Curve= 0 ,0
Exp/Cntr=0.3,0.1

Type RM Length L Ch R = 1 ,11389   ,257.8,236.3,195.7
XS GIS Cut Line= 3
     2127752.575      241403.544      2127477.84      241895.629
     2127429.201      242367.722
#Sta/Elev= 30
       0 2008.91    32.8 1998.79    62.3 1992.91     154 1963.54   170.4 1952.62
   203.2 1927.01   229.4 1912.57     249  1895.6   262.1 1879.43   268.7 1875.87
     308 1875.64   330.9 1876.48   340.8 1878.93   347.3 1879.86   360.4 1877.77
   380.1 1879.75   416.1 1877.52   429.2 1881.01   468.6 1882.05   484.9  1885.1
   517.7  1887.7   655.2  1887.4   697.8 1882.62   707.6 1888.48   720.7 1900.32
   727.2 1903.78   854.9 1947.37   881.1 1957.72   959.6 1971.89  1038.2 1978.78
#Mann= 10 ,-1 , 0
       0     .04       0      50     .12       0     230      .1       0
   262.1    .045       0   340.8     .12       0     390      .1       0
     500     .12       0  703.58      .1       0  903.58     .06       0
 1003.58     .04       0
Bank Sta=262.1,340.8
XS Rating Curve= 0 ,0
Exp/Cntr=0.3,0.1

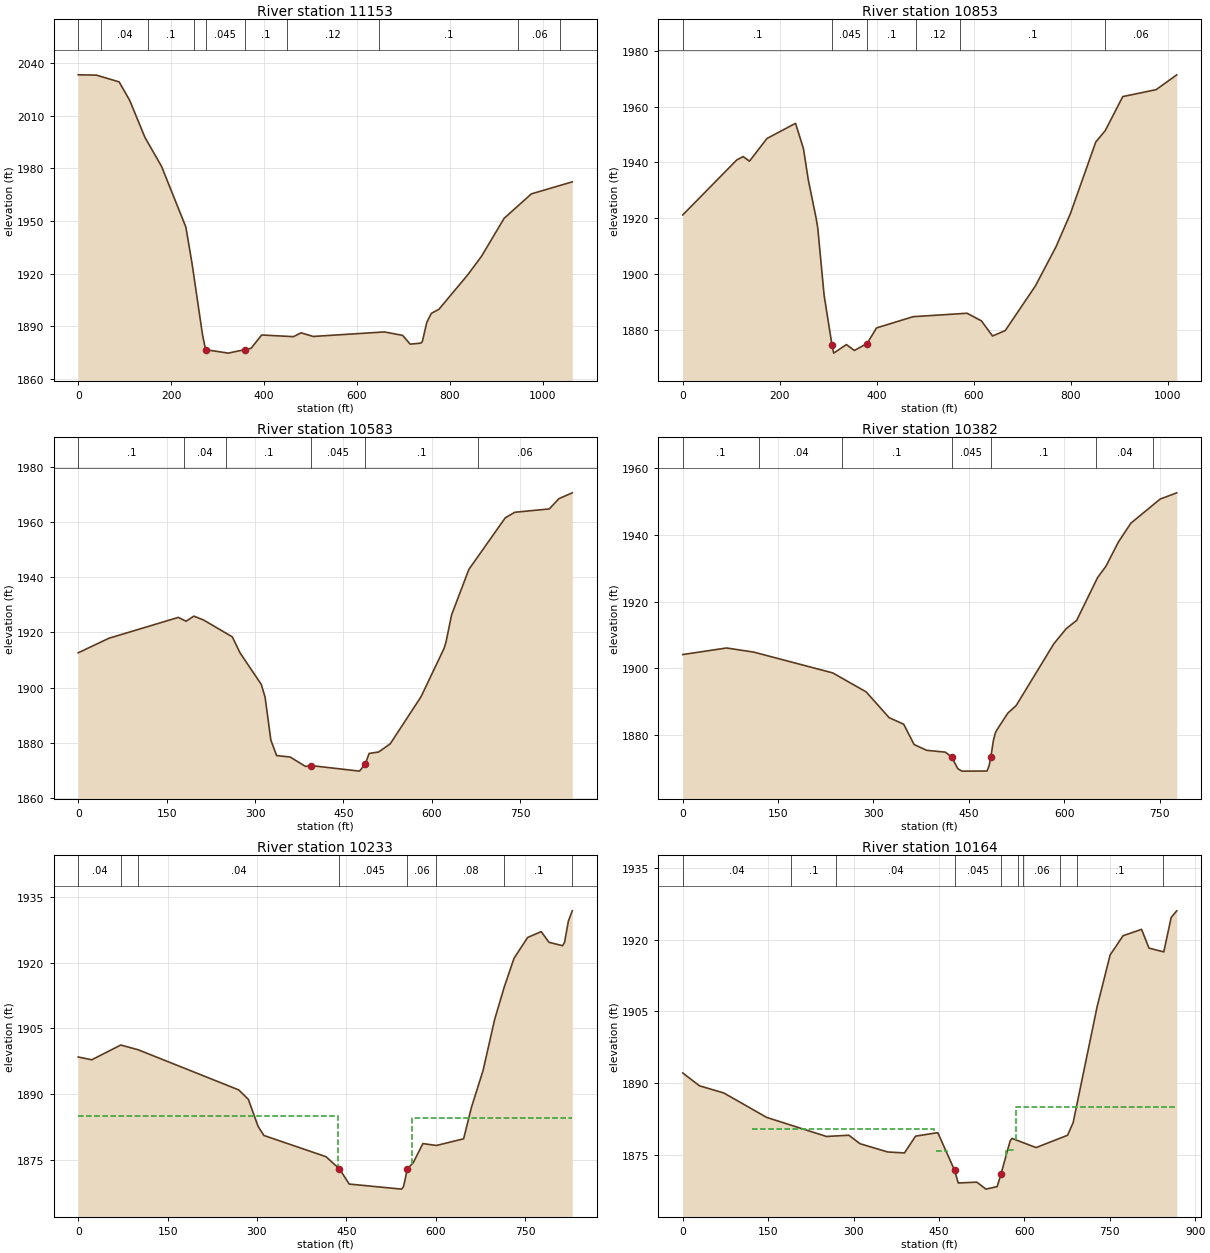
Type RM Length L Ch R = 1 ,11153   ,329.6,300.1,212.4
XS GIS Cut Line= 3
     2127355.648      241294.168     2127412.736       241859.17
     2127374.608      242353.509
#Sta/Elev= 30
       0 2033.22    39.2 2033.05    88.1 2029.19     111 2018.56   143.6 1997.59
   179.5    1981   231.7 1946.51   244.8 1926.12   267.6 1885.11   274.2 1876.65
   323.1 1874.68     359 1876.71   372.1 1877.42   394.9 1885.01   463.4 1884.06
   479.8 1886.25   505.9 1884.18   659.2 1886.75   698.4 1884.79   714.7 1879.79
   737.5 1880.37   740.8 1881.18   750.5 1892.23   760.3 1897.35   776.6 1899.66
   838.6 1919.29     868 1929.73   916.9 1951.45   975.6  1965.4  1063.7 1972.25
#Mann= 10 ,-1 , 0
       0     .06       0      50     .04       0     150      .1       0
     250     .12       0   274.2    .045       0     359      .1       0
     450     .12       0  647.88      .1       0  947.88     .06       0
 1037.88     .04       0
Bank Sta=274.2,359
XS Rating Curve= 0 ,0
Exp/Cntr=0.3,0.1

Type RM Length L Ch R = 1 ,10853   ,210.1,269.7,264.5
XS GIS Cut Line= 3
     2126898.714      241683.518      2127352.84      241843.545
     2127334.543      242380.278
#Sta/Elev= 30
       0 1921.12   111.4 1940.84   124.5 1942.05   137.6 1940.41   173.6 1948.53
   232.6 1953.98   248.9 1944.87   258.8 1933.76   275.1  1919.9   278.4  1916.4
   291.5 1892.28   307.9 1874.32   311.2 1871.58   337.4 1874.65   353.8 1872.53
     380 1875.02   399.6 1880.62     475 1884.65   586.3 1885.88   615.8 1883.14
   638.7 1877.72   664.9 1879.67   727.1 1895.68   769.7 1909.77   799.1 1921.55
   851.5 1947.27   871.2  1951.4   907.2 1963.56     976 1966.05  1018.5 1971.36
#Mann= 6 ,-1 , 0
       0      .1       0   307.9    .045       0     380      .1       0
     480     .12       0   571.5      .1       0   871.5     .06       0
Bank Sta=307.9,380
XS Rating Curve= 0 ,0
Exp/Cntr=0.3,0.1

Type RM Length L Ch R = 1 ,10583   ,177.7,201.1,210.5
XS GIS Cut Line= 3
     2126883.115      241708.345     2127264.298      242116.983
      2127321.59       242390.42
#Sta/Elev= 30
       0 1912.65    52.3 1917.93   169.9 1925.47     183 1924.07   196.1 1925.92
   212.4 1924.55   261.4 1918.42   274.5 1912.63   310.5 1901.21     317 1896.59
   326.8 1881.03   336.6 1875.41   359.5 1874.89   385.6 1871.49   395.4 1871.78
   477.1 1869.78   486.9 1872.26   493.5 1876.18   509.8 1876.72   529.4 1879.69
   581.6 1896.73   620.6  1914.2   623.8 1916.38   633.5 1926.42   662.8 1942.86
   724.5 1961.53   740.7 1963.55   799.2 1964.76   815.5 1968.47   838.2 1970.59
#Mann= 6 ,-1 , 0
       0      .1       0     180     .04       0     250      .1       0
   395.4    .045       0   486.9      .1       0  678.83     .06       0
Bank Sta=395.4,486.9
XS Rating Curve= 0 ,0
Exp/Cntr=0.3,0.1

Type RM Length L Ch R = 1 ,10382   ,118,148.6,180.7
XS GIS Cut Line= 2
     2126855.337      241732.651      2127165.34      242445.108
#Sta/Elev= 30
       0  1904.1    68.8 1906.07   111.5 1904.84     236 1898.59   288.5  1892.9
   324.6 1885.18   347.5 1883.21   363.9 1877.11   383.6 1875.39   413.1 1874.83
   422.9 1873.36   432.8 1869.84   439.3 1869.14   478.6 1869.17   481.9  1870.8
  484.53  1873.3   488.5 1878.21   491.8  1880.7     495 1881.77   511.4 1886.55
   524.5 1888.83   583.6 1907.32   603.2 1911.88   619.6 1914.36   652.4 1927.16
   665.5 1930.55   685.2 1937.85   704.8 1943.49   750.8 1950.72     777  1952.6
#Mann= 7 ,-1 , 0
       0      .1       0     120     .04       0     250      .1       0
   422.9    .045       0  484.53      .1       0     650     .04       0
     740     .06       0
Bank Sta=422.9,484.53
XS Rating Curve= 0 ,0
Exp/Cntr=0.5,0.3

Type RM Length L Ch R = 1 ,10233   ,71,69.8,61.4
XS GIS Cut Line= 4
     2126834.504      241743.067      2126915.34      242010.212
     2126907.527      242374.795     2127011.694      242528.441
#Sta/Elev= 30
       0 1898.46    22.7 1897.82    71.4 1901.19   100.6 1900.11   269.4 1890.95
   285.6 1888.79   301.9 1882.63   311.7 1880.54   415.9  1875.7   438.6  1872.9
   454.9 1869.45   542.8 1868.29   546.1 1868.86   552.6 1872.94   562.4 1874.32
   578.6 1878.69   601.4 1878.26     647 1879.78   660.1 1886.96   679.6 1895.36
   699.1 1907.04   715.4 1914.52   731.7 1921.02   754.5 1925.75   777.3 1927.08
   790.3 1924.64   813.1 1923.87   816.4 1924.61   822.9  1929.5   829.4 1931.83
#Mann= 8 ,-1 , 0
       0     .04       0    71.4      .1       0   100.6     .04       0
   438.6    .045       0   552.6     .06       0   601.4     .08       0
   715.4      .1       0   829.4     .04       0
#XS Ineff= 2 , 0
          436.36 1884.96  560.61         1884.42
Permanent Ineff=
       F       F
Bank Sta=438.6,552.6
XS Rating Curve= 0 ,0
Exp/Cntr=0.5,0.3

Type RM Length L Ch R = 1 ,10164   ,213.1,183.3,160.6
XS GIS Cut Line= 4
     2126778.948      241756.956     2126860.652      242033.649
      2126852.84      242398.233     2126970.027       242577.92
#Sta/Elev= 30
       0 1892.15    29.5 1889.46    72.1 1887.97   147.5 1882.86   252.4 1878.88
   291.8 1879.14   311.3 1877.37   360.1 1875.64   389.4 1875.44     409 1878.95
     448 1879.68   477.4 1871.83   483.9 1869.16   516.4 1869.34   532.7 1867.88
   552.2 1868.41   558.8 1870.95     575 1877.94   578.3 1878.48   620.6 1876.56
   675.9 1879.13   685.7 1881.77   727.9 1906.04   750.7 1916.81   773.4 1920.82
   805.9 1922.15   818.9 1918.23   844.9 1917.44   857.9 1924.64   867.7 1926.02
#Mann= 10 ,-1 , 0
       0     .04       0     190      .1       0     270     .04       0
   477.4    .045       0   558.8     .06       0   588.5     .08       0
   598.5     .06       0  663.17     .08       0  693.17      .1       0
  843.17     .04       0
#XS Ineff= 5 ,-1
       0  120.89  1878.8  120.89  440.631880.428  444.86  463.511875.845
  567.68  583.511876.027  585.07   867.7 1885.05
Permanent Ineff=
       F       F       F       F       F
Bank Sta=477.4,558.8
XS Rating Curve= 0 ,0
Exp/Cntr=0.5,0.3

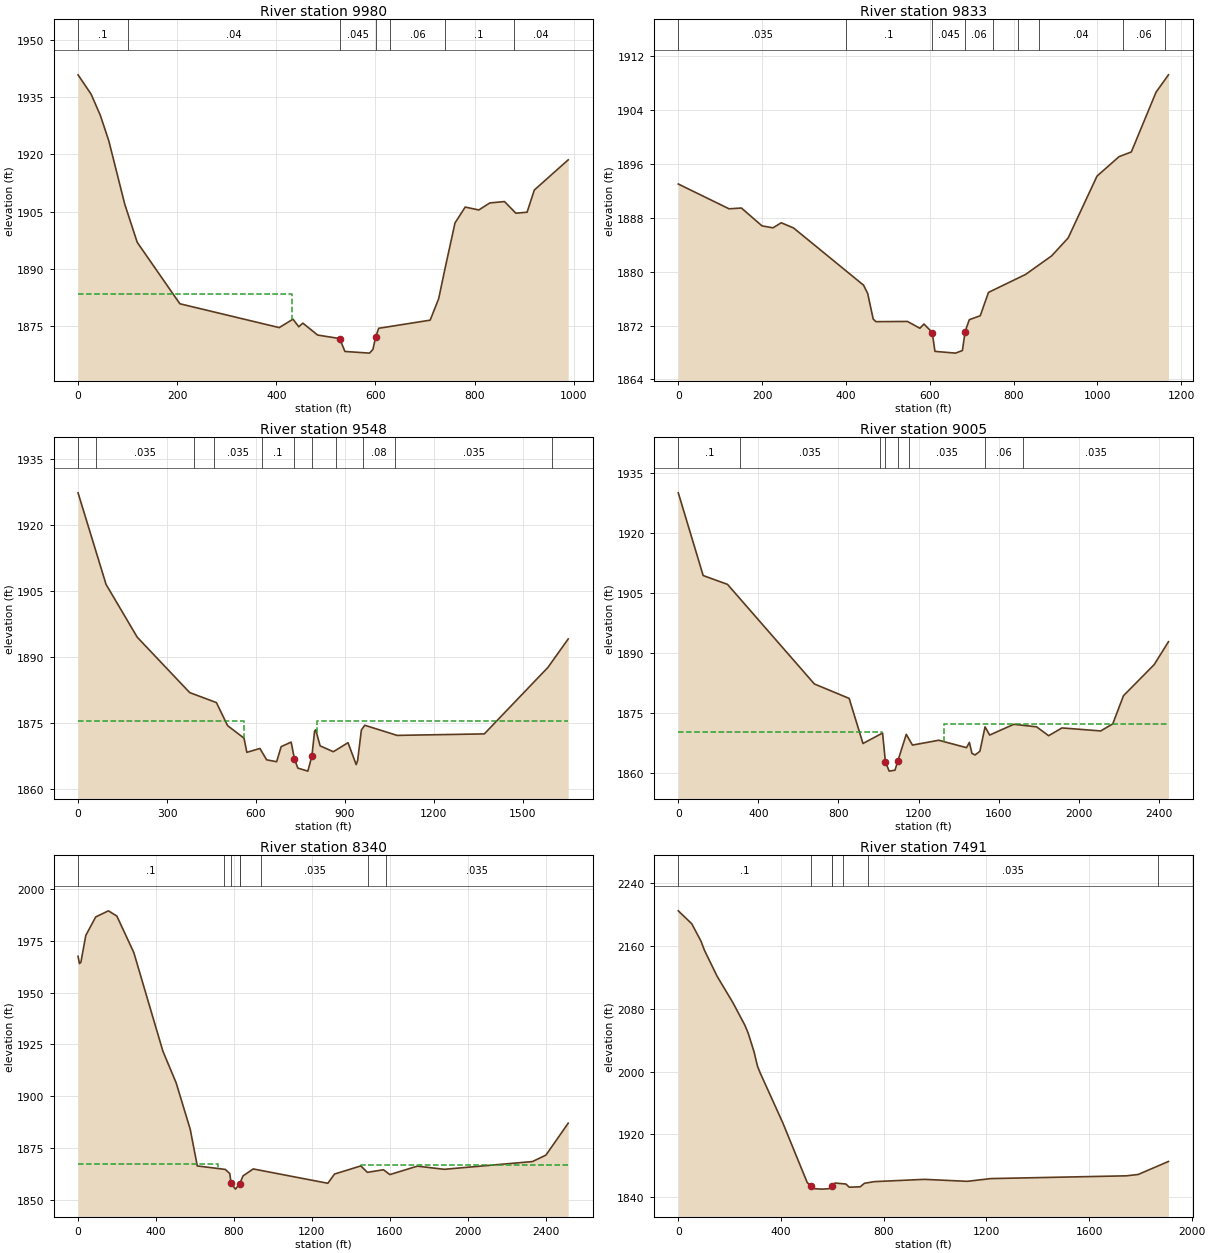
Type RM Length L Ch R = 1 ,9980    ,153.6,147.7,140.5
XS GIS Cut Line= 3
2126473.94541306241849.0436687432126798.22477352 242589.70540329
2126955.56742179242677.970791345
#Sta/Elev= 30
       0 1940.83    26.3 1935.78      45 1930.22    62.1 1923.53    94.3 1906.94
   119.4 1896.99   205.4 1880.91   405.9 1874.67   433.6 1876.88   445.3 1874.89
   453.5 1875.84   483.4 1872.72   527.7 1871.81   538.4 1868.43     588 1867.99
   594.9 1868.97   600.5 1872.23   606.5 1874.49   710.4 1876.62   727.5 1882.22
     740 1889.91   760.5 1902.07   781.1 1906.22   808.5 1905.46   830.7  1907.3
   860.3 1907.66   883.3 1904.61   905.9 1904.87   920.5 1910.68   988.9 1918.58
#Mann= 7 ,-1 , 0
       0      .1       0     100     .04       0   527.7    .045       0
   600.5     .04       0     630     .06       0     740      .1       0
  878.54     .04       0
#XS Ineff= 2 , 0
          431.58 1883.41
Permanent Ineff=
       F       F
Bank Sta=527.7,600.5
XS Rating Curve= 0 ,0
Exp/Cntr(USF)=0,0
Exp/Cntr=0.3,0.1

Type RM Length L Ch R = 1 ,9833    ,281.4,284.3,287.8
XS GIS Cut Line= 3
     2126235.545      241894.109     2126683.462      242618.067
     2126959.611      242775.837
#Sta/Elev= 30
       0    1893   121.2 1889.32   150.6 1889.44   199.7 1886.79   225.9  1886.5
   245.6 1887.25     275 1886.48     442 1877.99   451.8 1876.77     465 1872.97
   471.5 1872.58   546.8 1872.61   576.3  1871.6   586.1 1872.23   605.8 1870.97
   612.3 1868.17   661.4 1867.91   677.8  1868.3   684.3 1871.11   694.2 1872.87
   720.4 1873.46     740 1876.92   828.4 1879.58   890.7 1882.34     930 1884.99
   998.9 1894.17  1051.3 1897.05  1080.8 1897.76  1139.8 1906.63  1169.4  1909.2
#Mann= 9 ,-1 , 0
       0    .035       0     400      .1       0   605.8    .045       0
   684.3     .06       0     750     .04       0     810     .06       0
  861.32     .04       0 1061.32     .06       0 1161.32    .035       0
Bank Sta=605.8,684.3
XS Rating Curve= 0 ,0
Exp/Cntr=0.3,0.1

Type RM Length L Ch R = 1 ,9548    ,557.7,543.5,515.1
XS GIS Cut Line= 3
2125941.12949437241889.2051536132126493.54896506242874.894797388
2127006.25200321242979.601755884
#Sta/Elev= 30
       0 1927.27    94.5 1906.46   199.7 1894.46   376.5 1881.88   466.7  1879.6
   504.3 1874.37   559.7 1871.53   569.3  1868.3   613.4 1869.18     636  1866.6
   669.8 1866.17     685 1869.59   718.7 1870.63     730 1866.78   741.3 1864.72
   775.1 1864.03   788.7 1867.44   797.7 1873.08   801.4 1873.43   816.5 1869.77
     861 1868.44   910.5 1870.49   938.1 1865.51   942.9 1866.42   955.6 1873.38
   966.9 1874.46    1076 1872.15  1370.2 1872.49  1584.8  1887.6  1653.2 1894.07
#Mann= 11 ,-1 , 0
       0      .1       0      60    .035       0     390     .06       0
     460    .035       0     620      .1       0     730    .045       0
   788.7      .1       0     870     .04       0     960     .08       0
    1070    .035       0 1599.93      .1       0
#XS Ineff= 2 , 0
          558.95 1875.38  804.52         1875.38
Permanent Ineff=
       F       F
Bank Sta=730,788.7
XS Rating Curve= 0 ,0
Exp/Cntr(USF)=0,0
Exp/Cntr=0.3,0.1

Type RM Length L Ch R = 1 ,9005    ,664.9,665.1,661.7
XS GIS Cut Line= 3
     2124917.309      242115.9592126392.19935592 243028.67575257
2127094.18085858243160.179545474
#Sta/Elev= 30
       0 1930.02   124.3 1909.34   245.9 1907.13   679.8 1882.23   853.6 1878.62
   922.6 1867.35  1020.5 1869.97  1034.7 1862.76  1053.5 1860.44  1082.4 1860.67
  1096.7 1862.97  1138.9 1869.64  1169.8 1866.95    1301 1868.16  1439.9 1866.31
  1454.2 1867.63  1466.9 1864.87  1482.8 1864.49  1506.7  1865.4  1532.4 1871.51
  1555.6 1869.46  1675.9 1872.14    1790 1871.52  1850.1  1869.3  1916.8 1871.24
  2110.4 1870.49  2170.5 1872.26  2223.9 1879.29  2377.5 1887.08  2448.7  1892.8
#Mann= 8 ,-1 , 0
       0      .1       0     310    .035       0    1010      .1       0
  1034.7    .045       0  1096.7      .1       0    1150    .035       0
    1530     .06       0    1720    .035       0
#XS Ineff= 2 , 0
         1018.28  1870.2 1328.95         1872.26
Permanent Ineff=
       F       F
Bank Sta=1034.7,1096.7
XS Rating Curve= 0 ,0
Exp/Cntr=0.3,0.1

Type RM Length L Ch R = 1 ,8340    ,861.2,849.1,826.4
XS GIS Cut Line= 3
2124625.95750147242797.8828294142125976.97413637243428.664025018
2127000.91993173243407.670480427
#Sta/Elev= 30
       0 1967.61     7.2 1964.12    14.5 1964.69    39.8 1977.73    90.5 1986.64
   155.7 1989.61   199.1 1987.09     286 1969.47   435.3 1921.75   503.3 1906.45
   575.7 1883.93   611.9 1866.23   755.6 1864.55   778.4 1862.56   785.7 1857.77
   807.6 1855.02   829.7 1857.63   846.3  1861.4   898.8 1864.78  1281.7 1857.85
  1315.9 1862.31  1451.2 1866.25  1484.5 1863.13  1567.2  1864.4    1600 1862.05
  1741.1 1866.14  1878.9  1864.6  2331.7 1868.35  2400.7 1871.46  2515.2 1886.91
#Mann= 8 ,-1 , 0
       0      .1       0     750     .06       0   785.7    .045       0
   829.7     .06       0     830      .1       0     940    .035       0
    1490     .08       0 1581.02    .035       0
#XS Ineff= 2 , 0
           718.3 1867.02 1454.25         1866.85
Permanent Ineff=
       F       F
Bank Sta=785.7,829.7
XS Rating Curve= 0 ,0
Exp/Cntr(USF)=0,0
Exp/Cntr=0.3,0.1

Type RM Length L Ch R = 1 ,7491    ,569.1,576.6,569.1
XS GIS Cut Line= 2
     2125160.365      243966.654     2126995.962      243440.984
#Sta/Elev= 30
       0 2204.93    52.5 2188.43    88.6 2166.16   101.7 2154.79   150.9 2121.76
   213.2 2087.62   259.2 2059.25   272.3 2049.01   295.3 2025.01   308.4 2007.14
   318.2 1998.96   406.8 1934.99     502 1858.83   515.1 1854.48   531.5 1850.81
     561 1850.29   587.2 1850.84   597.1 1853.71   610.2 1858.07   652.9 1856.81
     666 1852.74   708.6 1853.26     725 1857.73   764.4 1859.86     958 1862.75
  1125.3 1860.23  1217.2 1863.72  1745.4 1867.24  1791.3 1868.95  1909.4 1885.54
#Mann= 7 ,-1 , 0
       0      .1       0   515.1    .045       0   597.1      .1       0
     600    .035       0     640     .06       0     740    .035       0
    1870      .1       0
Bank Sta=515.1,597.1
XS Rating Curve= 0 ,0
Exp/Cntr=0.3,0.1

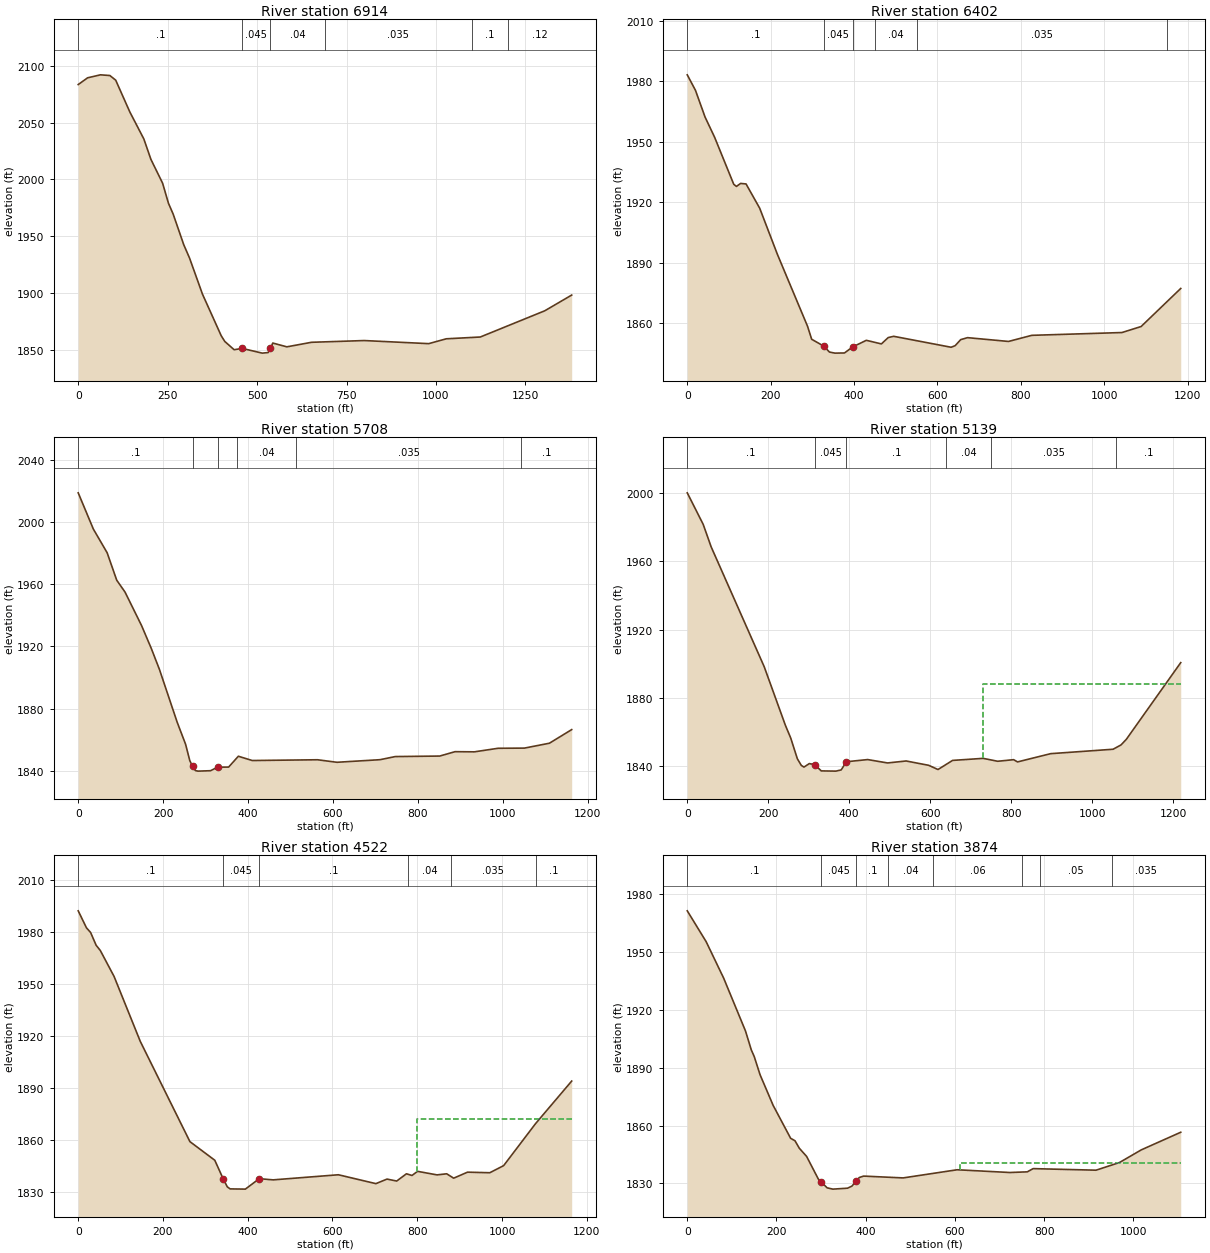
Type RM Length L Ch R = 1 ,6914    ,504.6,512,515.8
XS GIS Cut Line= 2
     2125500.643      244418.043     2126837.448      244077.765
#Sta/Elev= 30
       0 2083.42    26.2 2089.32    62.2 2091.96    88.5 2091.35   104.8 2087.26
   144.2 2059.38   183.5 2035.58   203.2 2017.68   235.9 1996.72   252.3 1979.06
   265.4 1969.58   294.9 1942.75   311.3 1930.84   347.3 1899.24   399.7 1862.68
   409.6 1857.69   435.8 1850.38   458.7  1851.5   514.4 1847.38   530.8 1847.86
   537.4 1851.52   543.9 1856.24   583.2  1852.9     652  1856.9   799.5 1858.43
   979.7 1855.71  1028.8 1859.97  1123.9 1861.54  1304.1 1884.58  1379.4 1898.41
#Mann= 6 ,-1 , 0
       0      .1       0   458.7    .045       0   537.4     .04       0
     690    .035       0    1100      .1       0    1200     .12       0
Bank Sta=458.7,537.4
XS Rating Curve= 0 ,0
Exp/Cntr=0.3,0.1

Type RM Length L Ch R = 1 ,6402    ,714,694,663.1
XS GIS Cut Line= 2
     2125720.316      244843.264     2126893.638      244687.295
#Sta/Elev= 30
       0 1983.19    19.7  1975.5    42.6  1962.3    65.6 1952.24   111.5 1928.92
     118 1927.87   127.9 1929.34     141 1929.09   173.8 1917.03   216.4 1894.08
   288.5 1858.52   298.4 1852.09   327.9 1848.61     341 1845.75   354.1 1845.21
   377.1 1845.29   396.7 1848.28   429.5 1851.56   465.6 1849.78     482 1852.92
   495.1 1853.55   632.8 1848.12   642.6 1848.92   655.8  1851.9   672.2 1852.88
   770.5    1851   826.3 1854.03  1042.7 1855.42  1088.6 1858.41  1183.6 1877.27
#Mann= 6 ,-1 , 0
       0      .1       0   327.9    .045       0   396.7      .1       0
     450     .04       0     550    .035       0    1150      .1       0
Bank Sta=327.9,396.7
XS Rating Curve= 0 ,0
Exp/Cntr=0.3,0.1

Type RM Length L Ch R = 1 ,5708    ,551,568.7,586.6
XS GIS Cut Line= 3
     2126074.194      245610.906     2126268.638      245465.073
      2126942.25      244840.073
#Sta/Elev= 30
       0  2018.7    35.6 1995.45    68.1 1980.22    90.7 1962.58   110.2 1954.98
   149.1 1933.48   171.8 1918.95   191.2 1905.33   233.3 1871.16   252.9 1857.17
   262.7 1846.72   269.2 1843.09   275.8 1840.31   282.3 1839.95   311.7 1840.22
   328.1 1842.49   354.2 1842.56   377.1 1849.51   409.8 1846.76   563.5 1847.25
   609.3 1845.63   710.7  1847.3   746.6  1849.3   851.3 1849.63   887.3 1852.44
     933 1852.34   988.6 1854.62  1050.8 1854.74  1109.6 1857.88    1162 1866.62
#Mann= 6 ,-1 , 0
       0      .1       0   269.2    .045       0   328.1      .1       0
  373.05     .04       0  513.05    .035       0 1043.05      .1       0
Bank Sta=269.2,328.1
XS Rating Curve= 0 ,0
Exp/Cntr=0.3,0.1

Type RM Length L Ch R = 1 ,5139    ,611.1,616.9,619.6
XS GIS Cut Line= 2
     2126250.532      246016.897     2127401.236      245615.572
#Sta/Elev= 30
       0 2000.04    39.3 1981.61      59 1968.44     190 1898.32   242.4    1864
   255.5 1856.59   271.9 1844.44   281.7 1840.56   288.3 1839.59   301.4 1841.63
   314.5 1841.03   330.9 1837.36   366.9 1837.22     380 1837.91   393.1 1842.71
   445.5 1843.98   494.7    1842   540.5 1843.16   596.2 1840.62   619.2 1838.16
   655.2 1843.49   730.6 1844.69   766.6 1842.99   805.9 1843.92   815.7 1842.62
   897.6 1847.44  1051.6 1850.02  1071.3 1852.56  1084.4 1855.85  1218.7  1900.7
#Mann= 6 ,-1 , 0
       0      .1       0   314.5    .045       0   393.1      .1       0
     640     .04       0     750    .035       0    1060      .1       0
#XS Ineff= 2 , 0
                          729.13         1888.11
Permanent Ineff=
       F       F
Bank Sta=314.5,393.1
XS Rating Curve= 0 ,0
Exp/Cntr=0.3,0.1

Type RM Length L Ch R = 1 ,4522    ,628,648.4,667.6
XS GIS Cut Line= 3
     2126421.416      246628.268     2126702.666      246499.795
     2127529.708      246282.238
#Sta/Elev= 30
       0 1992.37    19.5 1982.53    29.3 1979.84    42.3 1972.46    52.1 1969.46
    84.6 1954.47   146.5  1916.9   263.6 1858.99   322.3 1848.23     342 1837.52
   351.8 1832.87   358.4 1831.69   394.4 1831.55   427.2 1837.59   459.9  1836.9
   613.9 1839.85   702.4 1834.72   728.6 1837.35   751.5 1836.22   774.5 1840.42
   787.6 1839.45   800.7 1841.83   846.6 1839.78   869.5 1840.41   885.9 1837.88
   918.6 1841.35   971.1 1841.02  1003.8 1845.12  1079.2 1869.42  1164.4 1893.99
#Mann= 6 ,-1 , 0
       0      .1       0     342    .045       0   427.2      .1       0
   779.2     .04       0   879.2    .035       0  1079.2      .1       0
#XS Ineff= 2 , 0
                          798.99         1872.12
Permanent Ineff=
       F       F
Bank Sta=342,427.2
XS Rating Curve= 0 ,0
Exp/Cntr=0.3,0.1

Type RM Length L Ch R = 1 ,3874    ,497.5,507.1,514.1
XS GIS Cut Line= 3
     2126438.777      246951.184     2126667.944      247076.184
      2127504.75       247194.24
#Sta/Elev= 30
       0 1971.21    42.4 1955.21    81.6 1936.34   130.5 1908.98   143.6 1899.12
   150.1 1895.73   163.2  1886.3   192.5 1870.44   231.7 1853.38   241.5  1852.1
   251.2 1848.22   267.6 1843.97   293.8 1832.26   300.4 1830.75   313.4 1827.73
   326.5 1827.05   359.3 1827.54   369.1 1828.62     379  1831.3   385.5 1833.06
   395.3  1833.8   483.8 1832.86     605 1837.08   722.9 1835.66   762.2    1836
   775.3 1837.67   916.2 1836.86   968.6 1840.81  1017.7 1847.39  1106.1 1856.51
#Mann= 8 ,-1 , 0
       0      .1       0   300.4    .045       0     379      .1       0
  451.04     .04       0  551.04     .06       0  751.04    .035       0
  791.04     .05       0  951.04    .035       0
#XS Ineff= 2 , 0
                          611.05         1840.65
Permanent Ineff=
       F       F
Bank Sta=300.4,379
XS Rating Curve= 0 ,0
Exp/Cntr=0.3,0.1

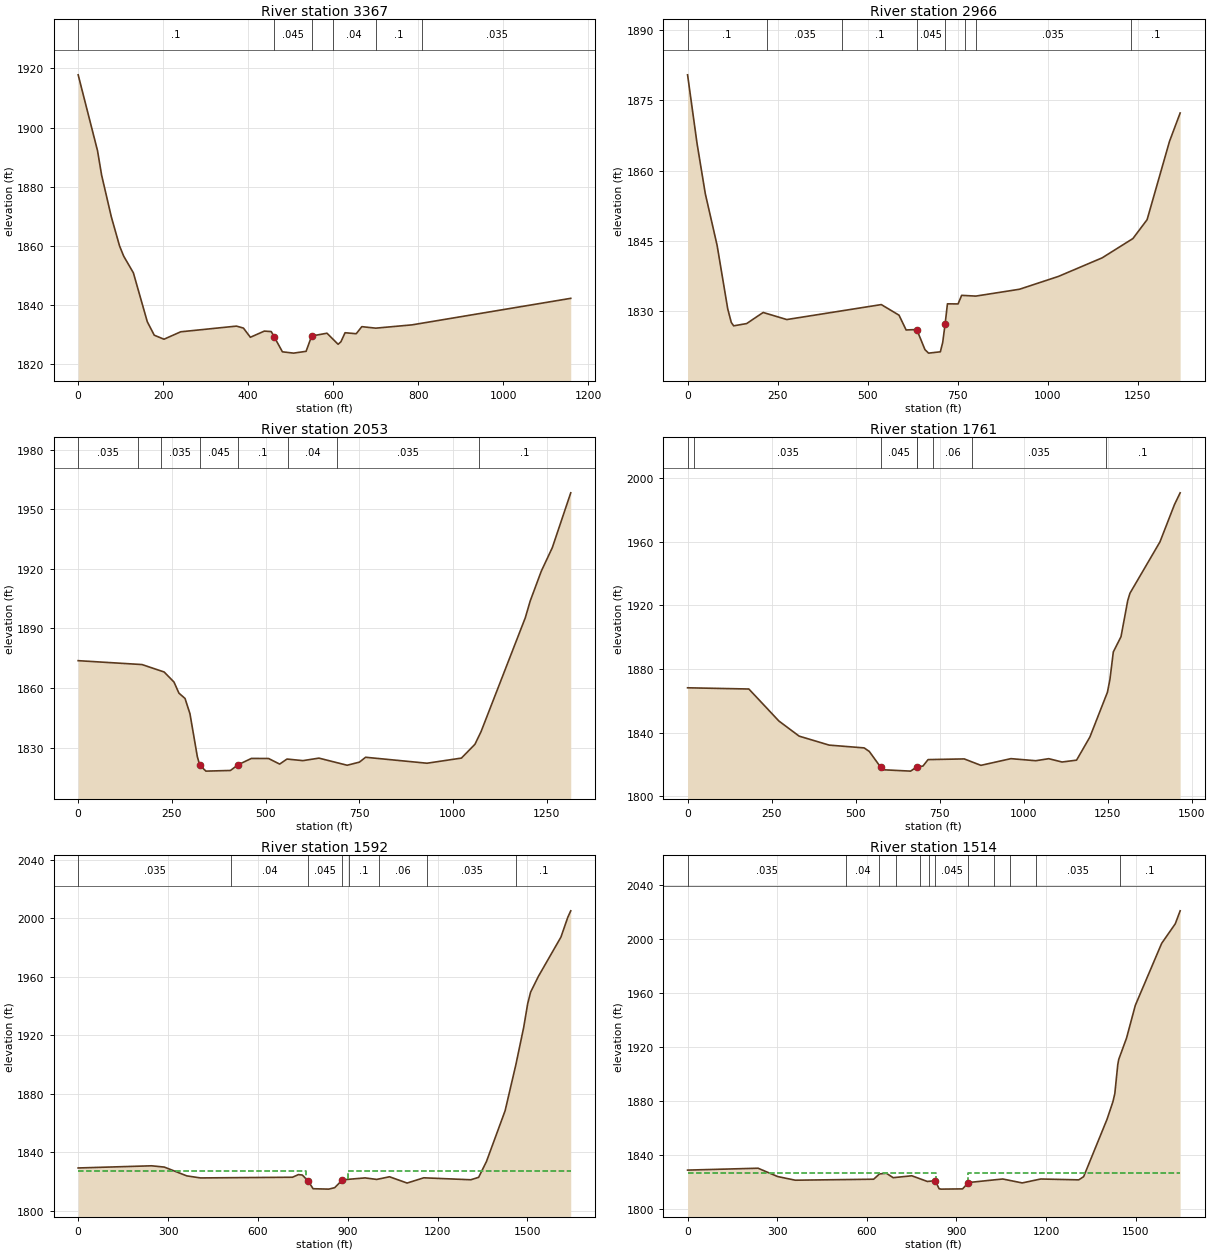
Type RM Length L Ch R = 1 ,3367    ,389.5,400.7,412.7
XS GIS Cut Line= 3
     2126240.861      247364.379     2126320.722      247478.962
     2127296.416      247774.101
#Sta/Elev= 30
       0 1917.84    45.5 1892.22    55.2 1883.92      78 1869.84    97.4    1860
   107.2 1856.53   129.9 1850.92   162.6 1834.41     179 1829.84   201.9 1828.48
   241.3 1830.99   372.4 1832.91   388.8 1832.25   405.2 1829.14   437.9 1831.22
   454.3 1831.07   460.9 1829.37   480.6 1824.22   506.8 1823.78   536.3 1824.39
   549.4 1829.57   585.4 1830.51   611.6 1826.77   618.2 1827.61     628 1830.67
   654.3 1830.34   667.4 1832.73   700.2 1832.22   785.4 1833.33    1159  1842.3
#Mann= 6 ,-1 , 0
       0      .1       0   460.9    .045       0   549.4      .1       0
  599.67     .04       0  699.67      .1       0  809.67    .035       0
Bank Sta=460.9,549.4
XS Rating Curve= 0 ,0
Exp/Cntr=0.3,0.1

Type RM Length L Ch R = 1 ,2966    ,944.2,912.8,897.4
XS GIS Cut Line= 2
     2126001.277      247628.268     2127174.888      248329.656
#Sta/Elev= 30
       0 1880.43    26.2 1865.84    49.2 1855.08      82 1844.06   111.5 1830.51
   121.3 1827.63   127.9 1826.91   163.9 1827.39   209.8 1829.76   275.4 1828.25
   537.7 1831.44   586.9 1829.18   606.6 1826.03   636.1 1826.12     659 1821.82
   668.9 1821.09   701.6 1821.37   708.2 1823.39   714.8 1827.29   721.3  1831.6
   750.8 1831.58   760.7 1833.41     800 1833.25   921.3 1834.71  1029.5 1837.45
  1150.8 1841.41  1236.1 1845.52  1275.4 1849.54  1337.7 1866.26  1367.2 1872.29
#Mann= 8 ,-1 , 0
       0      .1       0     220    .035       0     430      .1       0
   636.1    .045       0   714.8     .04       0     770     .06       0
     800    .035       0    1230      .1       0
Bank Sta=636.1,714.8
XS Rating Curve= 0 ,0
Exp/Cntr=0.3,0.1

Type RM Length L Ch R = 1 ,2053    ,345.7,292,255.5
XS GIS Cut Line= 2
     2125522.111      248482.434     2126806.833      248760.212
#Sta/Elev= 30
       0 1873.74   170.4 1871.78   229.4 1868.04   255.7 1862.97   268.8 1857.41
   285.2 1854.69   298.3 1847.02     318  1825.4   324.5 1821.06   340.9 1818.11
   406.4 1818.44   426.1 1821.26   462.2  1824.5   508.1 1824.47   537.6 1821.66
   557.2 1824.19   599.8 1823.39   642.4 1824.66   717.8 1821.07   750.6 1822.65
     767 1825.09   930.9 1822.09  1022.7 1824.68  1058.7 1831.61  1075.1 1838.02
  1193.1 1895.34  1206.2 1903.79  1235.7 1918.77  1265.2 1930.67  1314.4 1958.27
#Mann= 8 ,-1 , 0
       0    .035       0     160      .1       0     220    .035       0
   324.5    .045       0   426.1      .1       0     560     .04       0
     690    .035       0    1070      .1       0
Bank Sta=324.5,426.1
XS Rating Curve= 0 ,0
Exp/Cntr=0.3,0.1

Type RM Length L Ch R = 1 ,1761    ,208.2,169.8,131.2
XS GIS Cut Line= 4
2125471.77444031248614.8092609142125860.04084052248916.654509224
2126130.09597305248757.9378962432126785.25311709248844.418709446
#Sta/Elev= 30
       0 1868.19   182.4 1867.43   271.9  1847.3   332.1 1837.82   421.6 1832.18
   525.4 1830.44   540.7 1828.24   574.9 1818.25   582.5  1816.7   663.7 1815.85
   681.5  1818.4   700.5 1819.04   715.7 1823.09   823.3 1823.52     873 1819.48
   962.3 1823.69  1036.1 1822.38  1074.8 1823.66  1114.6 1821.58  1157.6 1822.75
  1197.3 1837.28  1249.5 1865.42  1256.9 1873.39    1267 1890.72  1289.9 1900.31
  1309.8 1922.88  1316.4 1927.54  1405.8 1959.84  1448.8 1983.18  1465.9 1990.65
#Mann= 8 ,-1 , 0
       0      .1       0      20    .035       0   574.9    .045       0
   681.5    .035       0  681.79      .1       0  731.79     .06       0
  845.04    .035       0 1245.04      .1       0
Bank Sta=574.9,681.5
XS Rating Curve= 0 ,0
Exp/Cntr(USF)=0,0
Exp/Cntr=0.5,0.3

Type RM Length L Ch R = 1 ,1592    ,74.3,77.9,74.9
XS GIS Cut Line= 5
     2125372.805      249083.129     2125983.916      249173.406
     2126105.444      248923.406     2126112.388      248815.768
     2126747.805      248902.573
#Sta/Elev= 30
       0 1829.13   245.1 1830.61   287.6 1829.74   362.8 1823.72   408.6 1822.32
   715.8 1822.79   735.5  1824.6   748.6  1824.3   768.2 1820.14   784.5 1814.94
   836.8 1814.66   856.5 1815.64   882.6 1821.02   957.8 1822.34     997  1821.3
  1039.6 1823.11  1098.5 1818.82  1154.1  1822.4  1311.2 1821.07  1337.3 1822.73
  1363.5 1833.58  1425.7 1868.28  1461.7 1899.83  1487.8 1925.32  1500.9 1941.31
  1510.7 1949.34  1536.9 1960.19  1612.2 1987.07  1635.1 2000.61  1644.9 2005.01
#Mann= 8 ,-1 , 0
       0    .035       0     510     .04       0   768.2    .045       0
   882.6     .06       0  905.72      .1       0 1003.58     .06       0
 1163.58    .035       0 1463.58      .1       0
#XS Ineff= 2 , 0
             760    1827     900            1827
Permanent Ineff=
       F       F
Bank Sta=768.2,882.6
XS Rating Curve= 0 ,0
Exp/Cntr=0.5,0.3

Type RM Length L Ch R = 1 ,1514    ,181.1,262.3,348.8
XS GIS Cut Line= 5
       2125348.5      249121.323     2126029.055       249225.49
     2126150.583       248975.49     2126164.472      248874.795
     2126740.861      248947.712
#Sta/Elev= 30
       0 1828.79     236 1830.18   301.6 1824.02   360.6 1821.32   622.9 1822.05
   642.6 1825.96   665.5 1826.46   688.5 1823.18   750.6  1824.6   802.9 1820.38
   829.1 1820.98   842.2    1815   848.7 1814.72   920.7  1814.9   940.3 1819.59
    1055 1822.22  1120.3 1819.31  1182.3 1822.21  1309.6 1821.58    1326 1823.96
  1404.3 1866.37  1423.9  1879.3  1430.4 1885.39  1440.2 1906.72  1443.5  1910.7
  1469.6 1926.46  1498.9 1950.61  1587.1 1996.49  1632.8 2011.01  1649.1 2020.59
#Mann= 12 ,-1 , 0
       0    .035       0     530     .04       0     640      .1       0
  698.48     .04       0  778.48      .1       0  808.48     .06       0
   829.1    .045       0   940.3     .06       0 1026.45      .1       0
  1078.1     .06       0  1168.1    .035       0  1448.1      .1       0
#XS Ineff= 2 , 0
           831.7    1827   938.3            1827
Permanent Ineff=
       F       F
Bank Sta=829.1,940.3
XS Rating Curve= 0 ,0
Exp/Cntr=0.5,0.3