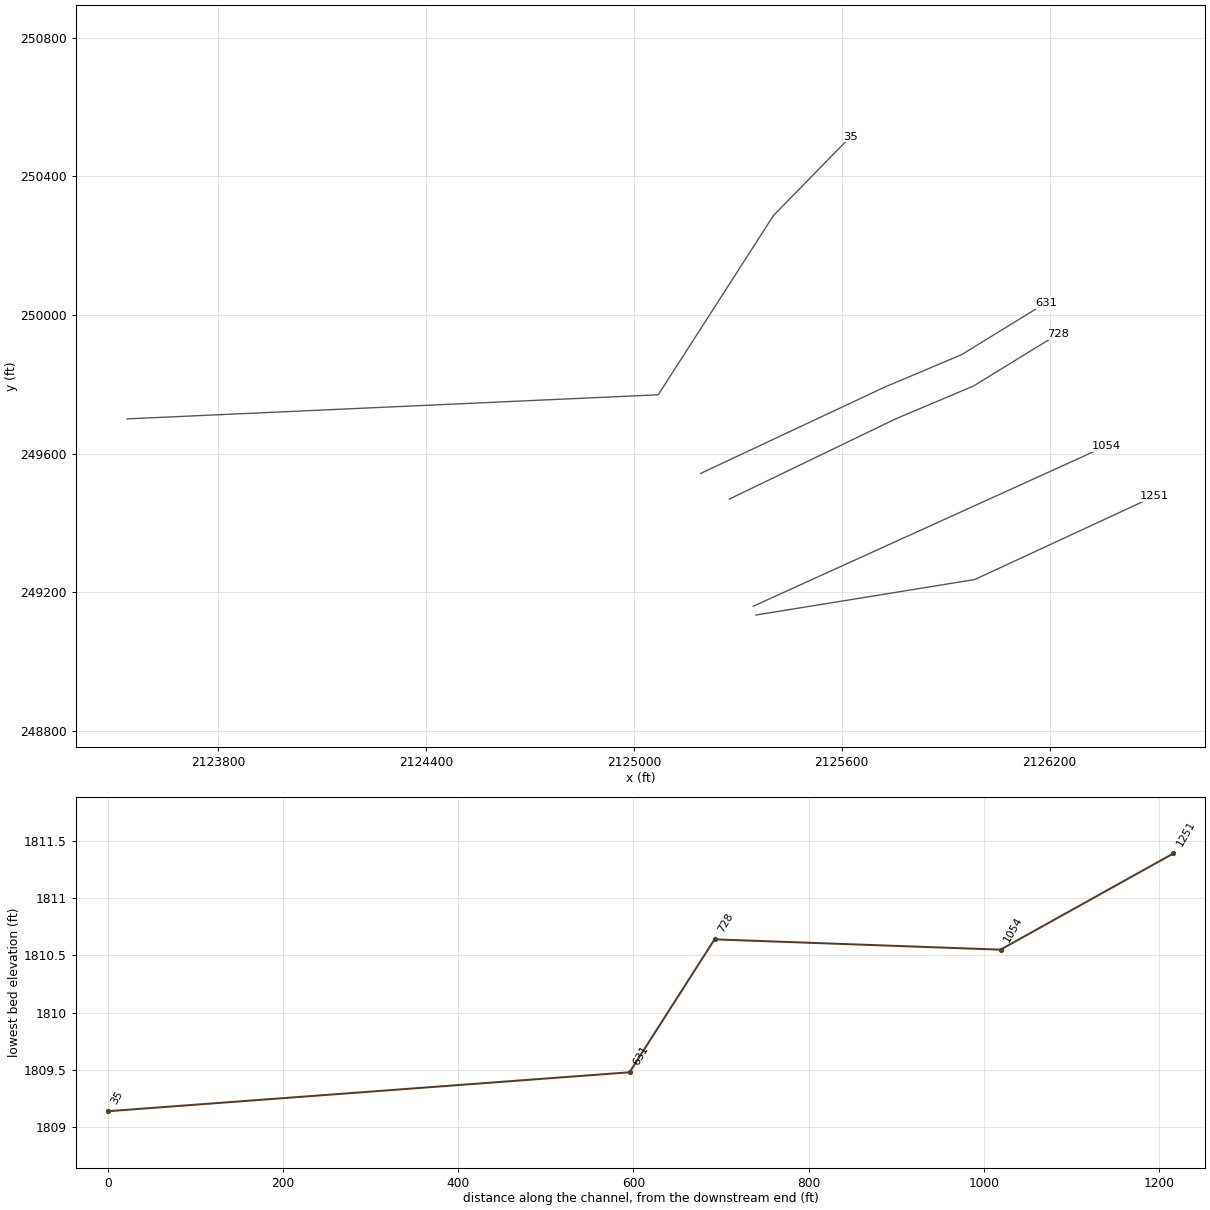
HEC-RAS study SECONDCK.prj: SECONDCK

--- SECONDCK.g01 (geometry) --- (continued)

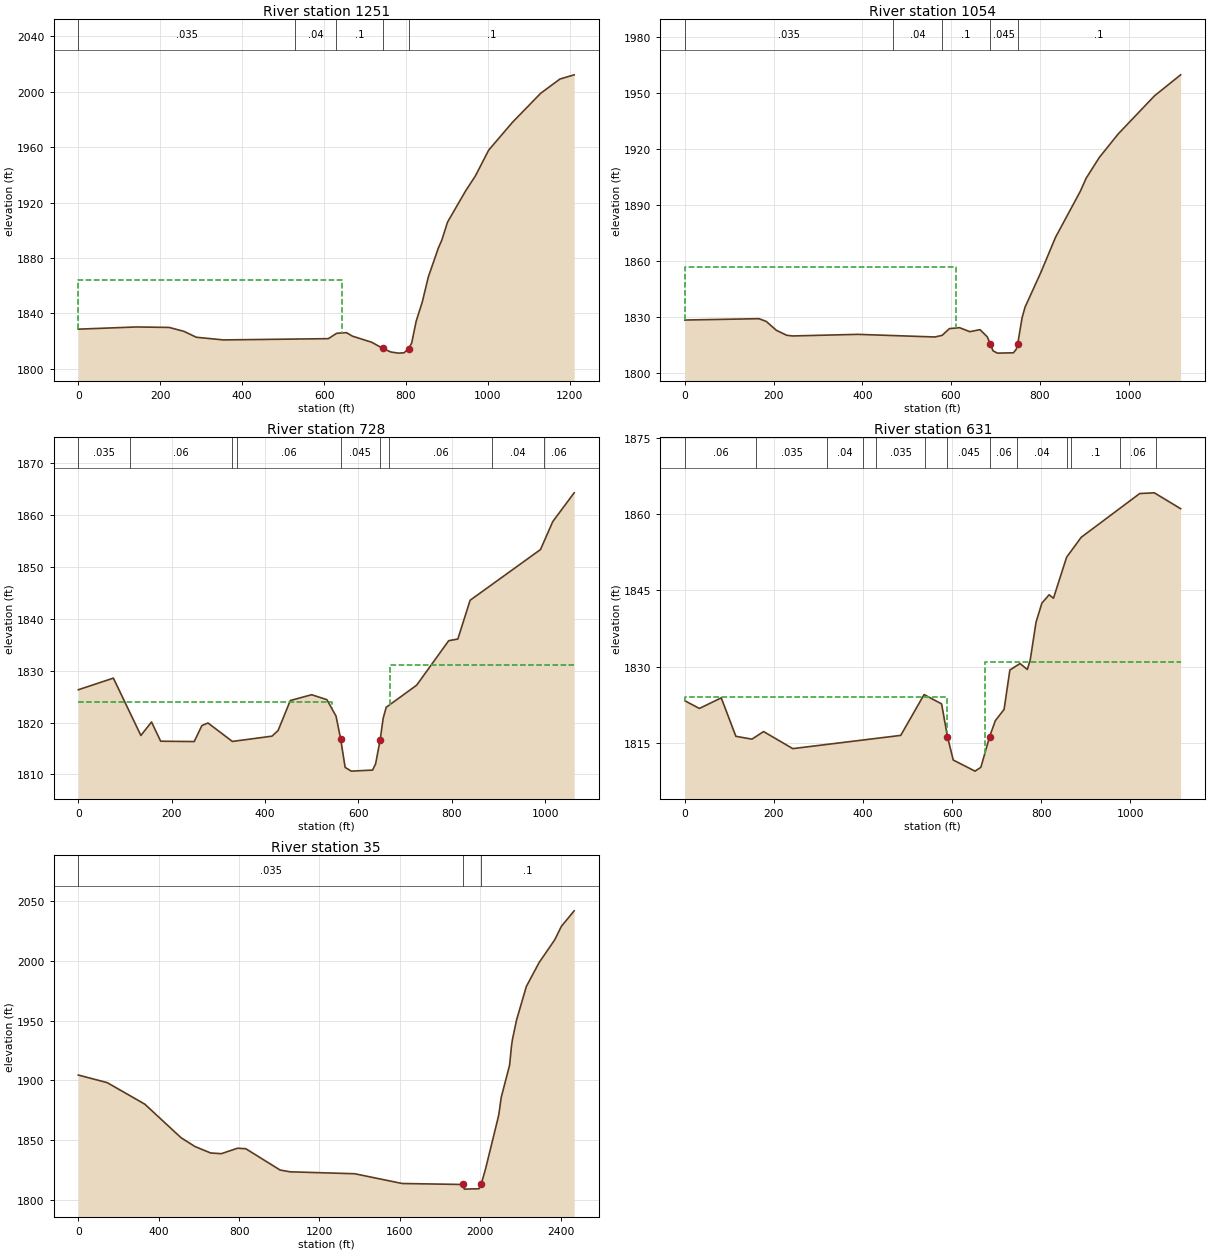
Type RM Length L Ch R = 1 ,1251    ,196,197.4,195.8
XS GIS Cut Line= 3
 2125352.2120196249133.9515026122125983.91993196249236.311581004
2126501.56947126249476.126621809
#Sta/Elev= 30
       0 1828.69   141.6 1830.27   221.7 1829.94     258 1827.09   287.9 1822.85
   354.4 1820.92   610.3 1821.83   630.7 1825.71   654.7 1826.14   669.2 1823.63
   716.2 1819.24   743.6 1814.77   762.4 1812.24   781.3 1811.39   795.1 1811.62
   806.6 1814.71   813.8 1818.69   824.7 1834.38   839.6 1848.27   854.4 1866.35
   878.9 1887.28   887.3 1892.91   901.3 1905.94   945.7  1928.6   969.3 1939.27
  1001.8 1957.91  1059.7 1977.94  1128.7 1998.92  1175.6 2009.17  1210.4 2012.23
#Mann= 5 ,-1 , 0
       0    .035       0     530     .04       0     630      .1       0
   743.6    .045       0   806.6      .1       0
#XS Ineff= 2 , 0
          644.85 1864.16
Permanent Ineff=
       F       F
Bank Sta=743.6,806.6
XS Rating Curve= 0 ,0
Exp/Cntr(USF)=0,0
Exp/Cntr=0.3,0.1

Type RM Length L Ch R = 1 ,1054    ,329.2,326.5,322.3
XS GIS Cut Line= 2
     2125345.027      249159.518     2126362.388      249621.323
#Sta/Elev= 30
       0  1828.3   167.1 1829.02   183.5 1827.57   206.4 1822.78   229.4 1820.15
   242.5 1819.76   389.9 1820.62   563.6 1819.21   579.9 1820.09   596.3  1823.7
   619.2  1824.2   642.2 1822.05   665.1 1823.15   681.5 1819.33     688  1815.7
   694.6  1811.8   704.4 1810.55   740.5 1810.73     747 1812.66   750.3 1815.64
   760.1 1829.58   766.7  1835.2   802.7 1854.04   835.5 1872.74   891.2 1897.33
   904.3 1904.31   933.8 1915.42   976.4 1928.06  1058.3 1948.54  1117.3 1959.83
#Mann= 5 ,-1 , 0
       0    .035       0     470     .04       0     580      .1       0
     688    .045       0   750.3      .1       0
#XS Ineff= 2 , 0
          611.35 1856.94
Permanent Ineff=
       F       F
Bank Sta=688,750.3
XS Rating Curve= 0 ,0
Exp/Cntr=0.5,0.3

Type RM Length L Ch R = 1 ,728     ,98.4,97,97.2
XS GIS Cut Line= 4
     2125275.583      249468.545     2125758.222      249701.184
     2125980.444      249794.934       2126223.5       249944.24
#Sta/Elev= 30
       0 1826.32    75.1 1828.56     134 1817.51   156.8 1820.11   176.4  1816.4
   248.3 1816.34   264.6 1819.41   277.7 1819.92     330 1816.36   414.9 1817.38
     428 1818.47   454.1 1824.24   499.8 1825.36   532.5 1824.41   552.1 1821.24
   561.9 1816.88   571.6 1811.36   584.7 1810.64   630.3 1810.84   636.8 1812.02
   646.6 1816.66   653.1 1820.85   659.6 1822.94   724.8  1827.2   793.4 1835.77
     813 1836.09   839.3 1843.56   990.1 1853.33  1016.3 1858.71  1062.2 1864.26
#Mann= 9 ,-1 , 0
       0    .035       0     110     .06       0     330     .04       0
     340     .06       0   561.9    .045       0   646.6     .08       0
  665.78     .06       0  886.97     .04       0  996.97     .06       0
#XS Ineff= 2 , 0
           542.5    1824   667.5            1831
Permanent Ineff=
       F       F
Bank Sta=561.9,646.6
XS Rating Curve= 0 ,0
Exp/Cntr=0.5,0.3

Type RM Length L Ch R = 1 ,631     ,595.7,595.7,595.7
XS GIS Cut Line= 4
     2125192.902      249542.655       2125723.5      249791.462
     2125945.722      249885.212     2126188.777      250034.518
#Sta/Elev= 30
       0 1823.31    32.7 1821.79    81.8 1823.87   114.6 1816.32   150.6 1815.76
   176.8 1817.25   242.3  1813.9   484.5  1816.5   536.9 1824.52   576.2 1822.68
   589.3 1816.28   602.3 1811.66   651.2 1809.48   664.3 1810.23   683.8 1816.22
   696.8  1819.4   716.4  1821.6   729.4 1829.35   752.3 1830.61   768.6 1829.44
   775.1 1831.35   788.1 1838.74   801.2 1842.47   817.4 1844.12   827.2 1843.44
   856.7  1851.5   889.5 1855.41  1020.7    1864  1053.5 1864.14  1112.5 1861.03
#Mann= 13 ,-1 , 0
       0     .06       0     160    .035       0     320     .04       0
     400      .1       0     430    .035       0     540     .06       0
   589.3    .045       0   683.8     .06       0  746.04     .04       0
  857.22     .06       0  867.22      .1       0  977.22     .06       0
 1057.22      .1       0
#XS Ineff= 2 , 0
           587.5    1824   672.5            1831
Permanent Ineff=
       F       F
Bank Sta=589.3,683.8
XS Rating Curve= 0 ,0
Exp/Cntr=0.5,0.3

Type RM Length L Ch R = 1 ,35      ,,,
XS GIS Cut Line= 4
2123537.49972725249700.0287185072125070.38723464249769.554933746
2125403.38400155250287.3635337272125625.41414144250514.439813164
#Sta/Elev= 30
       0 1904.49   143.7 1898.15   330.9 1880.16   511.5 1852.06   580.5 1844.75
   658.5 1839.36   711.9 1838.77     792 1843.32   833.4 1842.92  1004.2  1825.1
  1053.4 1823.62  1375.3    1822  1612.1 1813.84  1912.51813.027  1921.3 1809.14
  1994.3 1809.47 2005.741813.707  2026.6 1825.98  2086.9 1867.24  2092.9 1871.64
  2104.6 1885.77  2146.2 1912.63  2156.2 1929.27  2160.8 1934.42  2181.1 1950.55
  2229.8 1978.56  2293.9 1998.67  2371.4  2017.6  2403.8 2028.71  2467.7 2041.74
#Mann= 3 ,-1 , 0
       0    .035       0  1912.5    .045       0 2005.74      .1       0
Bank Sta=1912.5,2005.74
XS Rating Curve= 0 ,0
Exp/Cntr=0.3,0.1
LCMann Table=0

Chan Stop Cuts=-1
Use User Specified Reach Order=0
Composite Channel Slope=5